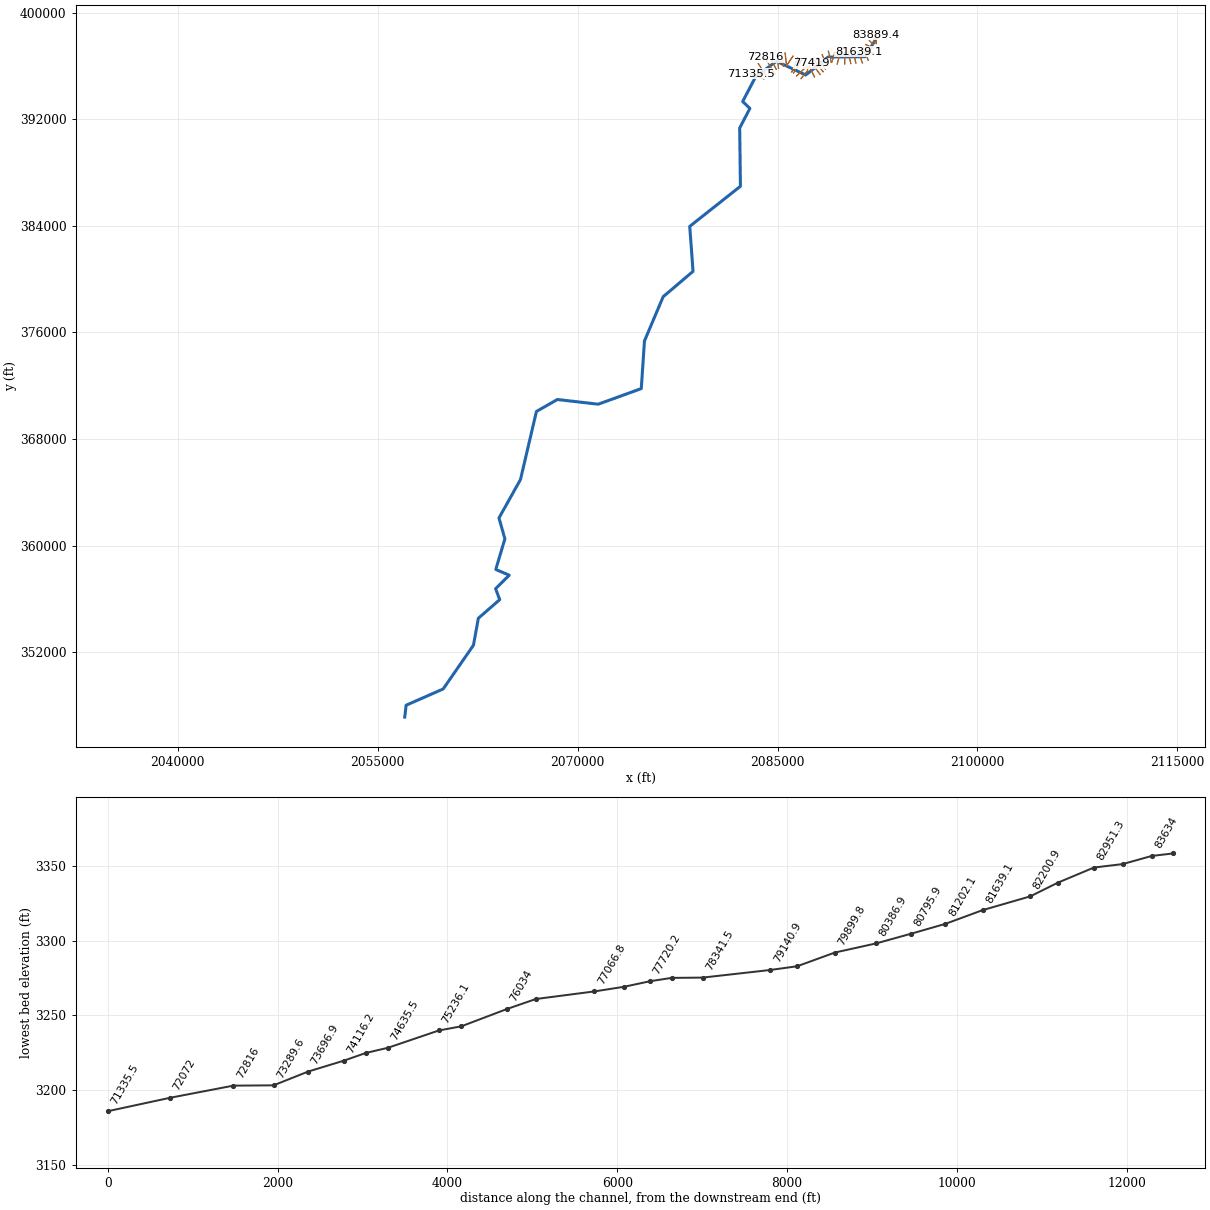
--- BigClearCk.prj (project) ---

Proj Title=BigClearCk
Current Plan=p01
Default Exp/Contr=0,0
English Units
Geom File=g01
Flow File=f01
Plan File=p01
BEGIN DESCRIPTION:
END DESCRIPTION:
DSS Export Rating Curves= 0
DSS Export Rating Curve Sorted= 0
DSS Export Volume Flow Curves= 0
DXF OffsetX= 0
DXF OffsetY= 0
DXF ScaleX= 0
DXF ScaleY= 0

--- BigClearCk.p01 (plan) ---

Plan Title=Floodplain
Program Version=4.00
Geom File=g01
Flow File=f01
K Sum by GR=0
Std Step Tol=0.01
Critical Tol=0.01
Num of Std Step Trials=20
Max Error Tol=0.3
Flow Tol Ratio=0.001
Split Flow NTrial=30
Split Flow Tol=0.02
Split Flow Ratio=0.02
Log Output Level=0
Friction Slope Method=1
Unsteady Friction Slope Method=2
Unsteady Bridges Friction Slope Method=1
Global Log Level=0
CheckData=False
Run HTab=0
Run UNet=0
Run PostProcess=0
UNET Theta=0
UNET Theta Warmup=0
UNET ZTol=0
UNET ZSATol=0
UNET MxIter=0
UNET MaxInSteps=0
UNET DtIC=0
UNET DtMin=0
UNET MaxCRTS=0
UNET WFStab=0
UNET SFStab=0
UNET WFX=0
UNET SFX=0
UNET DSS MLevel=0
UNET DZMax Abort=0
UNET Convert EG Bridges=0
UNET Use Existing IB Tables=0
UNET Froude Limit=0
UNET Froude Power=0
Write IC File=0
Echo Input=False
Echo Output=False
Write Detailed=0

--- BigClearCk.f01 (steady flow) ---

Flow Title=NFF Regression Equation
Program Version=4.00
Number of Profiles=1
Profile Names=P100yr
River Rch & RM=BigClearCk,Main      ,83889.4
578.2807
River Rch & RM=BigClearCk,Main      ,82200.9
610.2454
River Rch & RM=BigClearCk,Main      ,81639.1
676.8351
River Rch & RM=BigClearCk,Main      ,79140.9
743.7122
River Rch & RM=BigClearCk,Main      ,78341.5
882.2835
River Rch & RM=BigClearCk,Main      ,74374.4
971.6695
River Rch & RM=BigClearCk,Main      ,74116.2
1125.955
River Rch & RM=BigClearCk,Main      ,71335.5
1149.731
River Rch & RM=BigClearCk,Main      ,70880
1324.392
River Rch & RM=BigClearCk,Main      ,68918.4
1348.861
River Rch & RM=BigClearCk,Main      ,67512.6
1637.728
River Rch & RM=BigClearCk,Main      ,66826.1
1731.646
River Rch & RM=BigClearCk,Main      ,61674.5
1884.430
River Rch & RM=BigClearCk,Main      ,54176.8
2092.714
River Rch & RM=BigClearCk,Main      ,53840.5
2501.716
River Rch & RM=BigClearCk,Main      ,53537.2
2533.742
River Rch & RM=BigClearCk,Main      ,45701.1
2808.174
River Rch & RM=BigClearCk,Main      ,40648.1
3099.865
River Rch & RM=BigClearCk,Main      ,40382.9
5222.698
River Rch & RM=BigClearCk,Main      ,32948.9
5379.909
River Rch & RM=BigClearCk,Main      ,32555.5
6175.368
River Rch & RM=BigClearCk,Main      ,27260.1
6328.446
River Rch & RM=BigClearCk,Main      ,5169.4
6930.788
River Rch & RM=BigClearCk,Main      ,2751.4
6964.280
Boundary for River Rch & Prof#=BigClearCk,Main      ,1
Up Type=0
Dn Type=3
Dn Slope=0.002085

--- BigClearCk.g01 (geometry) ---

Geom Title=USGS 10m DEM
Program Version=4.10

River Reach=BigClearCk      ,Main
Reach XY= 30
     2092415.491      398069.683     2091569.432      396698.126
     2088799.518        396669.8     2087118.593      395323.191
     2084923.574      396352.954     2083378.925      395226.442
     2082385.995      393333.952     2082928.916      392816.462
     2082162.265      391346.003     2082217.541      386972.948
     2078413.838      383963.718     2078662.206      380589.294
     2076420.879       378685.18     2075016.064      375364.873
      2074777.41      371788.234     2071544.917      370619.761
     2068482.962      370971.143     2066908.954      370073.294
     2065711.821      364964.894     2064098.226      362078.157
     2064543.192      360516.817     2063857.533      358217.563
     2064870.978      357786.848     2063844.864      356773.403
     2064155.232      355953.145     2062549.554      354554.907
     2062183.764      352532.766     2059911.428      349250.152
     2057129.712      348027.791     2057028.558      347140.618

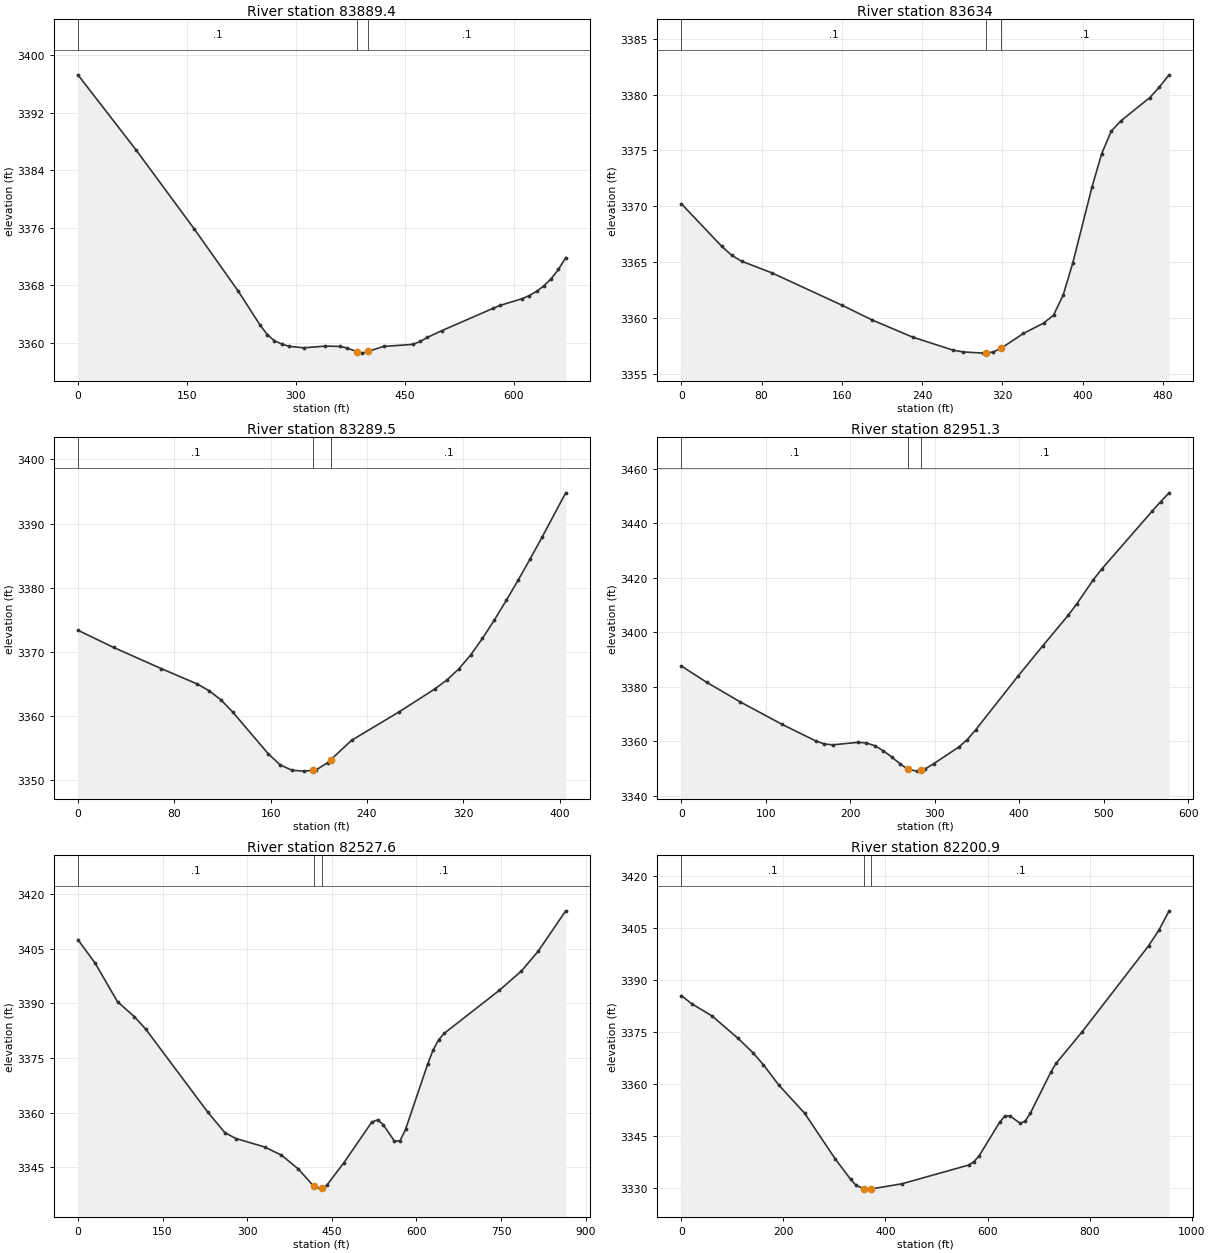
Type RM Length L Ch R = 1 ,83889.4 ,246.4,255.3,263.5
XS GIS Cut Line= 2
     2092401.462       397680.44     2092403.958      398351.941
#Sta/Elev= 30
       0 3397.29    80.2 3386.82   160.4 3375.82   220.5 3367.24   250.6 3362.52
   260.6 3361.17   270.6 3360.31   280.6 3359.86   290.6 3359.54   310.7 3359.33
   340.8 3359.57   360.8 3359.52   370.8  3359.3   383.8 3358.79   390.9 3358.59
   398.8 3358.82   420.9 3359.52     461 3359.81   471.1 3360.21   481.1 3360.78
   501.1 3361.72   571.3 3364.81   581.3 3365.23   611.4 3366.16   621.4 3366.59
   631.4 3367.18   641.4 3367.94   651.5 3368.94   661.5 3370.24   671.5 3371.87
#Mann= 3 , 0 , 0
       0      .1       0   383.8    .045       0   398.8      .1       0
Bank Sta=383.8,398.8
XS Rating Curve= 0 ,0
Exp/Cntr=0.3,0.1

Type RM Length L Ch R = 1 ,83634   ,333.9,344.4,354.8
XS GIS Cut Line= 3
     2092286.154      397770.949     2092167.055      398122.365
     2092079.441      398197.171
#Sta/Elev= 26
       0 3370.24    40.1 3366.45    50.1 3365.64    60.2  3365.1    90.3 3364.06
   160.4 3361.16   190.5 3359.84   230.6 3358.32   270.8 3357.16   280.8    3357
   300.8 3356.89     304 3356.92   310.9 3356.99     319 3357.34     341 3358.65
     361 3359.57     371 3360.28   380.6 3362.08   390.2 3364.95   409.4 3371.75
     419 3374.72   428.6 3376.74   438.2 3377.65     467 3379.73   476.6 3380.68
   486.2 3381.76
#Mann= 3 , 0 , 0
       0      .1       0     304    .045       0     319      .1       0
Bank Sta=304,319
XS Rating Curve= 0 ,0
Exp/Cntr=0.3,0.1

Type RM Length L Ch R = 1 ,83289.5 ,329.4,336.4,343.4
XS GIS Cut Line= 2
     2092187.753      397625.236     2091893.748      397903.835
#Sta/Elev= 28
       0 3373.38    29.6  3370.7    69.2  3367.4    98.8 3365.03   108.7 3363.98
   118.6 3362.55   128.4 3360.66   158.1 3354.11   167.9 3352.39   177.8 3351.55
   187.7 3351.42     195 3351.55   197.6 3351.59   207.5 3352.76     210 3353.21
   227.2 3356.22   266.7 3360.66   296.4 3364.24   306.2  3365.6   316.1 3367.33
     326  3369.5   335.9 3372.12   345.8 3374.99   355.6 3378.02   365.5 3381.19
   375.4 3384.48   385.3 3387.86     405  3394.8
#Mann= 3 , 0 , 0
       0      .1       0     195    .045       0     210      .1       0
Bank Sta=195,210
XS Rating Curve= 0 ,0
Exp/Cntr=0.3,0.1

Type RM Length L Ch R = 1 ,82951.3 ,418.7,423.5,428.3
XS GIS Cut Line= 2
     2092153.078      397347.288     2091635.096      397602.577
#Sta/Elev= 30
       0 3387.64    29.9  3381.7    69.7 3374.49   119.5 3366.22   159.3 3360.16
   169.3 3359.09   179.2 3358.75   209.1 3359.67     219 3359.47     229 3358.42
     239 3356.61   248.9 3354.35   258.9 3351.81   268.3 3349.79   278.8 3349.12
   283.3  3349.5   288.7 3349.95   298.7 3351.83   328.6 3357.97   338.5 3360.67
   348.5 3364.26   398.3 3383.82   428.1  3395.1     458 3406.22     468 3410.33
   487.9 3419.32   497.8  3423.2   557.6 3444.44   567.5 3447.87   577.5  3451.1
#Mann= 3 , 0 , 0
       0      .1       0   268.3    .045       0   283.3      .1       0
Bank Sta=268.3,283.3
XS Rating Curve= 0 ,0
Exp/Cntr=0.3,0.1

Type RM Length L Ch R = 1 ,82527.6 ,347.8,326.5,304.7
XS GIS Cut Line= 3
     2092195.829       396955.58     2091663.562      397099.112
     2091454.244      397332.353
#Sta/Elev= 30
       0 3407.48    30.1 3401.13    70.2 3390.45   100.2 3386.33   120.3 3382.91
   230.5 3360.08   260.6 3354.49   280.6 3352.88   330.8 3350.59   360.8 3348.34
   390.9 3344.51   418.4 3339.74     431 3339.01   433.4 3339.26     441 3340.04
   471.1 3346.18   521.2 3357.47   531.2    3358   541.3  3356.7   561.1 3352.18
   570.9 3352.24   580.7 3355.38   619.8 3373.24   629.6 3377.18   639.4    3380
   649.2 3381.75   747.2  3393.6   786.3  3398.9   815.7 3404.27   864.7  3415.4
#Mann= 3 , 0 , 0
       0      .1       0   418.4    .045       0   433.4      .1       0
Bank Sta=418.4,433.4
XS Rating Curve= 0 ,0
Exp/Cntr=0.3,0.1

Type RM Length L Ch R = 1 ,82200.9 ,563.6,561.6,560.1
XS GIS Cut Line= 2
     2091806.421      396434.726     2091431.162      397313.757
#Sta/Elev= 30
       0 3385.55    20.1 3383.23    60.4 3379.66   110.7 3373.29   140.8 3369.02
     161 3365.59   191.2 3359.74   241.5 3351.69   301.8 3338.45     332 3332.58
   342.1 3330.94   357.5  3329.9   362.2  3329.8   372.5 3329.86   432.6 3331.35
   563.4 3336.75   573.5 3337.74   583.5 3339.39   623.8 3349.07   633.8 3350.85
   643.9  3350.9     664 3348.75   674.1 3349.44   684.1 3351.73   724.4  3363.6
   734.4 3366.05   784.8    3375   915.5 3399.87   935.7 3404.36   955.8 3409.96
#Mann= 3 , 0 , 0
       0      .1       0   357.5    .045       0   372.5      .1       0
Bank Sta=357.5,372.5
XS Rating Curve= 0 ,0
Exp/Cntr=0.3,0.1

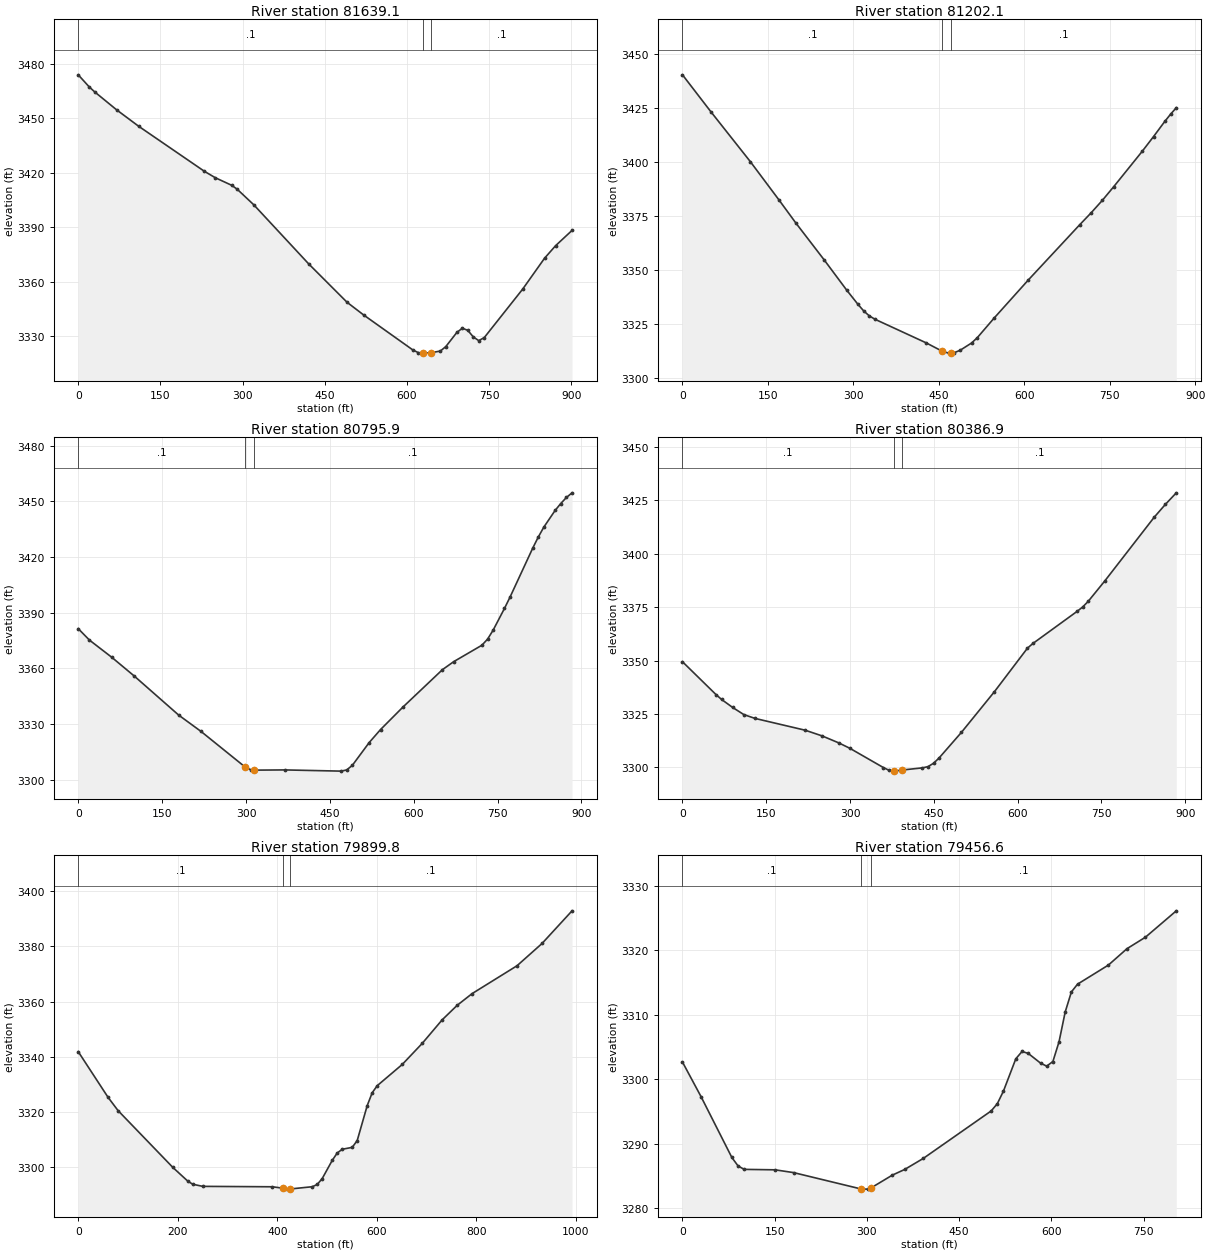
Type RM Length L Ch R = 1 ,81639.1 ,439.4,437,434.5
XS GIS Cut Line= 2
     2091368.803      396231.592      2091080.96      397085.934
#Sta/Elev= 30
       0 3473.89      20 3467.26      30  3464.5    70.1  3454.6   110.2 3445.58
   230.4 3420.72   250.4 3417.17   280.5 3412.98   290.5 3410.78   320.5 3402.28
   420.7 3369.73   490.8 3348.57   520.9 3341.62     611 3322.28     621  3320.8
   628.7 3320.62   631.1 3320.56   643.7 3320.75   661.1 3321.71   671.1 3324.18
   691.2 3331.96   701.2 3334.29   711.2 3333.11   721.2 3329.49   731.2 3327.44
   741.3 3329.14   811.4 3355.84   851.4 3372.88   871.5 3379.76   901.5 3388.18
#Mann= 3 , 0 , 0
       0      .1       0   628.7    .045       0   643.7      .1       0
Bank Sta=628.7,643.7
XS Rating Curve= 0 ,0
Exp/Cntr=0.3,0.1

Type RM Length L Ch R = 1 ,81202.1 ,406.2,405.8,405.4
XS GIS Cut Line= 3
     2090878.677      396219.775     2090795.613      396598.456
     2090689.343      397065.747
#Sta/Elev= 30
       0 3440.53    49.7 3423.45   119.3 3400.18     169 3382.61   198.8 3371.84
   248.5 3354.73   288.3 3340.61   308.2 3333.97   318.1 3330.97     328 3328.66
     338 3327.09   427.6 3316.17   456.2 3312.23   467.6 3311.38   471.2 3311.47
   477.5 3311.63   487.5 3312.72   507.5 3316.08   517.5 3318.54   547.4 3327.74
   607.3 3345.38   697.2 3370.92   717.2 3376.44   737.1 3382.29   757.1 3388.64
     807 3405.01     827 3411.89   846.9 3418.98   856.9 3422.27   866.9 3425.28
#Mann= 3 , 0 , 0
       0      .1       0   456.2    .045       0   471.2      .1       0
Bank Sta=456.2,471.2
XS Rating Curve= 0 ,0
Exp/Cntr=0.3,0.1

Type RM Length L Ch R = 1 ,80795.9 ,413.9,409.3,404.4
XS GIS Cut Line= 3
     2090497.259      396184.176     2090415.969      396554.768
     2090304.277      397045.898
#Sta/Elev= 30
       0 3381.45      20  3375.3    59.9 3366.05    99.8 3356.04   179.7  3334.9
   219.6 3326.12   298.8 3306.88   309.5 3305.35   313.8 3305.28   369.4  3305.4
   470.1 3304.75   480.1 3305.39   490.2 3307.87   520.4 3320.16   540.6 3327.12
   580.9  3339.3   651.4 3359.39   671.5 3363.69   721.9 3372.53     732  3375.8
     742 3380.65   762.2 3392.31   772.3  3398.5   812.6 3424.67   822.6  3430.7
   832.7 3436.14   852.8 3445.08   862.9  3448.8     873 3452.06   883.1 3454.57
#Mann= 3 , 0 , 0
       0      .1       0   298.8    .045       0   313.8      .1       0
Bank Sta=298.8,313.8
XS Rating Curve= 0 ,0
Exp/Cntr=0.3,0.1

Type RM Length L Ch R = 1 ,80386.9 ,493.5,487,480.8
XS GIS Cut Line= 3
     2090044.077      396150.296     2090047.453       396629.83
     2090047.194      397034.281
#Sta/Elev= 30
       0 3349.46    59.9 3334.13    69.9 3331.84    89.9 3328.06   109.9 3324.73
   129.9 3322.95   219.8 3317.42   249.8 3314.78   279.7 3311.51   299.7 3308.96
   359.7 3299.95   369.6  3298.7   378.5 3298.34   379.6 3298.29   393.5 3298.81
   429.6 3299.82   439.6  3300.4   449.6    3302   459.6 3304.52   499.3 3316.41
   558.5 3335.48   617.6 3355.84   627.5 3358.05   706.4 3373.03   716.3 3375.06
   726.2 3377.68   755.8  3387.2   844.5 3417.09   864.3 3423.04     884 3428.49
#Mann= 3 , 0 , 0
       0      .1       0   378.5    .045       0   393.5      .1       0
Bank Sta=378.5,393.5
XS Rating Curve= 0 ,0
Exp/Cntr=0.3,0.1

Type RM Length L Ch R = 1 ,79899.8 ,446,443.1,439.5
XS GIS Cut Line= 3
      2089480.94      396147.332     2089603.414      396611.736
     2089730.167      397107.795
#Sta/Elev= 30
       0 3341.91      60 3325.36      80 3320.58   190.1 3300.01   220.1 3295.05
   230.1 3293.92   250.2 3293.15   390.2    3293   411.4 3292.48   420.2 3292.15
   426.4 3292.21   470.3 3293.02   480.3 3293.84   490.3 3295.99   510.4 3302.55
   520.4 3305.22   530.5 3306.58   550.6 3307.27   560.6 3309.74   580.7 3322.38
   590.7 3327.03   600.8 3329.59     651 3337.26   691.1 3344.87   731.3 3353.42
   761.4 3358.67   791.5 3362.92   881.8 3373.01     932 3381.06   992.3 3392.88
#Mann= 3 , 0 , 0
       0      .1       0   411.4    .045       0   426.4      .1       0
Bank Sta=411.4,426.4
XS Rating Curve= 0 ,0
Exp/Cntr=0.3,0.1

Type RM Length L Ch R = 1 ,79456.6 ,301,314.8,327.5
XS GIS Cut Line= 2
     2089071.658       396280.51     2089313.263      397046.449
#Sta/Elev= 30
       0 3302.65    30.1 3297.31    80.3 3287.87    90.4 3286.56   100.4 3286.03
   150.6 3285.96   180.7 3285.53     291 3282.98   301.2 3282.97     306 3283.12
   341.3 3285.14   361.4 3286.02   391.5 3287.72     502 3295.08     512  3296.2
     522 3298.16   542.1 3303.16   552.2 3304.29   562.2    3304   582.3 3302.49
   592.3 3302.02   602.4 3302.74   612.4  3305.8   622.4 3310.41   632.5 3313.52
   642.5 3314.72   692.7 3317.68   722.8 3320.21     753    3322   803.1 3326.08
#Mann= 3 , 0 , 0
       0      .1       0     291    .045       0     306      .1       0
Bank Sta=291,306
XS Rating Curve= 0 ,0
Exp/Cntr=0.3,0.1

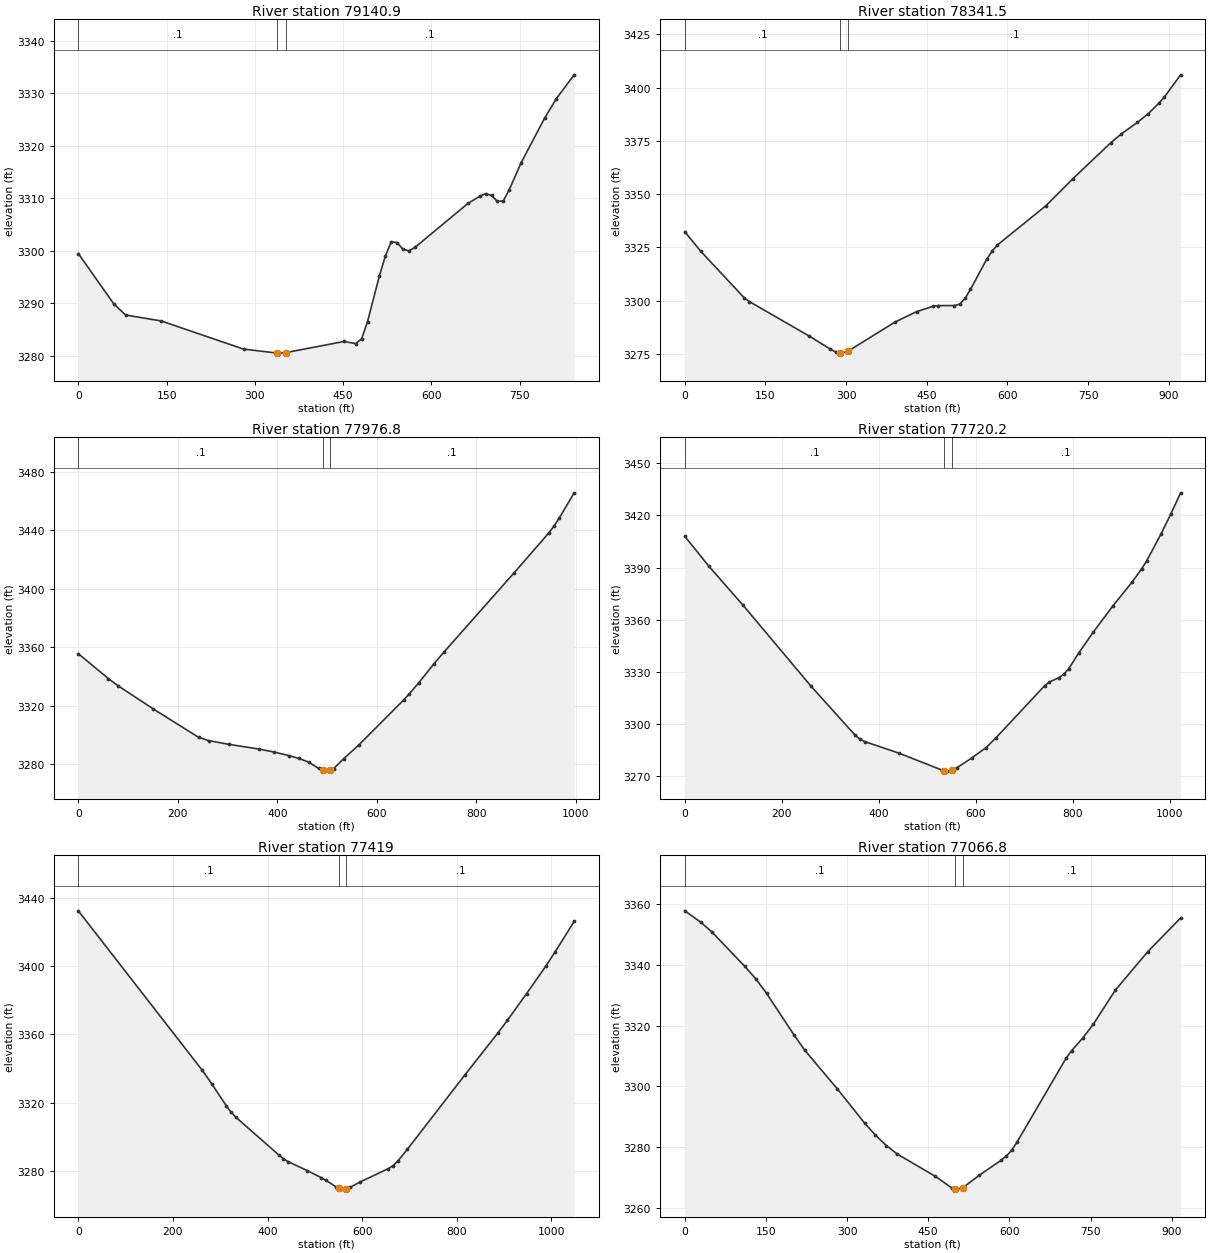
Type RM Length L Ch R = 1 ,79140.9 ,795.3,799.2,802.6
XS GIS Cut Line= 2
     2089025.393      396290.791     2088819.771      397108.136
#Sta/Elev= 30
       0 3299.45    60.2 3289.87    80.3 3287.74   140.5 3286.62   280.9 3281.25
   337.8 3280.49   341.1 3280.48   352.8 3280.58   451.5  3282.7   471.6 3282.29
   481.6 3283.23   491.6 3286.49   511.7 3295.18   521.7 3298.91   531.8 3301.67
   541.8 3301.55   551.8 3300.27   561.9 3299.97   571.9  3300.6   662.2 3308.99
   682.3 3310.36   692.3 3310.86   702.3 3310.51   712.4 3309.38   722.4 3309.48
   732.4  3311.6   752.5  3316.7   792.6 3325.25   812.7 3328.98   842.8 3333.49
#Mann= 3 , 0 , 0
       0      .1       0   337.8    .045       0   352.8      .1       0
Bank Sta=337.8,352.8
XS Rating Curve= 0 ,0
Exp/Cntr=0.3,0.1

Type RM Length L Ch R = 1 ,78341.5 ,359.4,364.1,368.7
XS GIS Cut Line= 2
     2088747.421      396001.473     2088352.609      396834.532
#Sta/Elev= 30
       0 3332.35    30.1 3323.09   110.2  3301.4   120.2 3299.55   230.5  3283.5
   270.6 3277.25   280.6 3275.86   288.6 3275.46   290.6 3275.36   303.6  3276.3
   390.8 3289.94   430.9 3294.84   460.9  3297.3     471 3297.68     501  3297.7
     511 3298.35   521.1 3301.06   531.1 3305.25   561.1 3319.36   571.2 3323.22
   581.2 3326.13   671.4 3344.58   721.5 3357.25   791.6 3374.06   811.7 3378.33
   841.7 3383.75   861.8 3387.82   881.8 3392.81   891.8  3395.7   921.9 3406.06
#Mann= 3 , 0 , 0
       0      .1       0   288.6    .045       0   303.6      .1       0
Bank Sta=288.6,303.6
XS Rating Curve= 0 ,0
Exp/Cntr=0.3,0.1

Type RM Length L Ch R = 1 ,77976.8 ,256.6,256.6,256.6
XS GIS Cut Line= 2
     2088584.982       395775.75     2087984.448      396571.602
#Sta/Elev= 30
       0 3355.47    60.4 3338.45    80.6 3333.39   151.1 3317.61   241.7 3298.31
   261.8 3296.07   302.1 3293.52   362.6 3290.29   392.8  3288.3     423 3285.83
   443.1 3283.89   463.3 3281.31   483.4 3277.02     491  3275.7   493.5 3275.26
   503.5 3275.17     506 3275.61   513.6 3276.95   533.8 3283.75     564 3293.05
   654.6 3323.99   664.7 3327.71   684.8 3335.71     715 3348.55   735.2 3356.59
   876.2 3410.74   946.6 3438.29   956.7  3442.9   966.8 3448.06     997 3465.46
#Mann= 3 , 0 , 0
       0      .1       0     491    .045       0     506      .1       0
Bank Sta=491,506
XS Rating Curve= 0 ,0
Exp/Cntr=0.3,0.1

Type RM Length L Ch R = 1 ,77720.2 ,301.2,301.2,301.2
XS GIS Cut Line= 2
     2088417.583      395572.927      2087801.71      396389.105
#Sta/Elev= 30
       0 3407.94    50.1 3390.58   120.3 3368.26   260.6 3321.67   350.8 3293.72
   360.9 3291.34   370.9 3289.92   441.1 3283.31   531.3 3273.42   535.5 3273.21
   541.3 3272.92   550.5 3273.32   561.4 3274.94   591.4  3280.4   621.5 3286.48
   641.6 3292.05   741.8 3321.96   751.8 3324.13   771.9 3326.73   781.9 3328.71
   791.9 3331.87     812 3340.69     842 3352.71   882.1 3367.68   922.2 3381.54
   942.3 3389.26   952.3 3393.72   982.4 3409.48  1002.4 3420.87  1022.5 3432.94
#Mann= 3 , 0 , 0
       0      .1       0   535.5    .045       0   550.5      .1       0
Bank Sta=535.5,550.5
XS Rating Curve= 0 ,0
Exp/Cntr=0.3,0.1

Type RM Length L Ch R = 1 ,77419   ,356.7,352,347.3
XS GIS Cut Line= 2
     2088193.448      395371.899     2087562.238      396208.404
#Sta/Elev= 30
       0 3432.41     262 3338.88   282.1 3330.96   312.4 3318.21   322.4 3314.48
   332.5 3311.51   423.2 3289.38   433.3 3287.08   443.4 3285.36   483.7 3280.13
   513.9 3275.88     524 3274.31   544.1 3270.62   551.5 3269.67   554.2 3269.33
   564.3 3269.23   566.5 3269.46   574.4 3270.27   594.5  3273.3     655 3281.23
     665    3283   675.1 3285.63   695.3 3292.55   816.2 3335.92   886.7  3360.8
   906.9 3368.22   947.2 3383.85   987.5 3399.77  1007.6 3408.31  1047.9  3426.2
#Mann= 3 , 0 , 0
       0      .1       0   551.5    .045       0   566.5      .1       0
Bank Sta=551.5,566.5
XS Rating Curve= 0 ,0
Exp/Cntr=0.3,0.1

Type RM Length L Ch R = 1 ,77066.8 ,715.9,689.5,663.1
XS GIS Cut Line= 2
     2087771.103      395180.436     2087382.052      396010.323
#Sta/Elev= 30
       0 3357.79    30.2 3353.96    50.4 3350.77   110.8 3339.51   130.9 3335.46
   151.1 3330.62   201.4 3317.03   221.6 3311.91     282 3299.12   332.4 3287.87
   352.5 3283.86   372.7 3280.43   392.8 3277.66   463.3  3270.3   493.5 3266.49
   499.5 3266.26   503.6  3266.1   514.5 3266.63   543.9 3270.61   584.2 3275.54
   594.2 3276.94   604.3 3278.91   614.4 3281.67     705 3309.26   715.1 3311.74
   735.3  3315.8   755.4 3320.48   795.7 3331.62   856.1 3344.38   916.6 3355.43
#Mann= 3 , 0 , 0
       0      .1       0   499.5    .045       0   514.5      .1       0
Bank Sta=499.5,514.5
XS Rating Curve= 0 ,0
Exp/Cntr=0.3,0.1

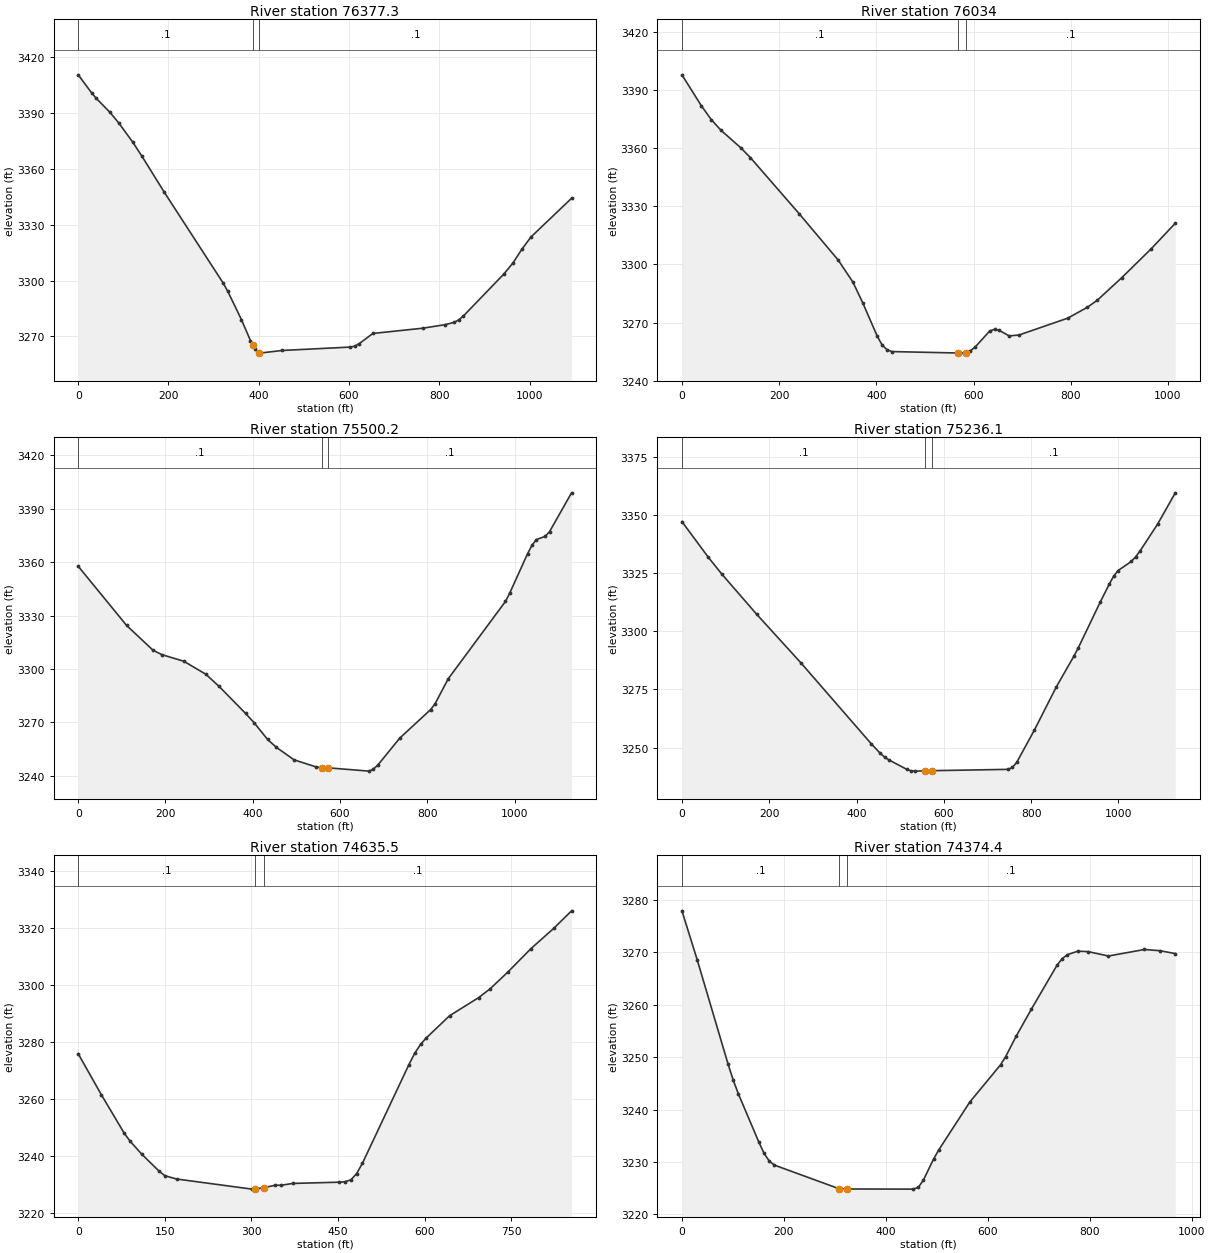
Type RM Length L Ch R = 1 ,76377.3 ,346.1,343.3,340.5
XS GIS Cut Line= 3
     2086763.558      395057.063     2087242.527      395625.129
     2087287.893      395972.078
#Sta/Elev= 30
       0 3410.52    30.1 3400.71    40.2 3397.83    70.3  3390.4    90.4  3384.5
   120.5 3374.46   140.6 3367.01   190.8  3347.4   321.3 3298.59   331.4 3294.17
   361.5 3279.06   381.6 3267.75   386.6 3265.36   391.6 3262.97   401.6 3261.01
   451.8 3262.44   602.5 3264.26   612.5 3264.74   622.6  3266.1   652.7 3271.58
     763 3274.39     813 3276.31     833 3277.54     843 3278.88     853 3280.88
     943 3303.53     963 3309.43     983 3316.87    1003 3323.41  1092.9  3344.2
#Mann= 3 , 0 , 0
       0      .1       0   386.6    .045       0   401.6      .1       0
Bank Sta=386.6,401.6
XS Rating Curve= 0 ,0
Exp/Cntr=0.3,0.1

Type RM Length L Ch R = 1 ,76034   ,527.7,533.7,539.7
XS GIS Cut Line= 2
     2086429.793      395250.825     2087166.897      395948.837
#Sta/Elev= 30
       0 3397.89    40.2 3381.81    60.3 3374.82    80.4 3369.24   120.6 3360.34
   140.7  3355.2   241.2 3326.21   321.6 3302.26   351.8  3290.9   371.9 3280.29
     402 3262.92   412.1  3258.4   422.1 3255.99   432.2 3255.04     569  3254.3
   572.9 3254.24     584 3254.48     593 3255.34   603.1 3257.31   633.2 3265.63
   643.3 3266.55   653.3 3265.92   673.4 3263.14   693.5 3263.59     794  3272.3
   834.2  3277.9   854.3 3281.46   904.6 3293.08   964.9 3307.92  1015.2 3321.26
#Mann= 3 , 0 , 0
       0      .1       0     569    .045       0     584      .1       0
Bank Sta=569,584
XS Rating Curve= 0 ,0
Exp/Cntr=0.3,0.1

Type RM Length L Ch R = 1 ,75500.2 ,264.8,264,261.7
XS GIS Cut Line= 2
     2086210.862      395479.255     2086802.442      396442.638
#Sta/Elev= 30
       0 3357.63     111 3324.41   171.6 3310.49   191.8 3308.05   242.2 3304.32
   292.7 3297.02     323  3290.2   383.6 3275.07   403.8 3269.66     434 3260.46
   454.2 3256.04   494.6 3249.05   545.1 3245.07   557.8 3244.64   572.8 3244.56
   666.2 3242.71   676.3  3243.8   686.4 3246.06   736.9 3261.25   807.5 3277.22
   817.6 3280.44   847.9 3294.52   979.1 3337.91   989.2 3342.78  1029.6 3364.58
  1039.7 3369.33  1049.8 3372.58    1070 3374.38    1080 3377.02  1130.5 3398.82
#Mann= 3 , 0 , 0
       0      .1       0   557.8    .045       0   572.8      .1       0
Bank Sta=557.8,572.8
XS Rating Curve= 0 ,0
Exp/Cntr=0.3,0.1

Type RM Length L Ch R = 1 ,75236.1 ,598.9,600.5,601.3
XS GIS Cut Line= 2
     2086068.946      395542.102     2086508.999       396583.46
#Sta/Elev= 30
       0 3347.07    60.6 3331.72    90.8 3324.66   171.6 3307.22   272.5 3286.45
     434 3251.64   454.2 3247.65   464.3 3245.95   474.4 3244.75   514.8 3240.74
   524.9 3240.09     535 3239.94   557.8 3240.07   572.8 3240.13     747  3240.7
     757 3241.52   767.1 3243.68   807.5 3257.53     858 3276.15   898.4 3289.37
   908.4 3292.95   958.9 3312.67   979.1  3320.2   989.2 3323.61   999.3 3326.05
  1029.6 3329.95  1039.7 3331.95  1049.8 3334.47  1090.1 3346.03  1130.5 3359.43
#Mann= 3 , 0 , 0
       0      .1       0   557.8    .045       0   572.8      .1       0
Bank Sta=557.8,572.8
XS Rating Curve= 0 ,0
Exp/Cntr=0.3,0.1

Type RM Length L Ch R = 1 ,74635.5 ,246,261,276.3
XS GIS Cut Line= 3
     2085725.171      396013.202     2085745.733      396121.153
     2086162.116      396738.017
#Sta/Elev= 30
       0 3275.91      40 3261.54    79.9  3247.9    89.9 3245.18   109.9 3240.64
   140.1 3234.63   150.1 3233.04   170.2 3231.89     301 3228.33   306.9 3228.41
   321.9 3228.86   341.2 3229.71   351.3 3229.69   371.4 3230.33   451.8 3230.77
   461.9 3230.93     472 3231.59     482 3233.78   492.1 3237.45   572.5 3272.08
   582.6 3276.09   592.6 3279.18   602.7  3281.5   642.9 3289.27   693.2 3295.64
   713.3 3298.78   743.5 3304.56   783.7 3312.85     824 3320.13   854.1 3326.15
#Mann= 3 , 0 , 0
       0      .1       0   306.9    .045       0   321.9      .1       0
Bank Sta=306.9,321.9
XS Rating Curve= 0 ,0
Exp/Cntr=0.3,0.1

Type RM Length L Ch R = 1 ,74374.4 ,256.2,258.2,260.2
XS GIS Cut Line= 2
     2085684.047      396008.062     2085570.955      396969.341
#Sta/Elev= 30
       0 3277.95    30.2 3268.52    90.7 3248.63   100.8 3245.59   110.9 3242.97
   151.2 3233.74   161.3 3231.64   171.4 3230.18   181.5 3229.42   308.5 3224.91
   323.5 3224.87   453.7 3224.84   463.8 3225.17   473.9 3226.61     494 3230.64
   504.1 3232.36   564.6 3241.44   625.1 3248.57   635.2 3250.14   655.4 3253.97
   685.6 3259.19     736 3267.59   746.1 3268.84   756.2 3269.58   776.3 3270.24
   796.5 3270.17   836.8 3269.33   907.4 3270.57   937.7 3270.34   967.9 3269.79
#Mann= 3 , 0 , 0
       0      .1       0   308.5    .045       0   323.5      .1       0
Bank Sta=308.5,323.5
XS Rating Curve= 0 ,0
Exp/Cntr=0.3,0.1

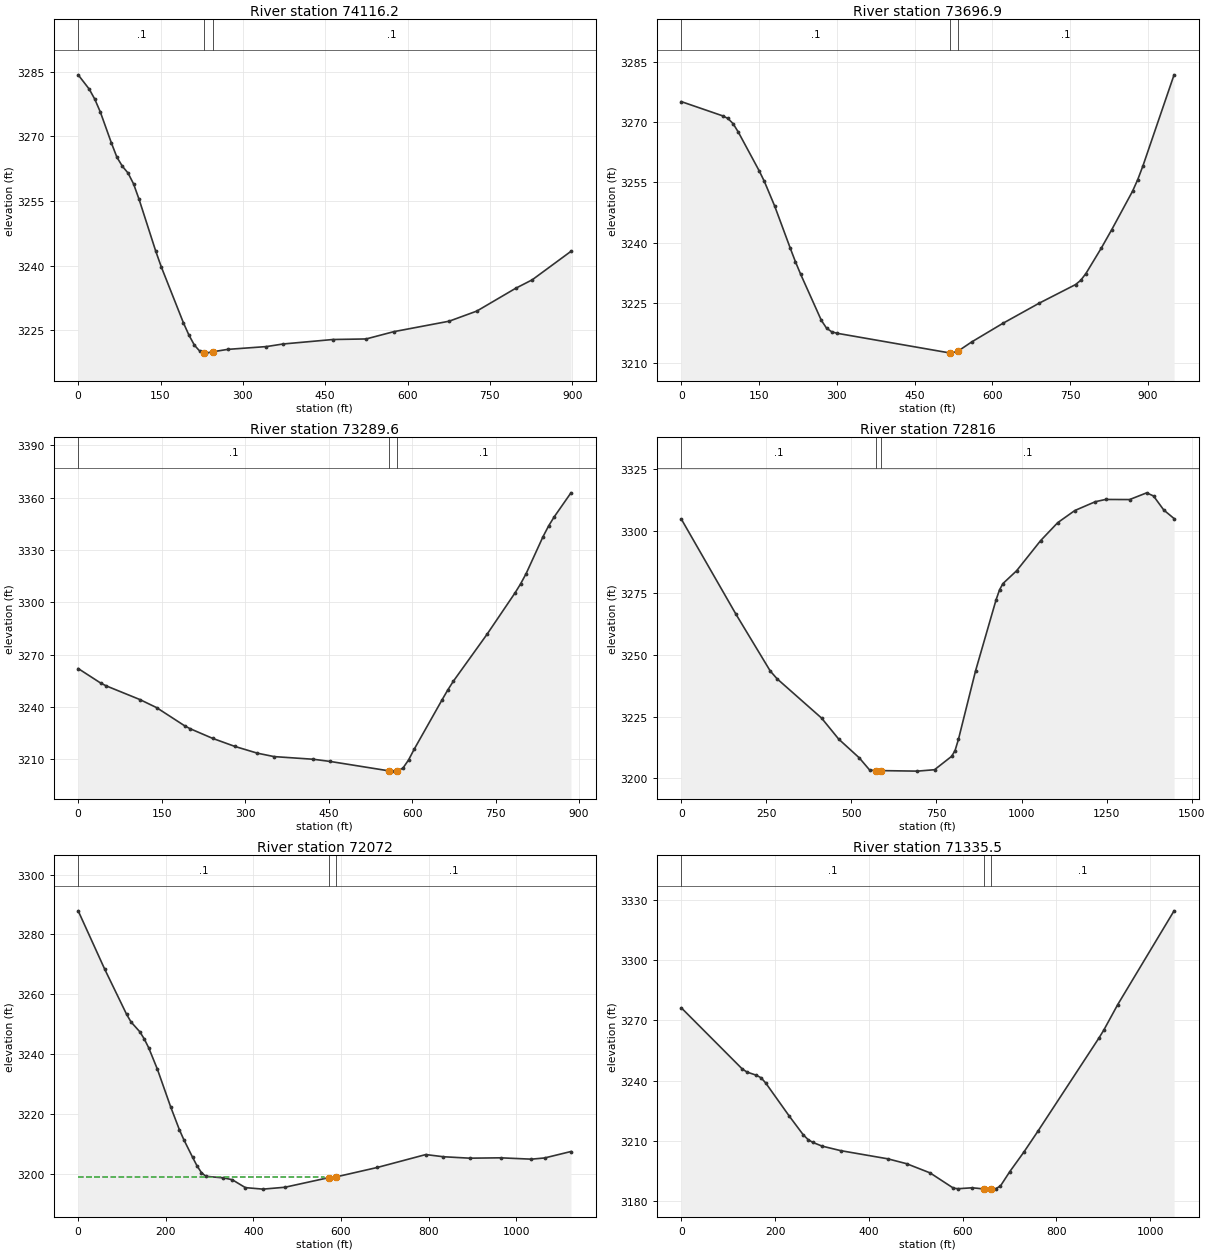
Type RM Length L Ch R = 1 ,74116.2 ,422,419.3,428.9
XS GIS Cut Line= 2
     2085447.582      395982.359     2085324.209      396871.671
#Sta/Elev= 30
       0 3284.27    20.2 3280.94    30.3 3278.61    40.4 3275.63    60.5 3268.47
    70.6 3265.14    80.7 3263.02    90.8 3261.49   100.9 3258.96     111 3255.36
   141.2  3243.4   151.3 3239.74   191.7 3226.74   201.8 3223.87   211.8 3221.53
   221.9  3220.1   230.1 3219.77     232 3219.69   245.1    3220   272.4 3220.56
     343 3221.21   373.2 3221.81     464 3222.85   524.6 3222.98     575 3224.67
   675.9  3227.1   726.3 3229.45     797 3234.73   827.2  3236.7   897.8 3243.31
#Mann= 3 , 0 , 0
       0      .1       0   230.1    .045       0   245.1      .1       0
Bank Sta=230.1,245.1
XS Rating Curve= 0 ,0
Exp/Cntr=0.3,0.1

Type RM Length L Ch R = 1 ,73696.9 ,398.5,407.4,416.3
XS GIS Cut Line= 2
     2085077.464      395828.143     2084984.934      396774.001
#Sta/Elev= 30
       0 3275.14      80 3271.58      90 3270.93     100 3269.63     110 3267.53
   150.1 3257.91   160.1 3255.27   180.1  3249.1   210.1 3238.61   220.1 3235.22
   230.1 3232.12   270.1 3220.59   280.1 3218.65   290.1 3217.73   300.1 3217.37
   518.5 3212.44   520.2 3212.41   533.5 3212.89   560.2 3215.21   620.2 3219.84
   690.3 3224.87   760.3  3229.5   770.3 3230.56   780.3 3232.25   810.3 3238.66
   830.3 3243.23   870.3 3252.79   880.4 3255.71   890.4 3259.13   950.4 3281.82
#Mann= 3 , 0 , 0
       0      .1       0   518.5    .045       0   533.5      .1       0
Bank Sta=518.5,533.5
XS Rating Curve= 0 ,0
Exp/Cntr=0.3,0.1

Type RM Length L Ch R = 1 ,73289.6 ,473.4,473.6,473.9
XS GIS Cut Line= 2
     2084902.686      395761.316     2084486.302      396542.677
#Sta/Elev= 30
       0 3262.01    40.2 3253.72    50.3 3252.07   110.7 3244.24   140.9 3239.59
   191.2 3229.19   201.2 3227.49   241.5 3221.97   281.7 3217.32     322 3213.46
   352.1  3211.5   422.6 3209.97   452.8 3208.72   558.7 3203.31   563.4 3203.17
   573.7 3203.27   583.6 3204.94   593.6 3209.57   603.7 3215.72     654 3244.16
     664 3249.67   674.1 3254.74   734.5  3281.6   784.8 3305.32   794.8 3310.49
   804.9 3316.47   835.1 3337.56   845.1  3343.7   855.2 3348.94   885.4 3362.77
#Mann= 3 , 0 , 0
       0      .1       0   558.7    .045       0   573.7      .1       0
Bank Sta=558.7,573.7
XS Rating Curve= 0 ,0
Exp/Cntr=0.3,0.1

Type RM Length L Ch R = 1 ,72816   ,727.8,744.1,749.6
XS GIS Cut Line= 2
     2084774.032      395406.525     2084049.301      396660.495
#Sta/Elev= 30
       0 3304.89   160.9 3266.35   261.5 3243.43   281.6 3240.29   412.4  3224.4
   462.7  3215.9     523 3208.34   553.2 3203.47   572.4 3203.06   587.4 3203.17
     694 3202.96   744.3 3203.53   794.6 3208.95   804.6 3211.28   814.7 3215.87
     865 3243.57   925.3 3272.28   935.4 3276.27   945.4  3278.8   985.7    3284
  1056.1 3296.16  1106.4 3303.43  1156.7 3308.33    1217  3311.9  1247.2  3312.8
  1317.6 3312.76  1367.9 3315.48    1388 3314.19  1418.2 3308.51  1448.3 3305.08
#Mann= 3 , 0 , 0
       0      .1       0   572.4    .045       0   587.4      .1       0
Bank Sta=572.4,587.4
XS Rating Curve= 0 ,0
Exp/Cntr=0.3,0.1

Type RM Length L Ch R = 1 ,72072   ,720.2,736.1,750.4
XS GIS Cut Line= 2
     2084159.989      395232.125     2083559.171      396183.634
#Sta/Elev= 30
       0 3287.91    60.3 3268.48   110.5 3253.32   120.6 3250.76   140.7 3247.47
   150.7 3245.12   160.8 3242.18   180.9 3234.94     211 3222.43   231.1 3214.72
   241.1 3211.42   261.2 3205.51   271.3 3202.65   281.3  3200.4   291.4 3199.13
   331.6  3198.6   351.7    3198   381.8 3195.34     422 3194.84   472.2 3195.47
   573.23198.711   588.23198.907   683.2 3202.09   793.8  3206.4     834 3205.67
   894.2 3205.19   964.6 3205.31  1034.9 3204.86    1065 3205.26  1125.3 3207.42
#Mann= 3 , 0 , 0
       0      .1       0   573.2    .045       0   588.2      .1       0
#XS Ineff= 2 , 0
           561.2 3199.04
Permanent Ineff=
       F       F
Bank Sta=573.2,588.2
XS Rating Curve= 0 ,0
Exp/Cntr=0.3,0.1

Type RM Length L Ch R = 1 ,71335.5 ,452.8,455.5,458.1
XS GIS Cut Line= 2
     2083972.441      395033.522     2082990.581      395408.668
#Sta/Elev= 30
       0 3276.33   130.1 3245.78   140.1 3244.26   160.2 3242.65   170.2 3241.39
   180.2 3238.75   230.2  3222.3   260.3 3212.88   270.3 3210.58   280.3 3209.16
   300.3 3207.28   340.4    3205   440.5 3200.94   480.5 3198.51   530.6 3193.92
   580.6 3186.28   590.6 3186.02   620.6 3186.48   645.83185.894   660.7 3185.81
   660.83185.812   670.7 3186.03   680.7 3187.36   700.7 3194.55   730.8 3204.33
   760.8 3214.77   890.9 3261.26   900.9 3265.07     931 3277.96  1051.1 3324.73
#Mann= 3 , 0 , 0
       0      .1       0   645.8    .045       0   660.8      .1       0
Bank Sta=645.8,660.8
XS Rating Curve= 0 ,0
Exp/Cntr=0.3,0.1