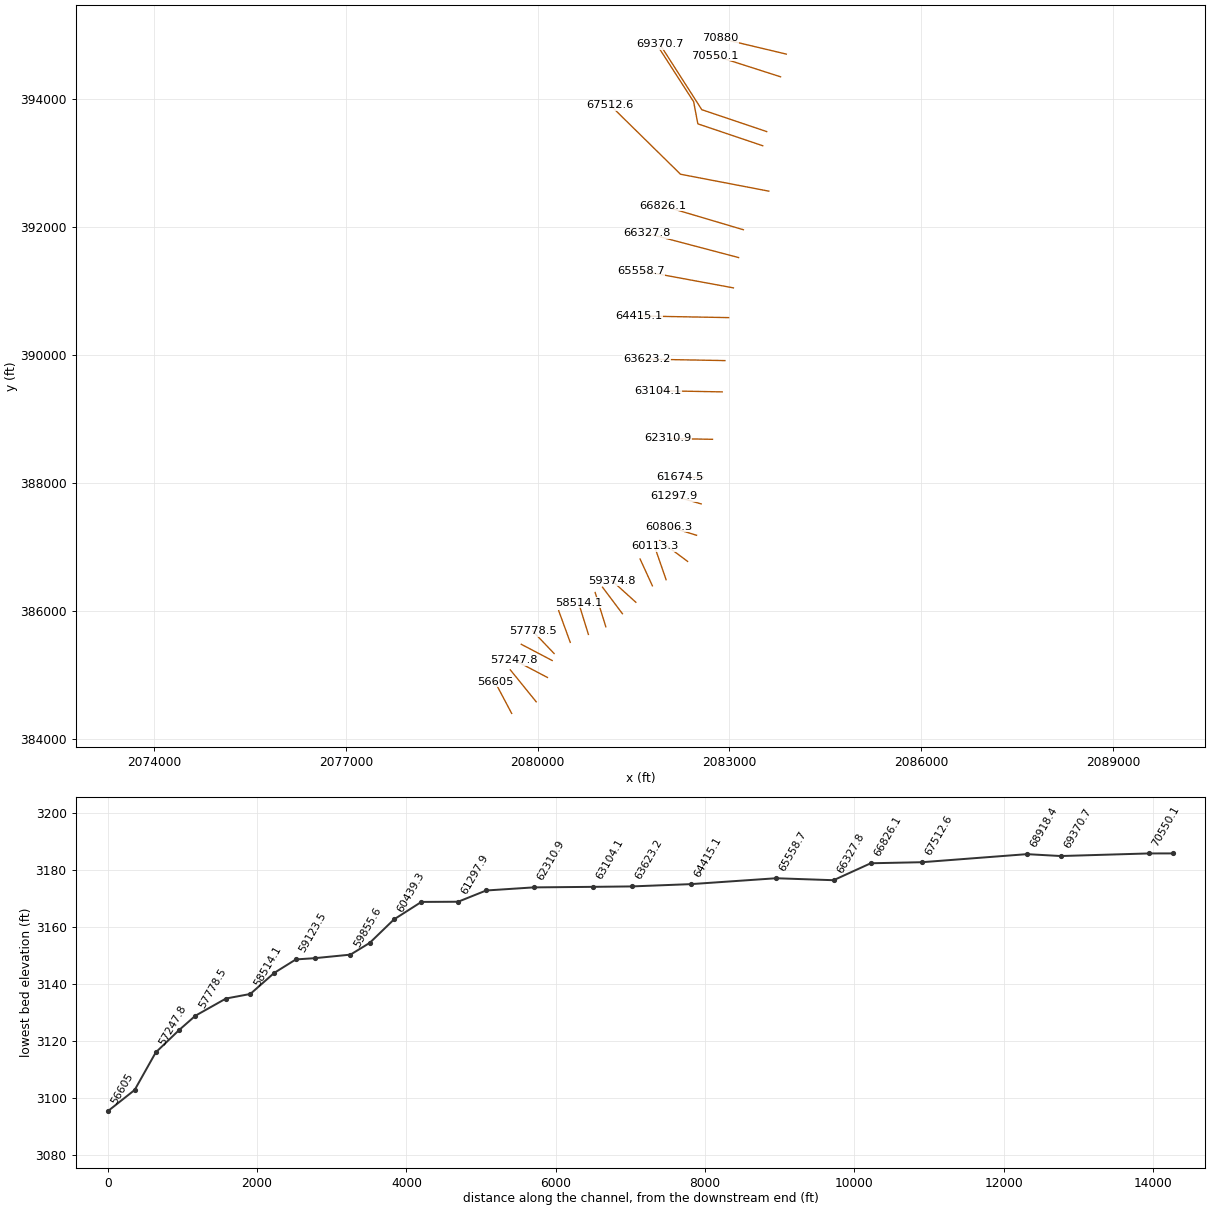
HEC-RAS study BigClearCk.prj: BigClearCk

--- BigClearCk.g01 (geometry) --- (continued)

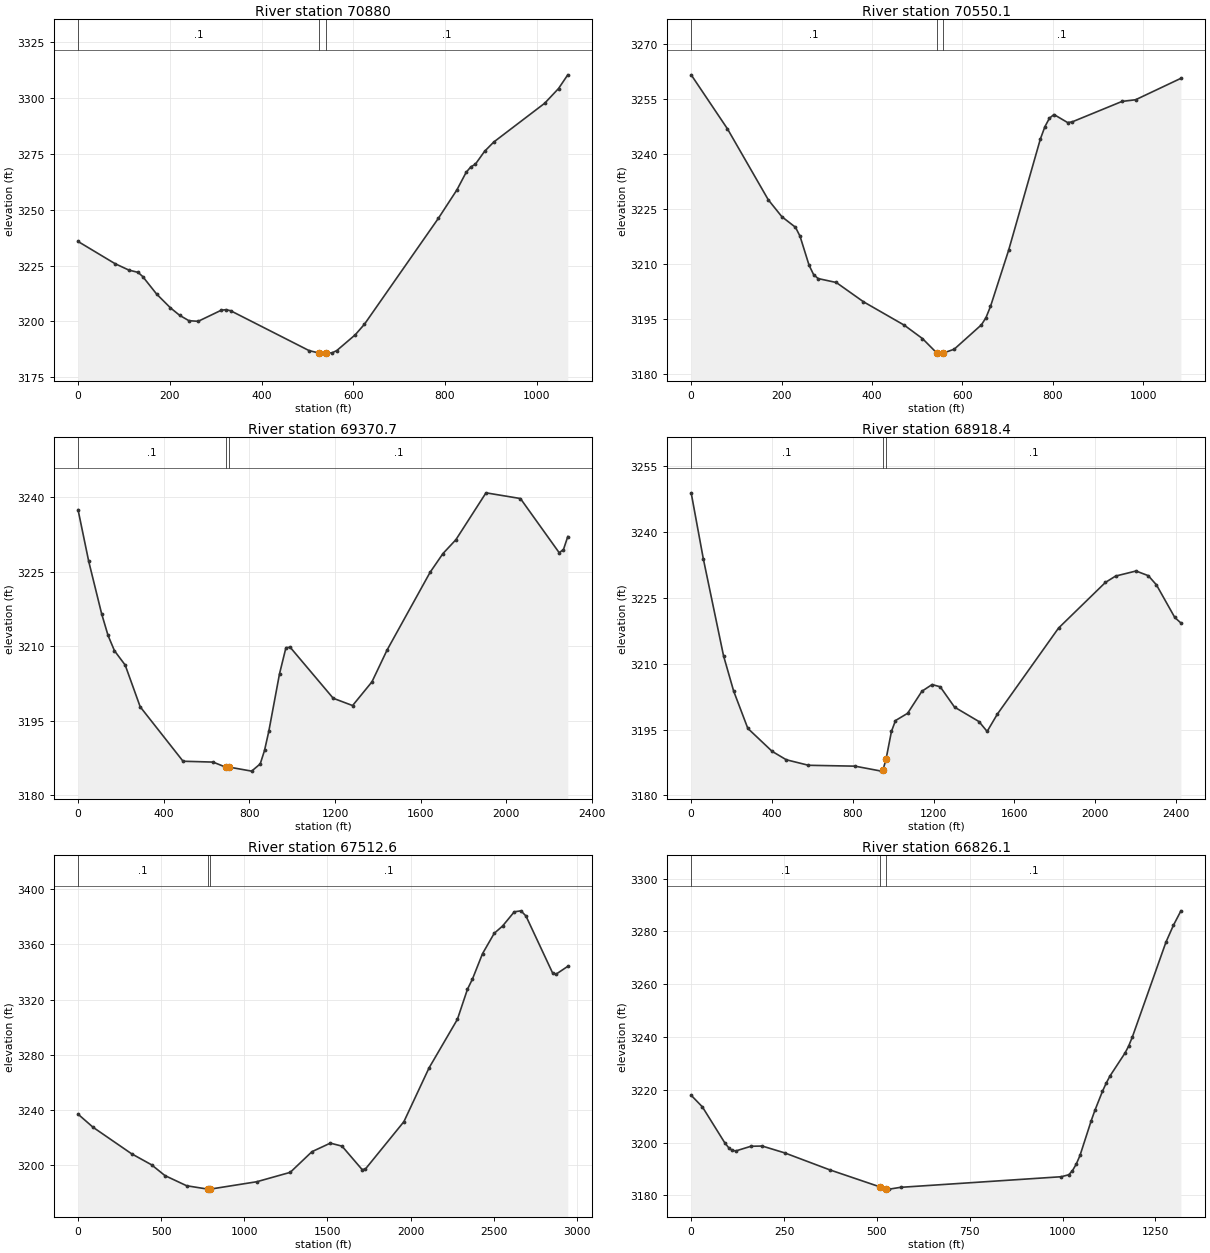
Type RM Length L Ch R = 1 ,70880   ,332.4,330,327.6
XS GIS Cut Line= 2
     2083889.738      394707.064     2082851.004      394953.527
#Sta/Elev= 30
       0 3235.78    80.6 3225.85   110.8 3222.97   130.9 3221.94     141 3220.08
   171.2 3212.27   201.4 3206.08   221.6 3202.71   241.7 3200.32   261.9 3200.04
   312.2    3205   322.3 3205.24   332.4  3204.8   503.6 3186.94   525.5 3185.82
   540.5  3185.8   553.9 3185.94     564 3186.94   604.3 3194.01   624.4 3198.75
   785.6 3246.17   825.9 3258.86     846  3266.7   856.1 3269.14   866.1 3270.35
   886.3 3276.14   906.4 3280.31  1017.2 3297.63  1047.4 3304.22  1067.6 3310.36
#Mann= 3 , 0 , 0
       0      .1       0   525.5    .045       0   540.5      .1       0
Bank Sta=525.5,540.5
XS Rating Curve= 0 ,0
Exp/Cntr=0.3,0.1

Type RM Length L Ch R = 1 ,70550.1 ,1180.2,1179.4,1177.1
XS GIS Cut Line= 2
     2083799.781       394351.97     2082767.909      394682.567
#Sta/Elev= 30
       0 3261.71    80.3 3246.97   170.6 3227.62   200.7    3223   230.8 3220.12
   240.8 3217.69   260.8 3209.78   270.9  3207.2   280.9 3206.13     321 3205.06
   381.2  3199.8   471.5 3193.41   511.7 3189.76   543.1 3185.87   551.8 3185.79
   558.1 3185.82   581.9 3186.86   642.1 3193.51   652.1 3195.44   662.2 3198.53
   702.3 3213.85   772.5 3244.19   782.6 3247.57   792.6 3249.88   802.6 3250.88
   832.7  3248.7   842.8 3248.87   953.1 3254.45   983.2 3254.91  1083.5 3260.76
#Mann= 3 , 0 , 0
       0      .1       0   543.1    .045       0   558.1      .1       0
Bank Sta=543.1,558.1
XS Rating Curve= 0 ,0
Exp/Cntr=0.3,0.1

Type RM Length L Ch R = 1 ,69370.7 ,454.8,452.3,485.2
XS GIS Cut Line= 3
     2083582.701      393495.077     2082567.762      393837.466
     2081911.809      394861.393
#Sta/Elev= 30
       0 3237.51      50 3227.09   110.1 3216.58   140.2 3212.19   170.2 3209.11
   220.2 3206.23   290.3 3197.83   490.5 3186.87   630.7  3186.7   691.8 3185.64
   706.8 3185.68   810.9 3184.88   850.9 3186.34   870.9 3189.04   890.9 3192.89
     941 3204.48     971 3209.74     991  3209.8  1191.7 3199.55  1282.2 3198.08
  1372.6 3202.85    1443 3209.23    1644 3224.89  1704.3 3228.68  1764.6 3231.46
  1905.3  3240.9  2066.1 3239.75    2247 3228.85    2267 3229.48  2287.2  3232.1
#Mann= 3 , 0 , 0
       0      .1       0   691.8    .045       0   706.8      .1       0
Bank Sta=691.8,706.8
XS Rating Curve= 0 ,0
Exp/Cntr=0.3,0.1

Type RM Length L Ch R = 1 ,68918.4 ,1403.5,1405.7,1408.2
XS GIS Cut Line= 4
     2083521.151      393273.494     2082506.211      393615.883
     2082439.899      393962.678     2081898.383       394802.58
#Sta/Elev= 30
       0 3248.87    60.1 3233.86   160.2 3211.78   210.2 3203.76   280.3 3195.27
   400.4 3190.05   470.5 3188.13   580.6 3186.87   810.9 3186.67     941 3185.54
   949.3 3185.83   964.3 3188.25     991 3194.56  1011.1 3197.05  1071.1  3198.7
  1141.8 3203.72  1192.2 3205.24  1232.5 3204.73  1303.2 3200.11  1424.2 3196.82
  1464.6 3194.57  1515.1 3198.51  1817.9 3218.09  2050.1 3228.49  2100.5 3229.93
  2201.5 3231.08    2262 3230.02  2302.4 3227.93  2393.3  3220.5  2423.6 3219.25
#Mann= 3 , 0 , 0
       0      .1       0   949.3    .045       0   964.3      .1       0
Bank Sta=949.3,964.3
XS Rating Curve= 0 ,0
Exp/Cntr=0.3,0.1

Type RM Length L Ch R = 1 ,67512.6 ,690.3,686.3,682.7
XS GIS Cut Line= 3
     2083616.758      392563.001     2082235.091      392827.713
     2081137.504       393905.93
#Sta/Elev= 30
       0 3237.02    90.4 3227.51   321.6 3208.36   442.1 3200.34   522.5 3192.54
   653.2 3185.16   779.9 3182.72   783.8 3182.71   794.9 3182.71  1075.2 3188.07
  1276.2 3194.86  1406.8 3209.83  1517.4 3216.03  1587.8 3213.83  1708.5 3196.87
  1728.6 3197.31  1959.9 3231.59  2110.7 3270.43  2281.7 3305.74    2342 3327.48
  2372.2 3334.91  2432.5 3353.24  2502.9 3367.98  2553.2 3373.26  2623.6 3383.56
  2663.8 3384.28    2694 3380.52  2854.9 3339.06    2875 3338.41  2945.4 3344.08
#Mann= 3 , 0 , 0
       0      .1       0   779.9    .045       0   794.9      .1       0
Bank Sta=779.9,794.9
XS Rating Curve= 0 ,0
Exp/Cntr=0.3,0.1

Type RM Length L Ch R = 1 ,66826.1 ,495.3,498.3,500.4
XS GIS Cut Line= 2
      2083218.39      391959.438     2081954.012      392334.275
#Sta/Elev= 30
       0  3217.9    30.2 3213.51    90.6 3199.87   100.7 3198.09   110.7 3196.98
   120.8 3196.84   161.1 3198.59   191.3 3198.67   251.7 3196.08   372.5 3189.68
   509.4 3183.14   524.4 3182.37   533.6 3182.34   563.8 3183.02   996.6 3187.04
  1016.8 3187.79  1026.8 3189.35  1036.9 3191.82    1047 3195.09  1077.2 3208.26
  1087.2 3212.21  1107.4 3219.38  1117.4 3222.45  1127.5 3225.16  1167.8 3233.82
  1177.8 3236.48  1187.9 3239.96  1278.5 3275.95  1298.6 3282.34  1318.8 3287.81
#Mann= 3 , 0 , 0
       0      .1       0   509.4    .045       0   524.4      .1       0
Bank Sta=509.4,524.4
XS Rating Curve= 0 ,0
Exp/Cntr=0.3,0.1

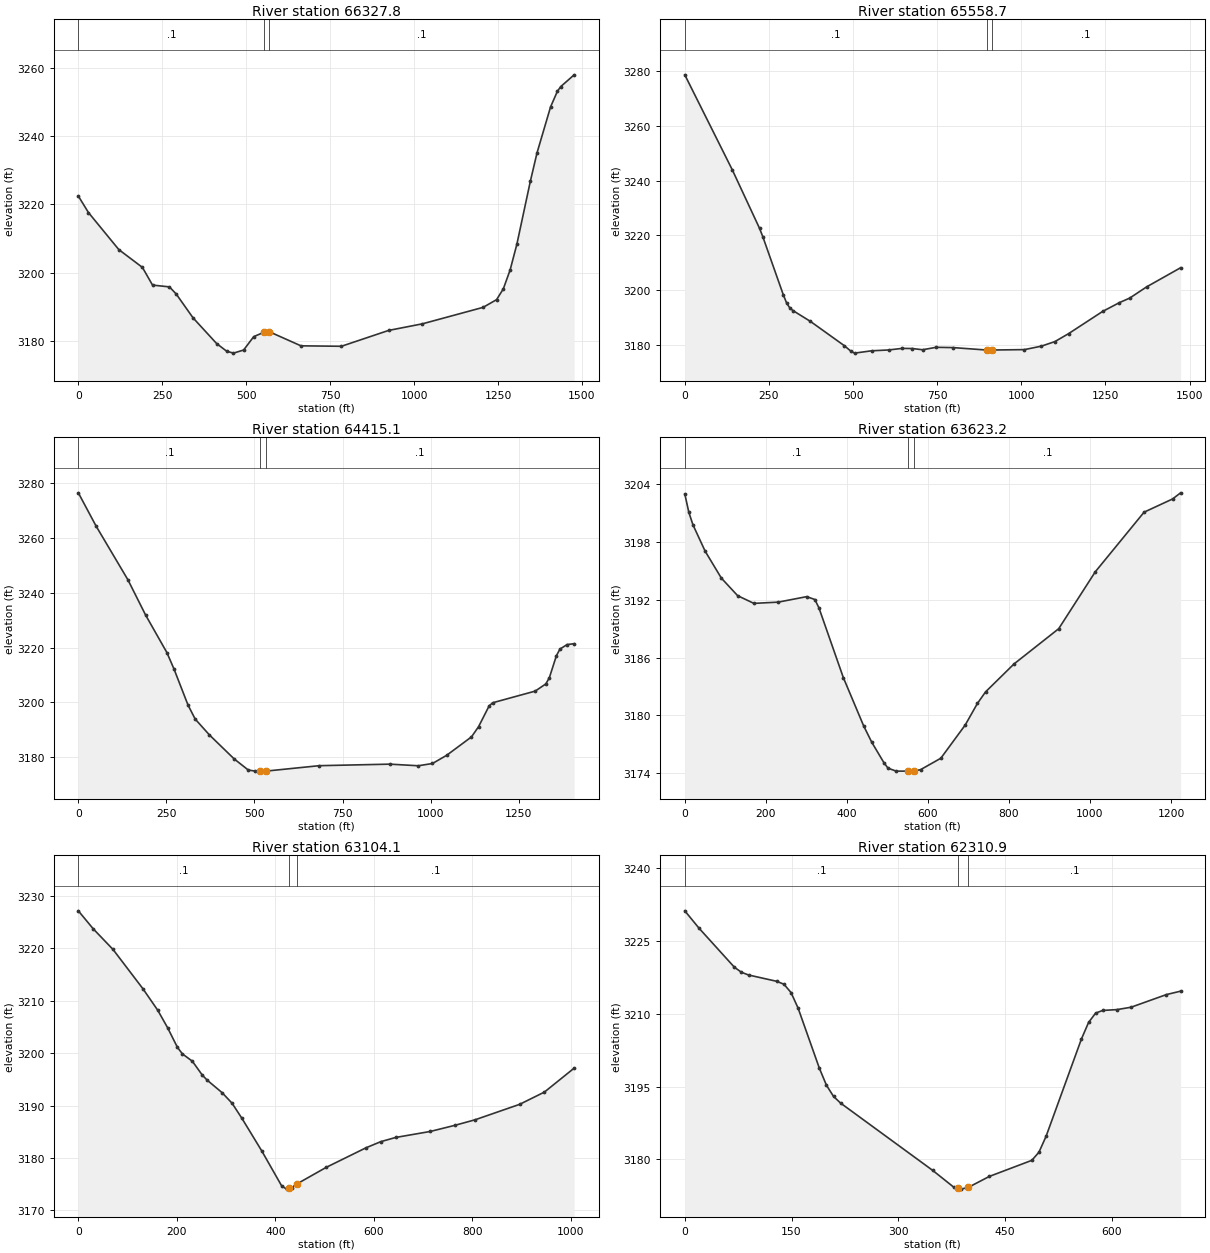
Type RM Length L Ch R = 1 ,66327.8 ,770,769,767.3
XS GIS Cut Line= 2
      2083143.64      391524.228     2081715.608      391900.813
#Sta/Elev= 30
       0 3222.44    30.1 3217.61   120.6 3206.74   190.9 3201.52     221 3196.34
   271.3 3195.81   291.4 3193.74   341.6 3186.74   411.9  3179.2     442 3176.94
   462.1 3176.39   492.3  3177.3   522.4 3181.22   553.8 3182.55   568.8 3182.66
   663.1 3178.53   783.6  3178.4   924.3 3183.05  1024.8 3184.98  1205.6 3189.81
  1245.8 3192.07  1265.9 3195.25    1286 3200.75  1306.1 3208.28  1346.2 3226.73
  1366.3 3235.14  1406.5 3248.56  1426.6  3253.1  1436.7 3254.52  1476.8 3257.98
#Mann= 3 , 0 , 0
       0      .1       0   553.8    .045       0   568.8      .1       0
Bank Sta=553.8,568.8
XS Rating Curve= 0 ,0
Exp/Cntr=0.3,0.1

Type RM Length L Ch R = 1 ,65558.7 ,1131.8,1143.1,1149.3
XS GIS Cut Line= 2
     2083062.196      391050.045     2081613.403      391317.441
#Sta/Elev= 30
       0 3278.56   141.3 3243.87     222 3222.61   232.1 3219.43   292.6 3198.38
   302.7 3195.32   312.8 3193.42   322.9 3192.48   373.4 3188.64   474.3 3179.77
   494.4  3177.7   504.5 3177.08     555 3177.93   605.4 3178.23   645.8 3178.81
   676.1 3178.76   706.4 3178.31   746.7  3179.2   797.2  3179.1   896.5 3178.21
   911.5 3178.21  1009.1 3178.36  1059.5 3179.62  1099.9  3181.3  1140.3 3184.18
  1241.2 3192.26  1291.6 3195.51  1321.9 3197.14  1372.4 3201.25  1473.3 3208.22
#Mann= 3 , 0 , 0
       0      .1       0   896.5    .045       0   911.5      .1       0
Bank Sta=896.5,911.5
XS Rating Curve= 0 ,0
Exp/Cntr=0.3,0.1

Type RM Length L Ch R = 1 ,64415.1 ,792.2,791.2,792.3
XS GIS Cut Line= 2
     2082987.396      390584.793     2081580.248      390610.747
#Sta/Elev= 30
       0 3276.32    50.3 3264.24   140.7 3244.67     191 3231.82   251.3 3218.19
   271.4 3212.23   311.6 3198.98   331.7 3193.96     372  3188.2   442.3 3179.46
   482.5  3175.4   502.6 3175.01     517 3175.01     532 3175.01   683.6 3176.99
   884.6 3177.55   965.1 3176.96  1005.3 3177.79  1045.5 3180.77  1115.9 3187.47
    1136 3191.17  1166.1 3198.77  1176.2  3199.9  1296.8 3204.14    1327 3206.76
    1337 3209.02  1357.1 3217.06  1367.2 3219.46  1387.3 3221.08  1407.4  3221.4
#Mann= 3 , 0 , 0
       0      .1       0     517    .045       0     532      .1       0
Bank Sta=517,532
XS Rating Curve= 0 ,0
Exp/Cntr=0.3,0.1

Type RM Length L Ch R = 1 ,63623.2 ,515.1,519.2,519.5
XS GIS Cut Line= 2
     2082929.677      389912.545     2081706.142      389935.113
#Sta/Elev= 30
       0 3202.99      10 3201.08    20.1 3199.79    50.2 3197.05    90.3 3194.25
   130.4 3192.43   170.5 3191.63   230.7 3191.76   300.9 3192.33     321 3192.03
     331 3191.17   391.2 3183.93   441.4 3178.91   461.4 3177.21   491.5 3175.08
   501.5 3174.52   521.6 3174.21   550.4 3174.21   565.4 3174.22   581.8 3174.36
   631.9 3175.55   692.1    3179   722.2 3181.24   742.3 3182.44   812.5 3185.34
   922.8    3189  1013.1 3194.91  1133.5  3201.1  1203.7 3202.47  1223.7 3203.11
#Mann= 3 , 0 , 0
       0      .1       0   550.4    .045       0   565.4      .1       0
Bank Sta=550.4,565.4
XS Rating Curve= 0 ,0
Exp/Cntr=0.3,0.1

Type RM Length L Ch R = 1 ,63104.1 ,793,793.2,793.3
XS GIS Cut Line= 2
     2082887.654      389423.101     2081881.135      389441.665
#Sta/Elev= 30
       0 3227.17    30.2 3223.74    70.5 3219.79   130.9 3212.33   161.1 3208.22
   181.2 3204.87   201.3  3201.1   211.4 3199.86   231.5 3198.47   251.7 3195.82
   261.7 3194.85   291.9 3192.47   312.1 3190.46   332.2 3187.56   372.5 3181.34
   412.7  3174.7   422.8 3174.06     428  3174.2   432.9 3174.33     443 3175.01
   503.4 3178.22   583.9 3181.94   614.1 3183.12   644.3 3183.92   714.8 3185.07
   765.1 3186.25   805.4 3187.29     896 3190.24   946.3 3192.58  1006.7 3197.15
#Mann= 3 , 0 , 0
       0      .1       0     428    .045       0     443      .1       0
Bank Sta=428,443
XS Rating Curve= 0 ,0
Exp/Cntr=0.3,0.1

Type RM Length L Ch R = 1 ,62310.9 ,636.4,636.4,636.4
XS GIS Cut Line= 2
     2082735.543      388681.079      2082038.77      388693.931
#Sta/Elev= 30
       0 3231.17    19.9 3227.61    69.7 3219.56    79.6 3218.52    89.6 3217.96
   129.4 3216.65   139.4 3216.05   149.3 3214.35   159.3 3211.12   189.2 3198.74
   199.1 3195.26   209.1 3192.95     219 3191.58   348.4 3177.73   378.3 3174.24
   383.6 3174.04   388.3 3173.87   398.6 3174.24   428.1 3176.49   487.8  3179.8
   497.8 3181.48   507.7 3184.71   557.5 3204.79   567.5 3208.18   577.4 3210.11
   587.4 3210.66   607.3 3210.83   627.2 3211.32     677 3213.93   696.9 3214.63
#Mann= 3 , 0 , 0
       0      .1       0   383.6    .045       0   398.6      .1       0
Bank Sta=383.6,398.6
XS Rating Curve= 0 ,0
Exp/Cntr=0.3,0.1

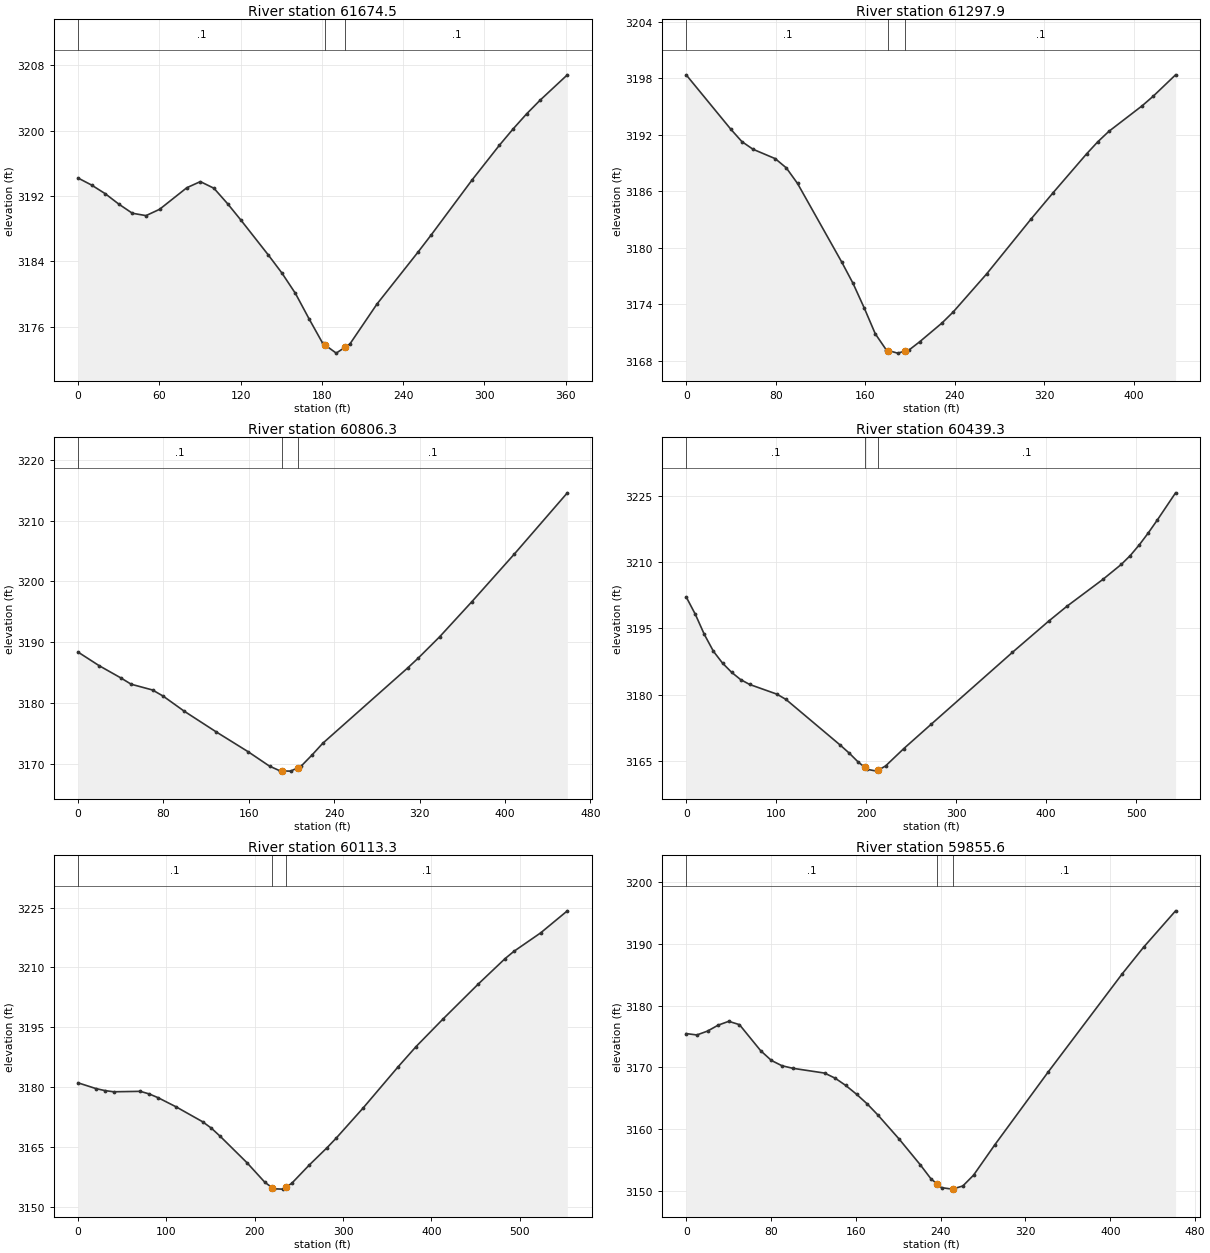
Type RM Length L Ch R = 1 ,61674.5 ,381.4,375.6,369.8
XS GIS Cut Line= 2
     2082589.348      388083.674      2082228.22      388090.334
#Sta/Elev= 30
       0  3194.2      10 3193.34    20.1 3192.28    30.1 3191.01    40.1 3189.89
    50.2  3189.6    60.2 3190.37    80.3 3193.01    90.3 3193.76   100.3 3192.95
   110.4 3191.06   120.4 3189.02   140.5 3184.78   150.5 3182.58   160.5 3180.08
   170.6 3176.96   180.6 3173.99   182.4 3173.77   190.6 3172.78   197.4 3173.53
   200.7  3173.9   220.7 3178.79   250.8  3185.1   260.9 3187.28     291 3193.99
     311  3198.2   321.1 3200.19   331.1 3202.04   341.1 3203.72   361.2 3206.82
#Mann= 3 , 0 , 0
       0      .1       0   182.4    .045       0   197.4      .1       0
Bank Sta=182.4,197.4
XS Rating Curve= 0 ,0
Exp/Cntr=0.3,0.1

Type RM Length L Ch R = 1 ,61297.9 ,492.1,491.5,491
XS GIS Cut Line= 2
     2082558.674      387670.478     2082138.818      387792.328
#Sta/Elev= 28
       0 3198.37    39.7 3192.62    49.7 3191.29    59.6 3190.48    79.5 3189.48
    89.4  3188.5    99.4 3186.85   139.1 3178.46     149 3176.24     159 3173.63
   168.9 3170.88   178.8 3169.16   180.6  3169.1   188.8 3168.83   195.6 3169.04
   198.7 3169.13   208.6 3170.04   228.5 3172.03   238.5  3173.2   268.3 3177.23
     308 3183.06   327.9 3185.88   357.7 3189.99   367.6 3191.26   377.6 3192.38
   407.4  3195.1   417.3 3196.12   437.2 3198.38
#Mann= 3 , 0 , 0
       0      .1       0   180.6    .045       0   195.6      .1       0
Bank Sta=180.6,195.6
XS Rating Curve= 0 ,0
Exp/Cntr=0.3,0.1

Type RM Length L Ch R = 1 ,60806.3 ,374.2,366.5,358.8
XS GIS Cut Line= 2
     2082485.833      387180.052     2082048.216      387316.511
#Sta/Elev= 23
       0 3188.36    19.9 3186.11    39.9 3184.13    49.8 3183.07    69.8 3182.12
    79.7 3181.12    99.6 3178.62   129.6 3175.21   159.4 3171.96   179.4 3169.59
   189.3 3168.81   191.1  3168.8   199.3 3168.77   206.1 3169.36   209.3 3169.64
   219.2 3171.42   229.2 3173.34   308.9 3185.76   318.9  3187.4   338.8 3190.88
   368.7  3196.6   408.6 3204.46   458.4 3214.56
#Mann= 3 , 0 , 0
       0      .1       0   191.1    .045       0   206.1      .1       0
Bank Sta=191.1,206.1
XS Rating Curve= 0 ,0
Exp/Cntr=0.3,0.1

Type RM Length L Ch R = 1 ,60439.3 ,339.3,325.9,312.5
XS GIS Cut Line= 2
     2082345.795      386771.457     2081909.795      387096.431
#Sta/Elev= 30
       0 3202.12    10.1  3198.2    20.1 3193.64    30.2 3189.82    40.3 3187.14
    50.4 3185.05    60.4  3183.4    70.5 3182.29   100.7  3180.1   110.8  3178.9
   171.2 3168.53   181.3 3166.69   191.3 3164.66   198.6 3163.49   201.4 3163.04
   211.5 3162.64   213.6 3162.89   221.5 3163.81   241.7 3167.74   271.9 3173.22
   362.5 3189.58   402.8 3196.66     423 3200.02   463.2 3206.15   483.4 3209.51
   493.4 3211.52   503.5 3213.96   513.6  3216.7   523.6 3219.62   543.8 3225.75
#Mann= 3 , 0 , 0
       0      .1       0   198.6    .045       0   213.6      .1       0
Bank Sta=198.6,213.6
XS Rating Curve= 0 ,0
Exp/Cntr=0.3,0.1

Type RM Length L Ch R = 1 ,60113.3 ,255.6,257.7,259.9
XS GIS Cut Line= 2
     2082009.092      386485.564     2081827.679      387009.073
#Sta/Elev= 30
       0 3181.06    20.2 3179.62    30.2 3179.12    40.3 3178.81    70.5 3178.92
    80.6 3178.27    90.7 3177.32   110.8 3175.06     141  3171.3   151.1 3169.66
   161.2 3167.59   191.4 3160.99   211.6 3156.08     220 3154.72   221.6 3154.46
   231.7 3154.38     235 3154.84   241.8  3155.8   261.9 3160.45   282.1 3164.81
   292.1 3167.13   322.4 3174.64   362.6 3185.13   382.8 3190.17     413 3197.02
   453.3 3205.88   483.5 3212.23   493.6 3214.07   523.8 3218.69     554 3224.22
#Mann= 3 , 0 , 0
       0      .1       0     220    .045       0     235      .1       0
Bank Sta=220,235
XS Rating Curve= 0 ,0
Exp/Cntr=0.3,0.1

Type RM Length L Ch R = 1 ,59855.6 ,524.4,480.7,531.9
XS GIS Cut Line= 2
     2081794.969      386389.461      2081602.49      386809.031
#Sta/Elev= 30
       0 3175.47      10 3175.25    20.1 3175.88    30.1 3176.84    40.1 3177.46
    50.2 3176.92    70.2  3172.7    80.3 3171.12    90.3 3170.26   100.4 3169.85
   130.5 3169.07   140.5 3168.24   150.5 3167.06   160.6 3165.65   170.6 3164.09
   180.6 3162.31   200.7  3158.4   220.8  3154.2   230.8 3151.94   236.7 3151.09
   240.8  3150.5   250.9 3150.26   251.7  3150.3   260.9 3150.77     271 3152.52
     291 3157.43   341.2  3169.2   411.4 3185.19   431.5 3189.49   461.6 3195.37
#Mann= 3 , 0 , 0
       0      .1       0   236.7    .045       0   251.7      .1       0
Bank Sta=236.7,251.7
XS Rating Curve= 0 ,0
Exp/Cntr=0.3,0.1

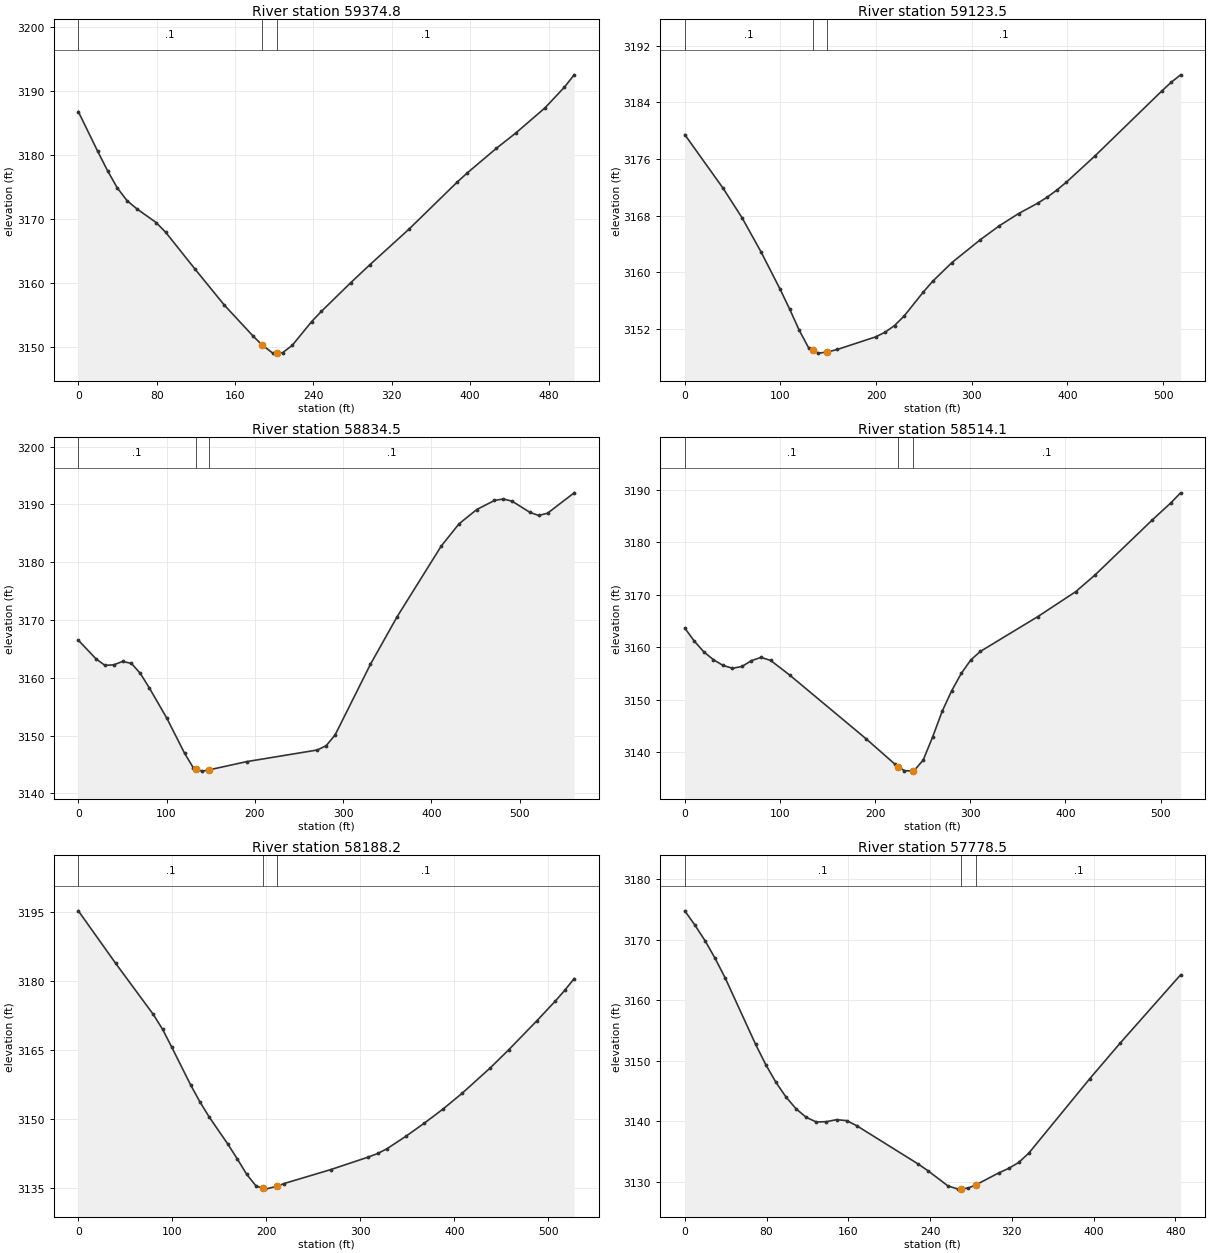
Type RM Length L Ch R = 1 ,59374.8 ,255.7,250.2,244.8
XS GIS Cut Line= 2
     2081536.014      386132.309     2081160.542      386471.649
#Sta/Elev= 28
       0 3186.77    19.8 3180.55    29.8 3177.54    39.7 3174.86    49.6 3172.87
    59.5  3171.6    79.4 3169.43    89.3 3167.88   119.1 3162.15   148.8 3156.56
   178.6 3151.64   187.4 3150.31   198.5 3149.01   202.4 3149.03   208.4 3149.07
   218.3 3150.22   238.2 3153.95   248.1 3155.54   277.9    3160   297.7 3162.85
   337.4 3168.38     387 3175.79   396.9 3177.17   426.7 3181.03   446.6 3183.43
   476.3 3187.35   496.2  3190.6   506.1 3192.52
#Mann= 3 , 0 , 0
       0      .1       0   187.4    .045       0   202.4      .1       0
Bank Sta=187.4,202.4
XS Rating Curve= 0 ,0
Exp/Cntr=0.3,0.1

Type RM Length L Ch R = 1 ,59123.5 ,296.3,289.8,283.1
XS GIS Cut Line= 2
      2081326.27      385953.011     2081014.951      386367.523
#Sta/Elev= 30
       0 3179.43    39.9 3171.89    59.8 3167.71    79.8 3162.85    99.7 3157.59
   109.7 3154.78   119.6 3151.82   129.6 3149.29   133.6 3149.01   139.6 3148.58
   148.6 3148.72   159.5  3149.1   199.4 3150.87   209.4 3151.53   219.3 3152.48
   229.3 3153.82   249.2 3157.18   259.2 3158.73   279.1 3161.35     309  3164.6
     329 3166.58   348.9 3168.28   368.9 3169.75   378.8 3170.59   388.8 3171.59
   398.8  3172.7   428.7 3176.41   498.5 3185.57   508.4 3186.81   518.4 3187.88
#Mann= 3 , 0 , 0
       0      .1       0   133.6    .045       0   148.6      .1       0
Bank Sta=133.6,148.6
XS Rating Curve= 0 ,0
Exp/Cntr=0.3,0.1

Type RM Length L Ch R = 1 ,58834.5 ,320.4,320.4,320.5
XS GIS Cut Line= 2
     2081066.614      385748.565     2080899.653      386285.063
#Sta/Elev= 30
       0 3166.51    20.1 3163.27    30.1 3162.16    40.1 3162.24    50.2 3162.83
    60.2 3162.49    70.2 3160.77    80.3 3158.29   100.3 3153.01   120.4 3146.95
   130.4  3144.4   132.9 3144.26   140.5 3143.85   147.9 3144.06   190.6 3145.49
   270.9 3147.51   280.9 3148.26     291 3150.12   331.1 3162.36   361.2 3170.55
   411.4 3182.83   431.4 3186.64   451.5 3189.12   471.6 3190.69   481.6 3190.95
   491.6 3190.56   511.7 3188.64   521.7 3188.09   531.8 3188.49   561.9 3192.01
#Mann= 3 , 0 , 0
       0      .1       0   132.9    .045       0   147.9      .1       0
Bank Sta=132.9,147.9
XS Rating Curve= 0 ,0
Exp/Cntr=0.3,0.1

Type RM Length L Ch R = 1 ,58514.1 ,324.6,325.7,326.8
XS GIS Cut Line= 2
     2080794.124      385629.266     2080639.291      386126.794
#Sta/Elev= 30
       0 3163.65      10 3161.17      20 3159.13    30.1 3157.64    40.1 3156.56
    50.1 3156.01    60.1 3156.35    70.1 3157.47    80.2 3158.08    90.2  3157.5
   110.2 3154.72   190.4 3142.62   220.4 3137.84   224.5 3137.32   230.5 3136.55
   239.5 3136.46   240.5 3136.45   250.5 3138.54   260.5 3142.96   270.6 3147.88
   280.6 3151.77   290.6 3155.04   300.6  3157.6   310.6 3159.21   370.8 3165.81
   410.8 3170.57   430.9 3173.71     491 3184.16     511 3187.49   521.1 3189.37
#Mann= 3 , 0 , 0
       0      .1       0   224.5    .045       0   239.5      .1       0
Bank Sta=224.5,239.5
XS Rating Curve= 0 ,0
Exp/Cntr=0.3,0.1

Type RM Length L Ch R = 1 ,58188.2 ,400.2,409.7,419.2
XS GIS Cut Line= 2
     2080509.929      385504.842     2080329.316      386000.446
#Sta/Elev= 30
       0 3195.23    39.8 3183.81    79.6  3172.8    89.6 3169.54    99.5 3165.61
   119.4 3157.49   129.4 3153.76   139.3 3150.48   159.2 3144.58   169.2 3141.38
   179.2 3138.04   189.1 3135.53   196.1 3135.05     199 3134.85   211.1 3135.46
     219 3136.07   268.7  3139.1   308.5 3141.81   318.5 3142.58   328.4 3143.62
   348.3 3146.29   368.2 3149.18   388.2 3152.26   408.1 3155.61   437.9 3161.09
   457.8 3165.07   487.7 3171.35   507.6 3175.69   517.5 3177.99   527.5 3180.53
#Mann= 3 , 0 , 0
       0      .1       0   196.1    .045       0   211.1      .1       0
Bank Sta=196.1,211.1
XS Rating Curve= 0 ,0
Exp/Cntr=0.3,0.1

Type RM Length L Ch R = 1 ,57778.5 ,211.6,219.1,226.6
XS GIS Cut Line= 2
     2080257.685      385330.435     2079922.404      385681.232
#Sta/Elev= 30
       0 3174.77     9.9 3172.41    19.8 3169.84    29.7 3166.91    39.6 3163.66
    69.3 3152.72    79.2 3149.38    89.1 3146.47      99 3144.03   108.9 3142.07
   118.8 3140.67   128.7  3139.9   138.6 3139.95   148.6 3140.28   158.4 3140.12
   168.4 3139.27   227.8 3133.02   237.7 3131.88   257.5 3129.34   267.4 3128.81
     270 3128.85   277.3 3128.98     285 3129.53     307 3131.47   316.9 3132.23
   326.8 3133.22   336.7 3134.77   396.1 3147.01   425.8 3152.88   485.2 3164.21
#Mann= 3 , 0 , 0
       0      .1       0     270    .045       0     285      .1       0
Bank Sta=270,285
XS Rating Curve= 0 ,0
Exp/Cntr=0.3,0.1

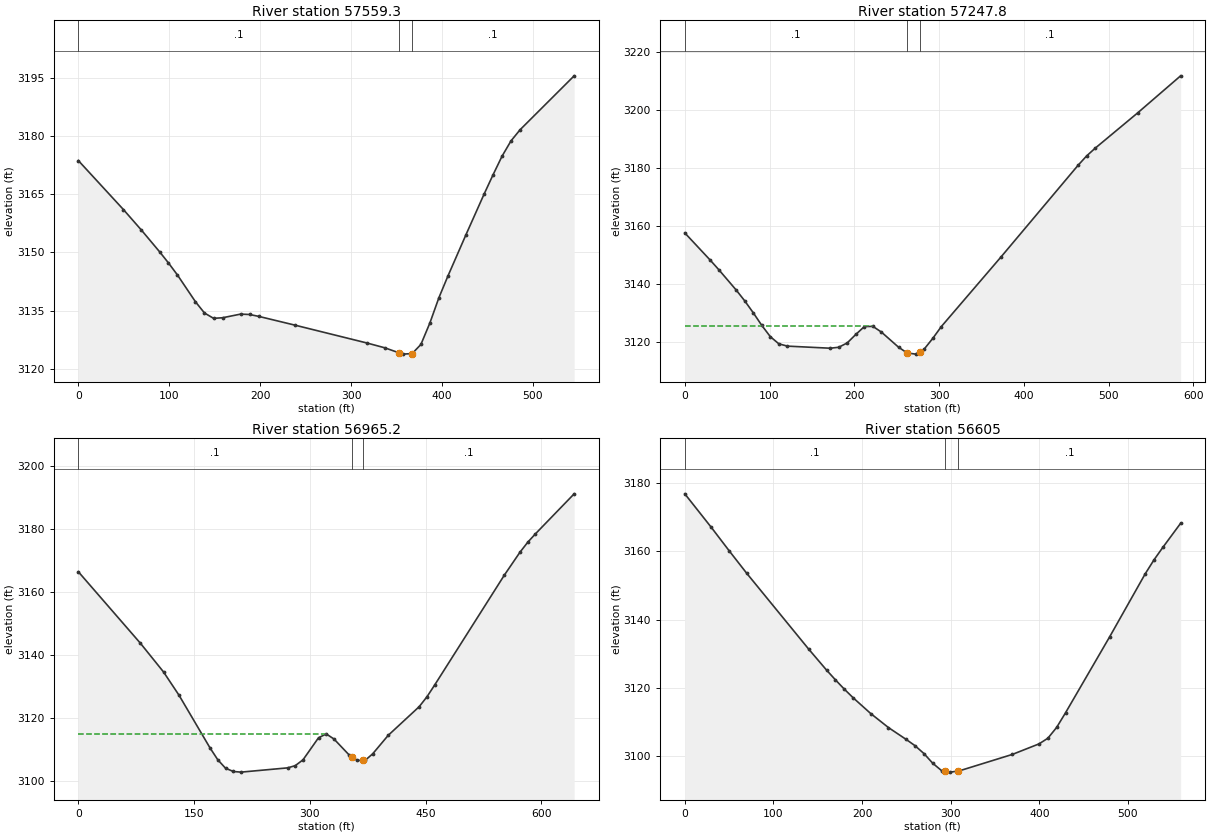
Type RM Length L Ch R = 1 ,57559.3 ,311.5,311.5,311.5
XS GIS Cut Line= 2
     2080227.237      385221.241     2079744.178      385474.593
#Sta/Elev= 30
       0 3173.73    49.6 3161.08    69.4 3155.78    89.3 3150.21    99.2 3147.29
   109.1 3144.17   128.9 3137.27   138.8 3134.37   148.8    3133   158.7 3133.15
   178.5 3134.09   188.4 3133.99   198.4 3133.51     238 3131.26   317.4 3126.64
   337.2 3125.39   352.3 3124.14     357 3123.76   367.3 3123.91   376.9 3126.26
   386.8 3131.82   396.7 3138.33   406.6 3143.91   426.5  3154.6   446.3 3165.01
   456.2 3170.02   466.1 3174.83     476  3178.8     486 3181.68   545.5  3195.6
#Mann= 3 , 0 , 0
       0      .1       0   352.3    .045       0   367.3      .1       0
Bank Sta=352.3,367.3
XS Rating Curve= 0 ,0
Exp/Cntr=0.3,0.1

Type RM Length L Ch R = 1 ,57247.8 ,291.8,282.6,273.4
XS GIS Cut Line= 2
     2080153.267      384955.969     2079635.072       385227.75
#Sta/Elev= 30
       0 3157.75    30.3 3148.27    40.4 3144.97    60.5  3138.1    70.6 3134.36
    80.7 3130.24    90.8 3125.87   100.9 3121.97     111 3119.49   121.1  3118.7
   171.5 3117.98   181.6  3118.3   191.7 3119.81   201.8 3122.73   211.9 3125.45
     222 3125.51     232 3123.55   252.2 3118.34   262.2 3116.37   272.4 3115.94
   277.2 3116.77   282.5 3117.68   292.6 3121.36   302.7 3125.44   373.3 3149.51
   464.1 3181.08   474.2 3184.31   484.2 3186.95   534.7 3199.22   585.1 3211.93
#Mann= 3 , 0 , 0
       0      .1       0   262.2    .045       0   277.2      .1       0
#XS Ineff= 2 , 0
          221.61 3125.74
Permanent Ineff=
       F       F
Bank Sta=262.2,277.2
XS Rating Curve= 0 ,0
Exp/Cntr=0.3,0.1

Type RM Length L Ch R = 1 ,56965.2 ,364.8,360.3,355.7
XS GIS Cut Line= 2
     2079977.464      384575.245     2079572.905      385074.235
#Sta/Elev= 30
       0 3166.41    80.3 3143.73   110.4 3134.57   130.5 3127.16   170.6 3110.45
   180.7 3106.67   190.7    3104   200.8 3102.95   210.8 3102.75     271  3104.1
     281  3104.8   291.1 3106.66   311.2 3113.67   321.2 3114.88   331.2 3113.28
   351.3 3108.09   354.4 3107.59   361.3 3106.47   369.4 3106.45   371.4 3106.45
   381.4 3108.57   401.5 3114.44   441.6 3123.54   451.7 3126.69   461.7 3130.43
     552 3165.35   572.1 3172.58   582.2 3175.76   592.2 3178.44   642.4 3191.16
#Mann= 3 , 0 , 0
       0      .1       0   354.4    .045       0   369.4      .1       0
#XS Ineff= 2 , 0
          321.79 3114.85
Permanent Ineff=
       F       F
Bank Sta=354.4,369.4
XS Rating Curve= 0 ,0
Exp/Cntr=0.3,0.1

Type RM Length L Ch R = 1 ,56605   ,427.3,433.5,439.6
XS GIS Cut Line= 2
     2079593.672      384394.056     2079331.549      384888.397
#Sta/Elev= 30
       0 3176.89      30 3167.02      50 3160.21    69.9 3153.58   139.9 3131.32
   159.9 3125.22   169.9 3122.36   179.8 3119.67   189.8 3117.12   209.8 3112.46
   229.8 3108.35   249.8 3104.87   259.8 3103.03   269.8 3100.74   279.8 3097.88
   289.8 3095.71   293.3 3095.56   299.8 3095.28   308.3  3095.6   309.7 3095.65
   369.7 3100.48   399.7 3103.56   409.7 3105.22   419.6 3108.39   429.6 3112.67
   479.6 3135.04   519.6 3153.46   529.6 3157.59   539.6 3161.25   559.5 3168.25
#Mann= 3 , 0 , 0
       0      .1       0   293.3    .045       0   308.3      .1       0
Bank Sta=293.3,308.3
XS Rating Curve= 0 ,0
Exp/Cntr=0.3,0.1