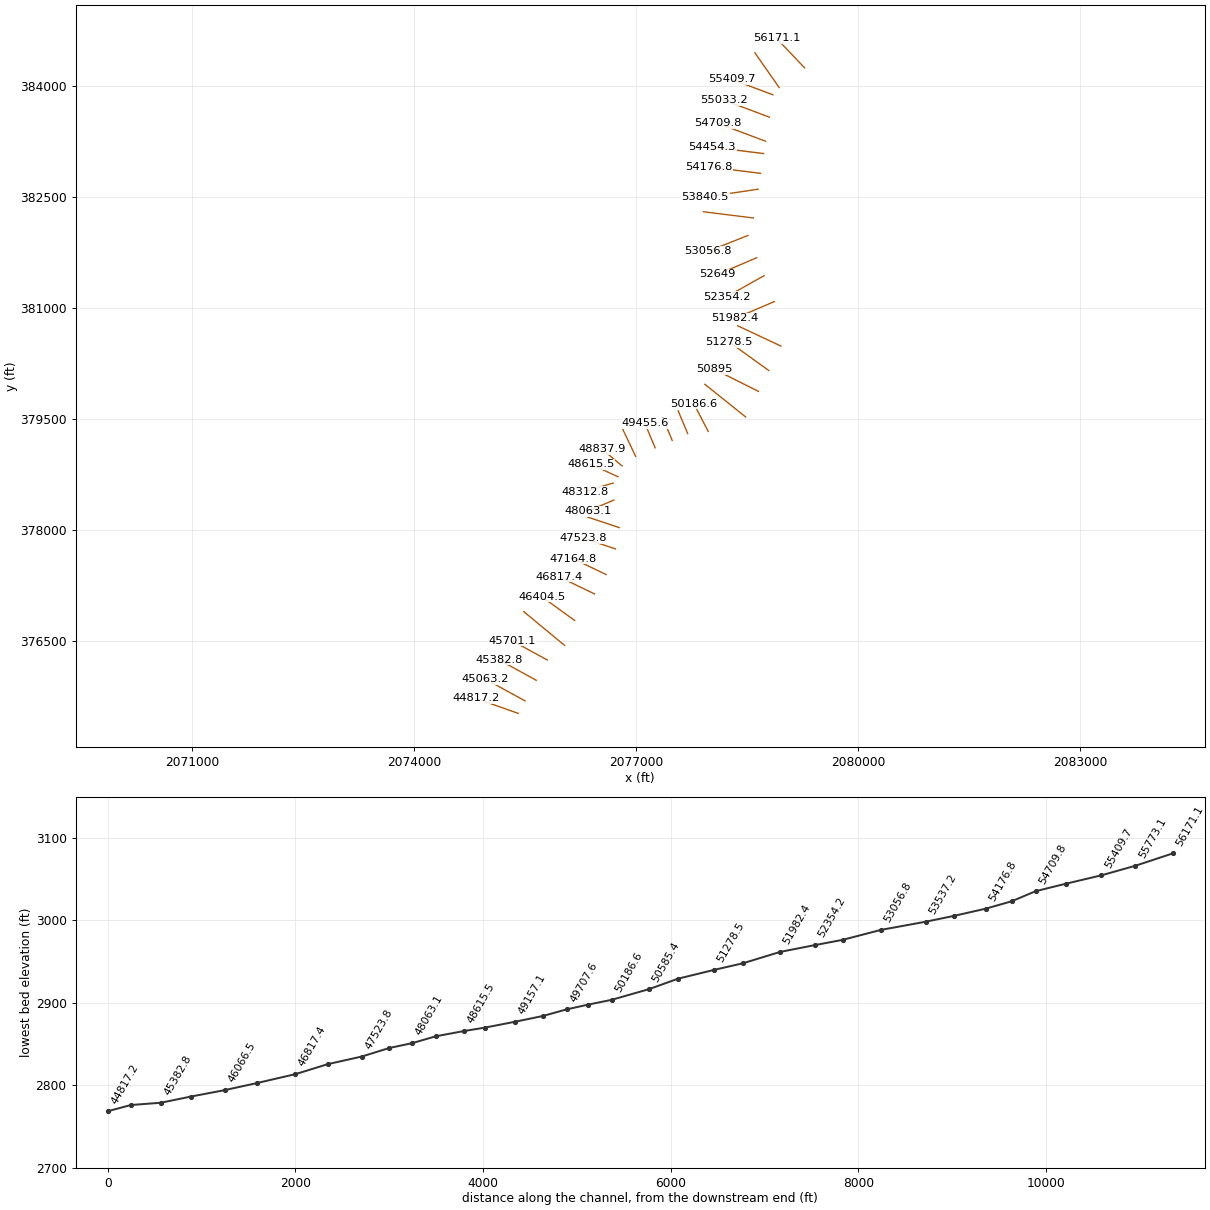
HEC-RAS study BigClearCk.prj: BigClearCk

--- BigClearCk.g01 (geometry) --- (continued)

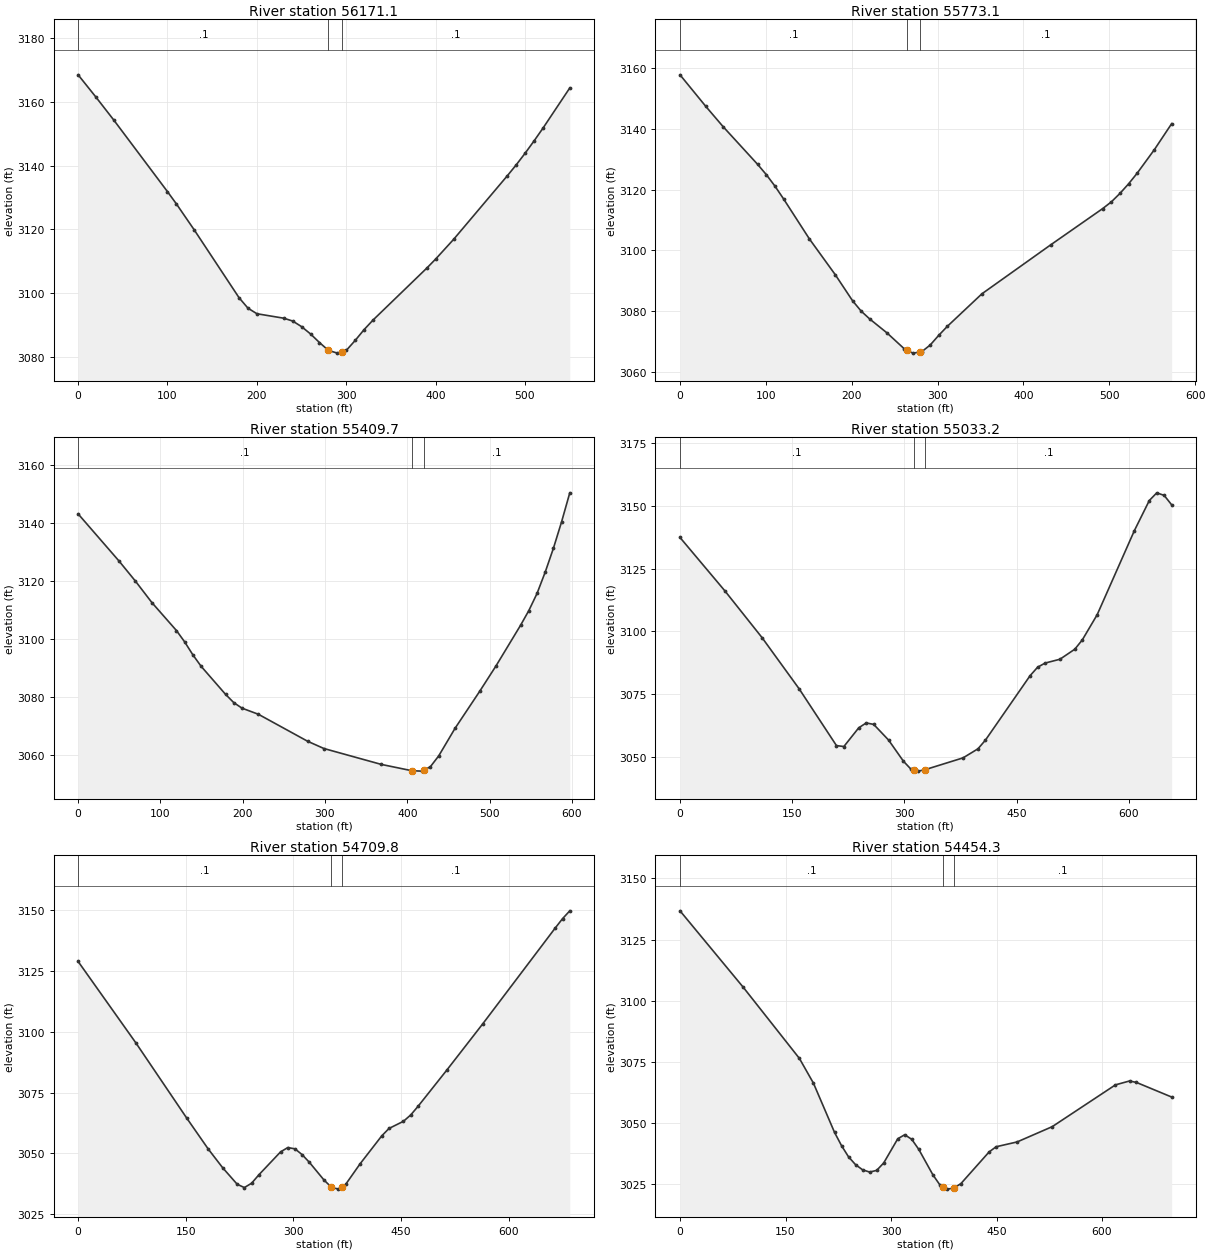
Type RM Length L Ch R = 1 ,56171.1 ,466.3,397.8,455.2
XS GIS Cut Line= 2
     2079273.582       384242.94     2078894.384      384641.576
#Sta/Elev= 30
       0 3168.49      20 3161.47      40 3154.25     100  3131.8     110 3127.94
     130 3119.76   180.1 3098.48   190.1 3095.19   200.1 3093.45   230.1 3092.05
   240.1 3091.16   250.1 3089.39   260.1  3087.1   270.1  3084.4   280.1 3081.94
   290.1 3081.08   295.1 3081.51   300.1 3081.94   310.1 3085.08   320.1 3088.49
   330.1 3091.49   390.1 3107.76   400.1 3110.63   420.1 3116.78   480.2 3136.75
   490.2 3140.19   500.2 3143.86   510.2 3147.72   520.2 3151.74   550.2 3164.37
#Mann= 3 , 0 , 0
       0      .1       0   280.1    .045       0   295.1      .1       0
Bank Sta=280.1,295.1
XS Rating Curve= 0 ,0
Exp/Cntr=0.3,0.1

Type RM Length L Ch R = 1 ,55773.1 ,348.9,363.5,378.1
XS GIS Cut Line= 2
     2078930.001      383976.984     2078602.143      384446.572
#Sta/Elev= 30
       0 3157.78    30.1 3147.37    50.2 3140.71    90.4  3128.3   100.5 3124.92
   110.5 3121.17   120.6 3116.94   150.7 3103.75   180.9 3091.94     201 3083.38
     211 3079.97     221 3077.37   241.1 3072.79   261.2 3067.56   264.9 3067.04
   271.3 3066.13   279.9 3066.48   281.3 3066.54   291.4 3068.79   301.4    3072
   311.5 3074.98   351.7 3085.67     432 3101.83   492.3 3113.72   502.4 3115.93
   512.4 3118.71   522.5 3121.87   532.5 3125.38   552.6 3133.16   572.7  3141.7
#Mann= 3 , 0 , 0
       0      .1       0   264.9    .045       0   279.9      .1       0
Bank Sta=264.9,279.9
XS Rating Curve= 0 ,0
Exp/Cntr=0.3,0.1

Type RM Length L Ch R = 1 ,55409.7 ,375.7,376.2,376.3
XS GIS Cut Line= 2
     2078846.157       383879.24     2078286.539      384088.574
#Sta/Elev= 30
       0 3143.23    49.8 3126.94    69.7 3120.02    89.6 3112.65   119.5 3102.99
   129.5 3099.06   139.4 3094.63   149.4 3090.68   179.2 3080.97   189.2 3078.11
   199.2 3076.21   219.1  3074.1   278.8 3064.81   298.7 3062.29   368.4 3056.81
   405.9 3054.61   418.2 3054.49   420.9 3054.91   428.2 3056.05   438.2 3059.74
   458.1 3069.28     488 3082.02   507.9 3090.82   537.7 3104.81   547.7 3109.86
   557.7 3115.78   567.6 3123.12   577.6 3131.36   587.5 3140.46   597.5  3150.5
#Mann= 3 , 0 , 0
       0      .1       0   405.9    .045       0   420.9      .1       0
Bank Sta=405.9,420.9
XS Rating Curve= 0 ,0
Exp/Cntr=0.3,0.1

Type RM Length L Ch R = 1 ,55033.2 ,323.4,323.4,323.4
XS GIS Cut Line= 2
     2078798.196      383576.879     2078182.472        383807.2
#Sta/Elev= 30
       0 3137.35    59.8 3116.18   109.6 3097.54   159.4 3077.09   209.2 3054.54
   219.1 3054.17     239 3061.62     249 3063.56     259 3062.97   278.9 3056.74
   298.8  3048.3   308.8 3045.17   312.7 3044.86   318.7 3044.38   327.7 3044.96
   378.5 3049.66   398.4 3053.26   408.4 3056.72   468.1 3082.36   478.1 3085.71
   488.1 3087.37     508  3088.9   527.9  3092.9   537.9 3096.59   557.8 3106.62
   607.6 3140.12   627.5 3152.06   637.5 3155.12   647.4 3154.09   657.4 3150.34
#Mann= 3 , 0 , 0
       0      .1       0   312.7    .045       0   327.7      .1       0
Bank Sta=312.7,327.7
XS Rating Curve= 0 ,0
Exp/Cntr=0.3,0.1

Type RM Length L Ch R = 1 ,54709.8 ,249.9,255.2,260.6
XS GIS Cut Line= 2
     2078746.726      383252.392     2078105.244      383492.348
#Sta/Elev= 30
       0 3128.89    80.6 3095.35   151.1 3064.58   181.3 3051.76   201.4 3044.06
   221.6 3037.29   231.6 3035.93   241.7 3037.73   251.8 3041.18     282  3050.6
   292.1 3052.38   302.2 3051.84   312.2 3049.42   322.3 3046.26   342.4 3039.07
   352.8 3036.08   362.6 3035.29   367.8  3036.3   372.7 3037.25   392.8  3045.7
     423  3057.2   433.1 3060.24   453.2 3063.18   463.3 3065.78   473.4 3069.29
   513.7 3084.27     564 3103.38   664.8 3142.71   674.8 3146.48   684.9 3149.71
#Mann= 3 , 0 , 0
       0      .1       0   352.8    .045       0   367.8      .1       0
#XS Ineff= 2 , 0
          298.85 3051.98
Permanent Ineff=
       F       F
Bank Sta=352.8,367.8
XS Rating Curve= 0 ,0
Exp/Cntr=0.3,0.1

Type RM Length L Ch R = 1 ,54454.3 ,277.6,277.6,277.7
XS GIS Cut Line= 2
     2078720.278      383085.656      2078026.63      383171.842
#Sta/Elev= 30
       0 3136.71    89.9  3105.5   169.8 3076.42   189.7 3066.34   219.7 3046.24
   229.7 3040.79   239.6 3036.26   249.6 3033.05   259.6 3030.96   269.6 3030.04
   279.6 3030.72   289.6 3033.76   309.6 3043.64   319.5 3045.28   329.5  3043.4
   339.5 3039.29   359.5 3028.93   369.5 3024.78   374.1 3023.99   379.4 3023.07
   389.1 3023.45   399.4 3025.33   439.4 3038.24   449.4 3040.37   479.3 3042.34
   529.2 3048.58   619.1 3065.65   639.1 3067.23     649 3066.63     699 3060.67
#Mann= 3 , 0 , 0
       0      .1       0   374.1    .045       0   389.1      .1       0
#XS Ineff= 2 , 0
          319.93 3045.13
Permanent Ineff=
       F       F
Bank Sta=374.1,389.1
XS Rating Curve= 0 ,0
Exp/Cntr=0.3,0.1

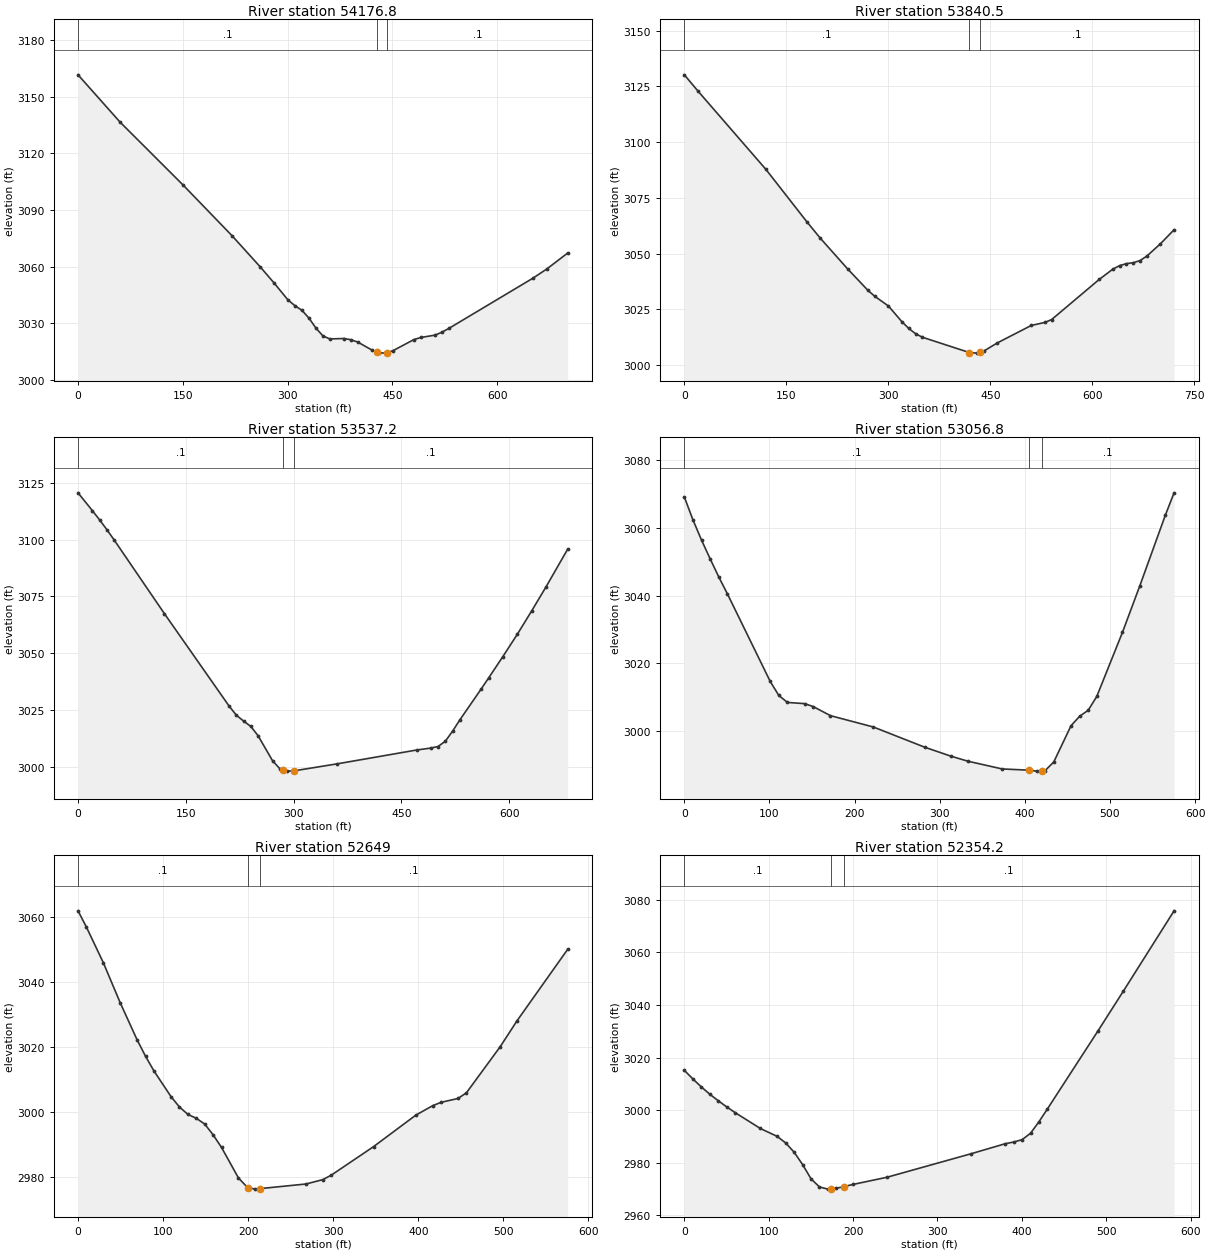
Type RM Length L Ch R = 1 ,54176.8 ,329.4,335.4,341.3
XS GIS Cut Line= 2
     2078677.968      382818.922      2077982.29      382905.359
#Sta/Elev= 30
       0 3161.74    60.1 3136.68   150.2 3103.33   220.3 3076.42   260.4    3060
   280.4 3051.39   300.4 3042.33   310.5 3039.22   320.5 3036.79   330.5 3032.66
   340.5 3027.37   350.5 3023.19   360.5 3021.58   380.6 3021.81   390.6 3021.16
   400.6 3019.89   420.6  3015.7   427.4 3014.69   430.6 3014.22   440.6 3014.05
   442.4 3014.28   450.7 3015.32   480.7 3021.22   490.7 3022.36   510.8 3023.58
   520.8 3025.13   530.8 3027.16     651 3053.78     671 3058.69     701  3067.2
#Mann= 3 , 0 , 0
       0      .1       0   427.4    .045       0   442.4      .1       0
Bank Sta=427.4,442.4
XS Rating Curve= 0 ,0
Exp/Cntr=0.3,0.1

Type RM Length L Ch R = 1 ,53840.5 ,309.3,303.2,297
XS GIS Cut Line= 2
     2078643.873      382603.971     2077931.244      382499.676
#Sta/Elev= 30
       0 3130.14      20 3122.87     120 3087.73   180.1 3064.29   200.1 3056.85
   240.1 3043.16   270.1  3033.5   280.1 3030.86   300.1 3026.52   320.1 3019.42
   330.1 3016.45   340.1 3014.08   350.1 3012.52   419.1 3005.67   430.1  3005.4
   434.1 3005.74   440.1 3006.26   460.1 3009.95   510.2 3017.81   530.2 3019.16
   540.2 3020.46   610.2 3038.46   630.2 3043.06   640.2 3044.63   650.2 3045.52
   660.2 3045.92   670.2  3046.9   680.2 3048.91   700.2 3054.43   720.2 3060.71
#Mann= 3 , 0 , 0
       0      .1       0   419.1    .045       0   434.1      .1       0
Bank Sta=419.1,434.1
XS Rating Curve= 0 ,0
Exp/Cntr=0.3,0.1

Type RM Length L Ch R = 1 ,53537.2 ,467.2,478.7,490.2
XS GIS Cut Line= 2
     2078582.346      382216.084     2077906.132      382300.103
#Sta/Elev= 30
       0 3120.55      20 3112.72    30.1 3108.63    40.1 3104.38    50.1 3099.92
   120.2 3067.47   210.4 3026.77   220.5 3022.78   230.5 3020.25   240.5 3017.89
   250.5 3013.84   270.6 3002.87   280.6  2999.4   285.2 2998.88   290.6 2998.27
   300.2 2998.38   360.8 3001.48     471 3007.54     491 3008.41     501 3009.09
   511.1 3011.42   521.1  3015.8   531.1 3020.71   561.2 3034.48   571.2 3039.15
   591.2 3048.63   611.3 3058.43   631.3 3068.71   651.4 3079.35   681.4 3095.85
#Mann= 3 , 0 , 0
       0      .1       0   285.2    .045       0   300.2      .1       0
Bank Sta=285.2,300.2
XS Rating Curve= 0 ,0
Exp/Cntr=0.3,0.1

Type RM Length L Ch R = 1 ,53056.8 ,407.5,408.1,408.7
XS GIS Cut Line= 2
      2078507.42      381979.251      2077972.18      381768.349
#Sta/Elev= 30
       0 3068.99    10.1 3062.26    20.2  3056.3    30.3  3050.8    40.4 3045.49
    50.5 3040.53   100.9  3014.7     111 3010.58   121.1 3008.54   141.3 3008.18
   151.4 3007.32   171.6 3004.65     222 3001.31   282.6 2995.34   312.9 2992.74
   333.1 2991.24   373.4 2988.96   405.1  2988.6   413.8 2988.32   420.1 2988.43
   423.9  2988.5     434 2991.03   454.2 3001.66   464.3 3004.46   474.4 3006.23
   484.5  3010.3   514.7 3029.19   534.9 3042.75   565.2 3063.75   575.3 3070.23
#Mann= 3 , 0 , 0
       0      .1       0   405.1    .045       0   420.1      .1       0
Bank Sta=405.1,420.1
XS Rating Curve= 0 ,0
Exp/Cntr=0.3,0.1

Type RM Length L Ch R = 1 ,52649   ,291.9,294.2,296.4
XS GIS Cut Line= 2
     2078627.733      381679.523     2078098.504      381453.089
#Sta/Elev= 30
       0 3061.84     9.9 3056.82    29.8 3045.85    49.6 3033.55    69.5 3022.13
    79.4 3017.08    89.3 3012.57   109.2 3004.73   119.1 3001.54     129 2999.25
     139 2998.03   148.9 2996.26   158.8 2992.94   168.7 2989.05   188.6 2979.66
   199.4  2976.7   208.4 2976.24   214.4 2976.41     268 2977.82   287.8 2979.17
   297.7 2980.54   347.4 2989.32     397 2998.99   416.8  3001.9   426.8 3002.94
   446.6 3004.12   456.5 3005.86   496.2 3020.04   516.1 3028.06   575.6 3050.03
#Mann= 3 , 0 , 0
       0      .1       0   199.4    .045       0   214.4      .1       0
Bank Sta=199.4,214.4
XS Rating Curve= 0 ,0
Exp/Cntr=0.3,0.1

Type RM Length L Ch R = 1 ,52354.2 ,374.5,371.8,369.1
XS GIS Cut Line= 2
     2078725.505      381435.951     2078218.711      381153.093
#Sta/Elev= 30
       0 3015.12      10 3011.88      20 3008.86      30 3006.08      40  3003.6
      50 3001.26      60 2999.08    90.1    2993   110.1 2989.98   120.1  2987.5
   130.1 2983.98   140.1  2979.3   150.1 2973.87   160.1 2970.76   170.1 2969.93
   174.2 2970.07   180.1 2970.26   189.2  2970.9   200.1 2971.73   240.2 2974.45
   340.2 2983.43   380.2  2987.2   390.3 2987.85   400.3 2988.75   410.3  2991.2
   420.3 2995.58   430.3 3000.45   490.3 3030.17   520.4 3045.32   580.4 3075.82
#Mann= 3 , 0 , 0
       0      .1       0   174.2    .045       0   189.2      .1       0
Bank Sta=174.2,189.2
XS Rating Curve= 0 ,0
Exp/Cntr=0.3,0.1

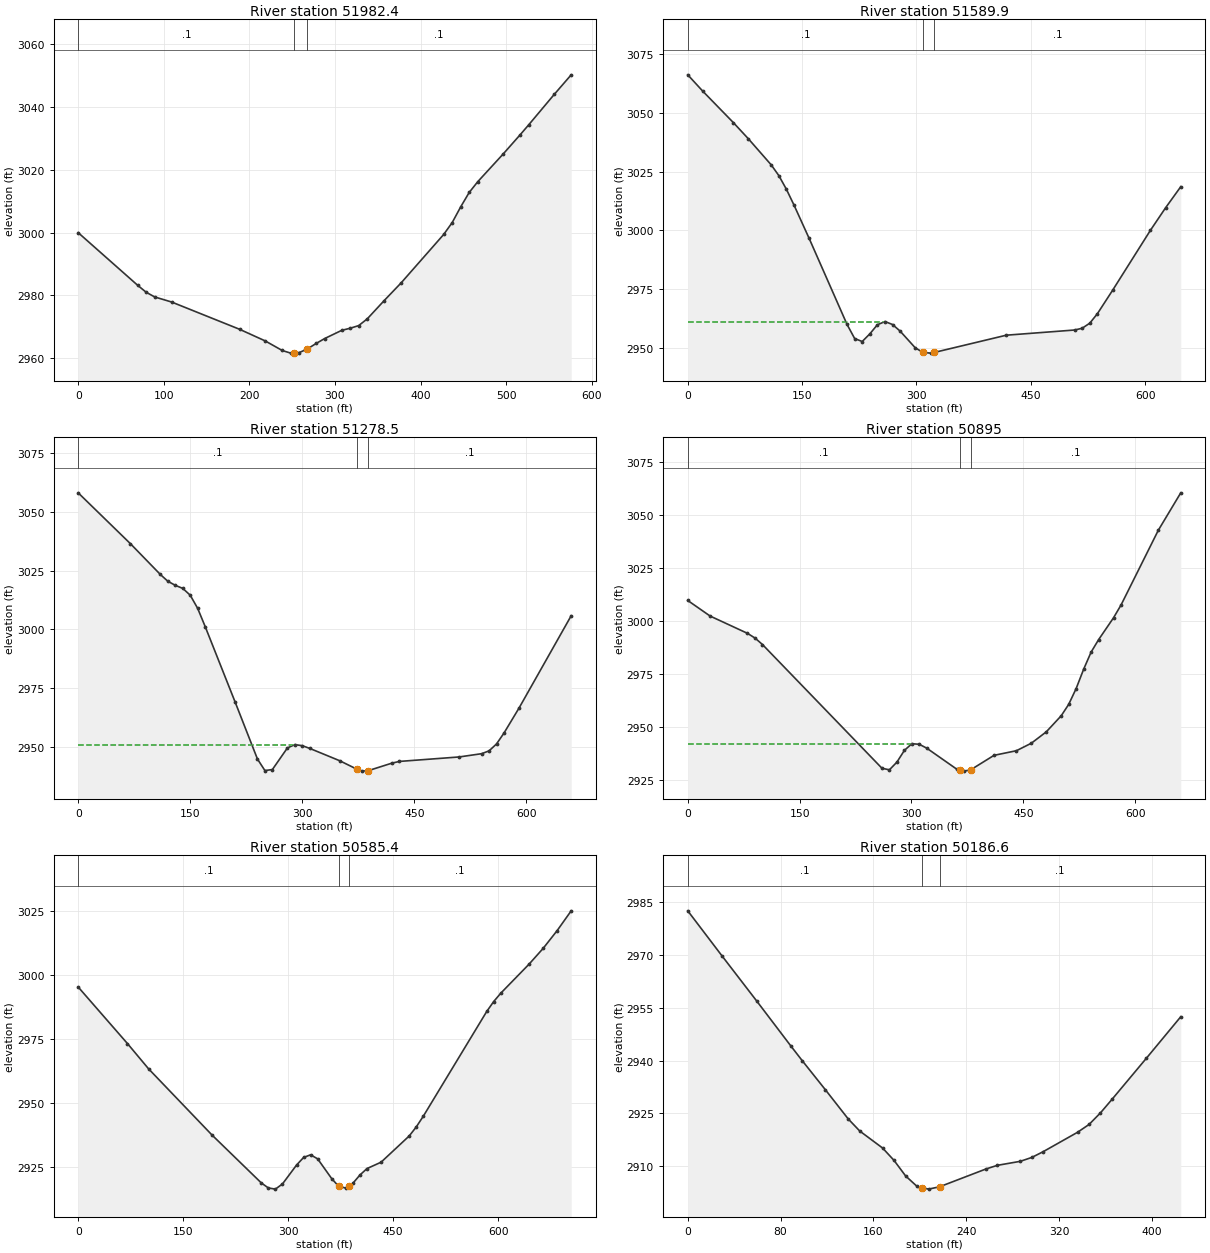
Type RM Length L Ch R = 1 ,51982.4 ,411.8,392.4,373.1
XS GIS Cut Line= 2
     2078865.505       381087.18     2078335.915      380860.592
#Sta/Elev= 30
       0    3000    69.5 2983.23    79.4 2981.02    89.4 2979.52   109.2  2977.9
   188.7  2969.2   218.5 2965.51   238.4 2962.46   248.3 2961.62   252.5 2961.69
   258.2 2961.79   267.5 2962.91   278.1 2964.71     288 2966.27   307.9 2968.88
   317.8 2969.55   327.7 2970.39   337.7 2972.53   357.5 2978.36   377.4 2984.03
     427 2999.42     437 3003.23   446.9 3008.22   456.8  3012.8   466.8 3016.23
   496.6 3025.09   516.4  3031.2   526.4 3034.37   556.2 3044.06     576 3050.29
#Mann= 3 , 0 , 0
       0      .1       0   252.5    .045       0   267.5      .1       0
Bank Sta=252.5,267.5
XS Rating Curve= 0 ,0
Exp/Cntr=0.3,0.1

Type RM Length L Ch R = 1 ,51589.9 ,315.9,311.7,307.4
XS GIS Cut Line= 2
     2078955.075      380486.078     2078369.516      380760.423
#Sta/Elev= 30
       0 3066.06    19.9 3059.05    59.7 3045.82    79.6 3038.88   109.4 3027.87
   119.4 3023.32   129.3 3017.54   139.3 3010.82   159.2 2996.65   208.9 2960.14
   218.9 2954.15   228.8 2952.89   238.8 2956.13   248.7    2960   258.7 2961.36
   268.6  2960.1   278.6 2957.28   298.4  2950.2   308.5 2948.27   318.4 2947.96
   323.5 2948.26   417.8 2955.57   507.4 2957.77   517.3 2958.52   527.3 2960.68
   537.2 2964.66   557.1 2974.58   606.8 3000.08   626.7 3009.64   646.6 3018.59
#Mann= 3 , 0 , 0
       0      .1       0   308.5    .045       0   323.5      .1       0
#XS Ineff= 2 , 0
          257.93 2961.32
Permanent Ineff=
       F       F
Bank Sta=308.5,323.5
XS Rating Curve= 0 ,0
Exp/Cntr=0.3,0.1

Type RM Length L Ch R = 1 ,51278.5 ,379.9,383.1,386.4
XS GIS Cut Line= 2
     2078790.289      380156.507      2078253.77      380541.115
#Sta/Elev= 30
       0    3058      70 3036.38     110 3023.33     120 3020.46     130 3018.72
     140 3017.42     150 3014.53     160 3008.92     170 3001.23     210 2969.26
     240 2944.97     250 2940.06     260 2940.49   280.1 2949.66   290.1 2951.08
   300.1 2950.62   310.1 2949.46   350.1 2944.24   373.1 2940.66   380.1 2939.82
   388.1 2939.99   420.1 2943.22   430.1 2943.94   510.1 2945.84   540.1 2947.22
   550.1 2948.42   560.1 2951.36   570.1 2955.98   590.1 2966.52   660.1 3005.81
#Mann= 3 , 0 , 0
       0      .1       0   373.1    .045       0   388.1      .1       0
#XS Ineff= 2 , 0
          292.65 2951.09
Permanent Ineff=
       F       F
Bank Sta=373.1,388.1
XS Rating Curve= 0 ,0
Exp/Cntr=0.3,0.1

Type RM Length L Ch R = 1 ,50895   ,314.1,309.6,305.2
XS GIS Cut Line= 2
     2078649.611      379875.151     2078058.378      380170.899
#Sta/Elev= 30
       0 3009.55      30 3002.21    80.1 2994.07    90.2 2991.85   100.2  2988.8
   260.4 2930.54   270.4 2929.79   280.5 2933.44   290.5 2938.95   300.5 2942.09
   310.5 2941.82   320.5 2939.99   360.6 2930.13   364.7 2929.74   370.6 2929.18
   379.7 2929.86   410.7 2936.62   440.7 2938.79   460.8 2942.34   480.8 2947.69
   500.8 2955.26   510.8 2960.61   520.8 2968.06   530.9  2977.2   540.9 2985.25
   550.9 2991.09   570.9 3001.38     581 3007.41     631 3042.63   661.1 3060.25
#Mann= 3 , 0 , 0
       0      .1       0   364.7    .045       0   379.7      .1       0
#XS Ineff= 2 , 0
          301.95 2942.13
Permanent Ineff=
       F       F
Bank Sta=364.7,379.7
XS Rating Curve= 0 ,0
Exp/Cntr=0.3,0.1

Type RM Length L Ch R = 1 ,50585.4 ,408.2,398.8,389.3
XS GIS Cut Line= 2
     2078476.758      379529.445     2077926.575      379969.524
#Sta/Elev= 30
       0 2995.39    70.4 2973.32   100.6 2963.45   191.2 2937.62   261.7 2918.91
   271.8 2916.94   281.8 2916.49   291.9 2918.51     312 2925.88   322.1 2928.85
   332.1 2929.89   342.2 2928.31   362.3 2920.58   372.1 2917.62   382.5  2916.9
   387.1 2917.76   392.5 2918.76   402.6    2922   412.7 2924.52   432.8    2927
     473 2937.24   483.1 2940.77   493.2 2944.97   583.8 2985.85   593.8 2989.74
   603.9 2992.99   644.2 3004.29   664.3 3010.44   684.4 3017.41   704.5 3025.14
#Mann= 3 , 0 , 0
       0      .1       0   372.1    .045       0   387.1      .1       0
#XS Ineff= 2 , 0
          331.62 2929.67
Permanent Ineff=
       F       F
Bank Sta=372.1,387.1
XS Rating Curve= 0 ,0
Exp/Cntr=0.3,0.1

Type RM Length L Ch R = 1 ,50186.6 ,251.6,249.8,247.9
XS GIS Cut Line= 2
     2077971.368      379333.836     2077775.348      379710.698
#Sta/Elev= 26
       0 2982.52    29.6 2969.69    59.3 2956.97    88.9 2944.13    98.8 2939.92
   118.6 2931.73   138.3 2923.44   148.2 2920.02   167.9 2915.19   177.8 2911.66
   187.7 2907.28   197.6 2904.29     202 2903.95   207.5 2903.53     217  2904.2
   256.8 2909.23   266.7 2910.28   286.5 2911.42   296.4 2912.52   306.2 2914.15
   335.9 2919.67   345.8 2921.89   355.6 2925.17   365.5 2928.99   395.2 2940.69
   424.8 2952.46
#Mann= 3 , 0 , 0
       0      .1       0     202    .045       0     217      .1       0
Bank Sta=202,217
XS Rating Curve= 0 ,0
Exp/Cntr=0.3,0.1

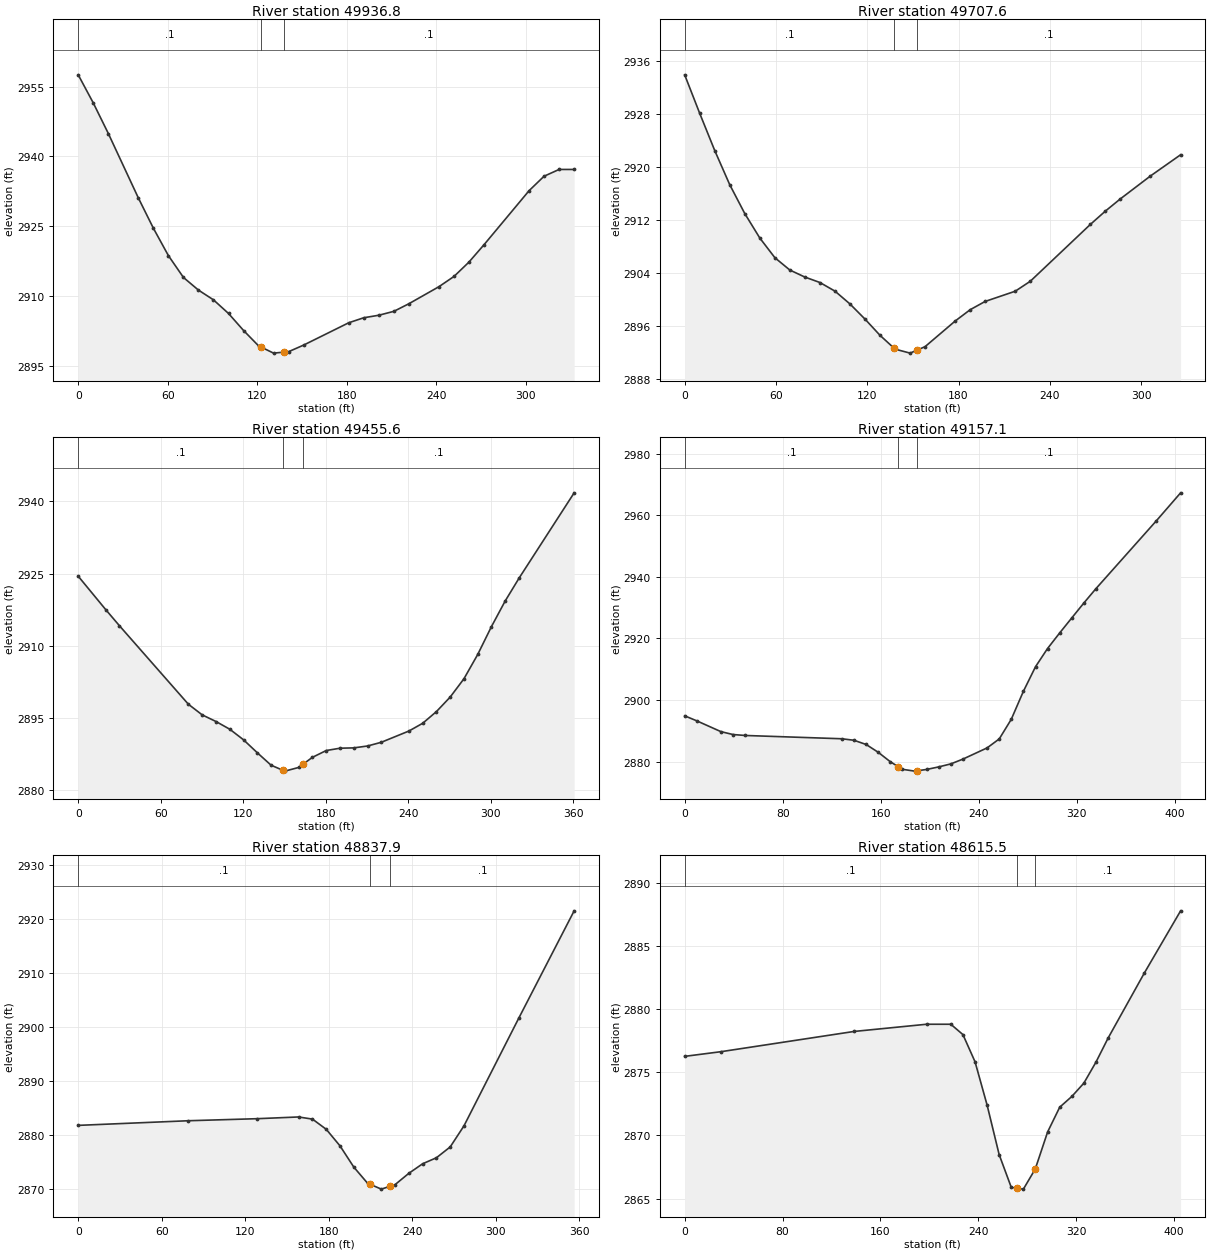
Type RM Length L Ch R = 1 ,49936.8 ,229.2,229.2,229.2
XS GIS Cut Line= 2
     2077694.419      379304.951     2077565.305      379611.474
#Sta/Elev= 30
       0 2957.53    10.1 2951.49    20.2 2944.92    40.3  2931.1    50.4 2924.58
    60.5 2918.68    70.6 2913.99    80.6 2911.29    90.7 2909.19   100.8 2906.26
   110.9  2902.6     121 2899.29   122.9    2899     131 2897.74   137.9 2897.95
   141.1 2898.05   151.2 2899.47   181.4 2904.26   191.5 2905.34   201.6 2905.88
   211.7 2906.72   221.7 2908.34   241.9 2912.01     252 2914.21     262 2917.28
   272.1 2921.01   302.4 2932.65   312.4 2935.74   322.5  2937.2   332.6  2937.2
#Mann= 3 , 0 , 0
       0      .1       0   122.9    .045       0   137.9      .1       0
Bank Sta=122.9,137.9
XS Rating Curve= 0 ,0
Exp/Cntr=0.3,0.1

Type RM Length L Ch R = 1 ,49707.6 ,252,252,252
XS GIS Cut Line= 2
     2077484.819      379213.298     2077358.291      379513.683
#Sta/Elev= 29
       0 2933.85     9.9 2928.04    19.8 2922.43    29.6 2917.32    39.5 2912.97
    49.4 2909.28    59.3 2906.32    69.1 2904.47      79 2903.41    88.9 2902.59
    98.8 2901.29   108.6 2899.37   118.5 2897.09   128.4 2894.64   137.6 2892.71
   138.3 2892.56   148.2 2891.96   152.6  2892.4     158 2892.93   177.8 2896.79
   187.7  2898.5   197.5 2899.74   217.3 2901.28   227.2 2902.78   266.7 2911.34
   276.6 2913.35   286.4 2915.18   306.2 2918.63     326 2921.82
#Mann= 3 , 0 , 0
       0      .1       0   137.6    .045       0   152.6      .1       0
Bank Sta=137.6,152.6
XS Rating Curve= 0 ,0
Exp/Cntr=0.3,0.1

Type RM Length L Ch R = 1 ,49455.6 ,297,298,299.1
XS GIS Cut Line= 2
     2077254.289      379112.493     2077114.337      379444.746
#Sta/Elev= 30
       0 2924.47      20 2917.53      30 2914.17    80.1 2897.87    90.1 2895.67
   100.2 2894.28   110.2 2892.68   120.2 2890.48   130.2 2887.79   140.2 2885.21
   148.5 2884.19   150.2 2883.98   160.2 2884.74   163.5 2885.43   170.2 2886.84
   180.3 2888.26   190.3 2888.74   200.3 2888.81   210.3  2889.2   220.3 2889.97
   240.4 2892.31   250.4 2893.92   260.4 2896.35   270.4 2899.37   280.4 2903.17
   290.4 2908.21   300.4 2914.01   310.4 2919.34   320.5 2924.09   360.5 2941.79
#Mann= 3 , 0 , 0
       0      .1       0   148.5    .045       0   163.5      .1       0
Bank Sta=148.5,163.5
XS Rating Curve= 0 ,0
Exp/Cntr=0.3,0.1

Type RM Length L Ch R = 1 ,49157.1 ,309.5,319.2,328.9
XS GIS Cut Line= 2
     2076990.552      378997.167     2076816.858      379362.731
#Sta/Elev= 30
       0 2894.91     9.9 2893.27    29.6 2889.77    39.5 2888.83    49.4 2888.53
   128.3 2887.46   138.2 2886.97   148.1  2885.6   157.9 2883.08   167.8 2880.01
   174.3 2878.39   177.7 2877.55   187.6 2876.96   189.3 2877.05   197.4  2877.5
   207.3 2878.33   217.2 2879.31     227 2880.85   246.8  2884.5   256.7 2887.41
   266.5 2893.77   276.4 2902.86   286.3 2910.84   296.1 2916.74     306 2921.79
   315.9 2926.68   325.8 2931.54   335.6 2936.17     385 2958.23   404.7 2967.26
#Mann= 3 , 0 , 0
       0      .1       0   174.3    .045       0   189.3      .1       0
Bank Sta=174.3,189.3
XS Rating Curve= 0 ,0
Exp/Cntr=0.3,0.1

Type RM Length L Ch R = 1 ,48837.9 ,216.3,222.3,228.3
XS GIS Cut Line= 2
     2076807.269      378868.213     2076533.682      379096.797
#Sta/Elev= 20
       0 2881.73    79.2 2882.59   128.7 2882.97   158.4 2883.29   168.4 2882.89
   178.3    2881   188.2 2877.92   198.1 2873.99     208 2870.99   209.4 2870.84
   217.9  2869.9   224.4 2870.45   227.8 2870.74   237.7 2872.84   247.6 2874.61
   257.5 2875.72   267.4 2877.73   277.3 2881.64   316.9 2901.73   356.5 2921.54
#Mann= 3 , 0 , 0
       0      .1       0   209.4    .045       0   224.4      .1       0
Bank Sta=209.4,224.4
XS Rating Curve= 0 ,0
Exp/Cntr=0.3,0.1

Type RM Length L Ch R = 1 ,48615.5 ,286,302.3,318.7
XS GIS Cut Line= 2
     2076752.183      378721.712      2076383.68      378890.545
#Sta/Elev= 21
       0 2876.25    29.7 2876.62   138.4 2878.22   197.7 2878.79   217.5 2878.79
   227.4 2877.97   237.3 2875.82   247.2 2872.38     257 2868.48   266.9 2865.89
   271.5 2865.82   276.8 2865.75   286.5 2867.34   296.6 2870.27   306.5 2872.23
   316.4 2873.08   326.2 2874.13   336.1 2875.79     346 2877.69   375.7 2882.85
   405.3 2887.76
#Mann= 3 , 0 , 0
       0      .1       0   271.5    .045       0   286.5      .1       0
Bank Sta=271.5,286.5
XS Rating Curve= 0 ,0
Exp/Cntr=0.3,0.1

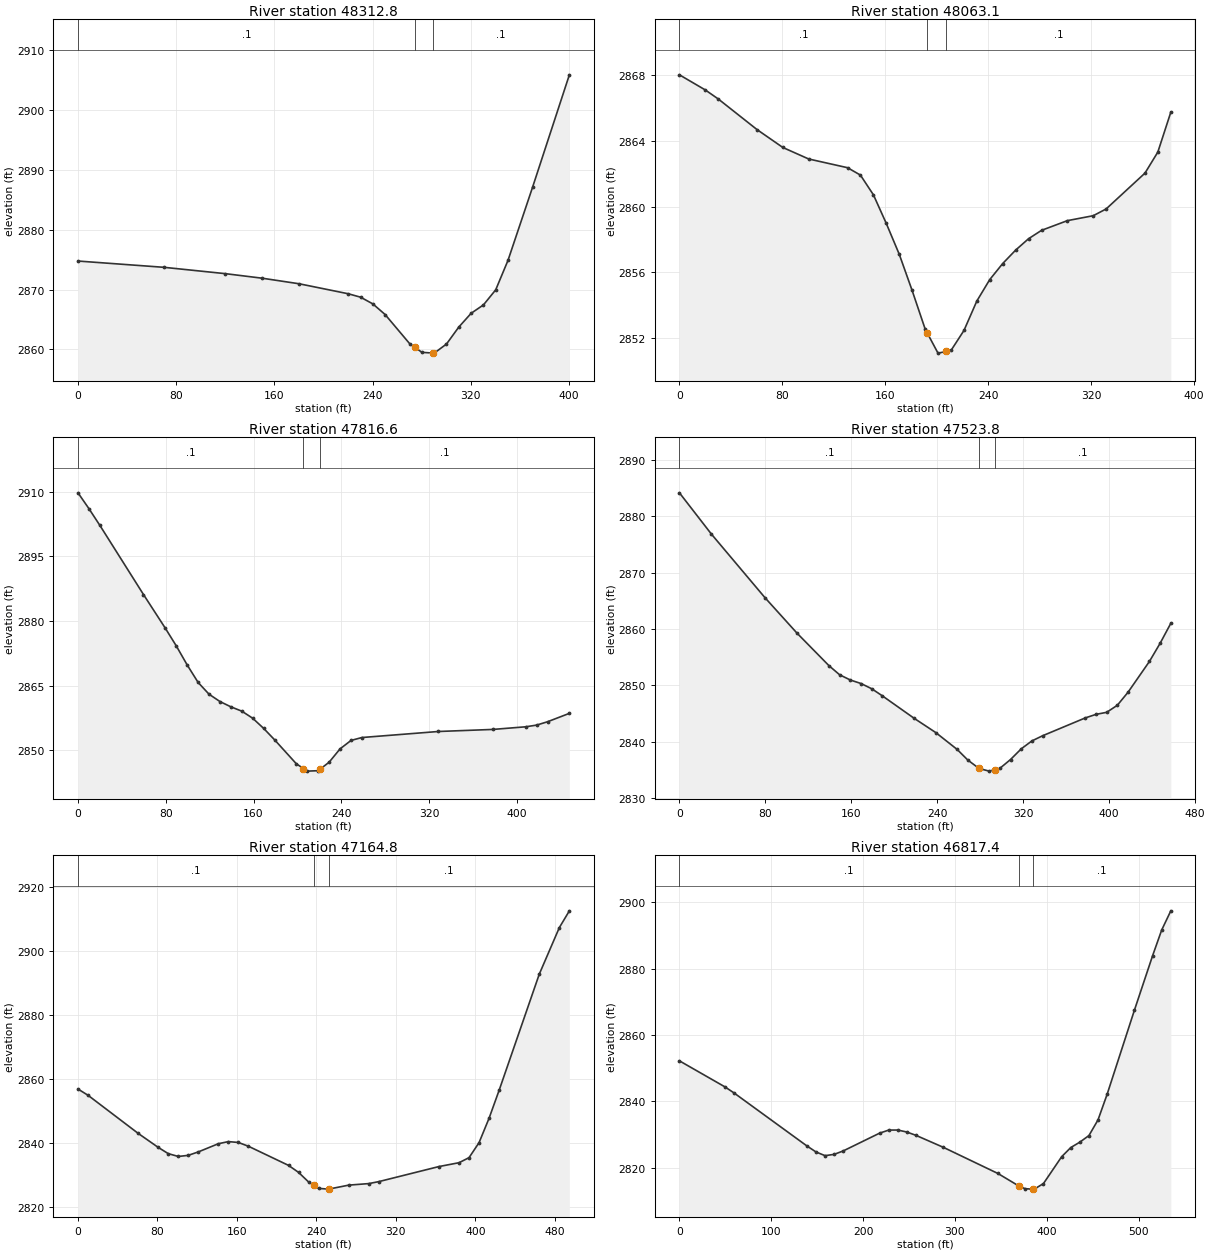
Type RM Length L Ch R = 1 ,48312.8 ,247.5,249.9,252.3
XS GIS Cut Line= 2
     2076686.207      378636.842     2076302.556      378522.515
#Sta/Elev= 22
       0 2874.76    70.1 2873.71   120.1 2872.65   150.1 2871.89   180.2 2870.96
   220.2 2869.29   230.2 2868.72   240.2  2867.6   250.2 2865.82   270.2 2860.95
   274.2 2860.37   280.2  2859.5   289.2 2859.38   290.2 2859.37   300.2 2860.89
   310.2 2863.72   320.3 2866.03   330.3 2867.43   340.3 2869.95   350.3 2874.87
   370.3 2887.08   400.3 2905.88
#Mann= 3 , 0 , 0
       0      .1       0   274.2    .045       0   289.2      .1       0
Bank Sta=274.2,289.2
XS Rating Curve= 0 ,0
Exp/Cntr=0.3,0.1

Type RM Length L Ch R = 1 ,48063.1 ,263,246.4,229.9
XS GIS Cut Line= 2
     2076695.596      378406.606     2076344.143      378256.962
#Sta/Elev= 30
       0 2868.02    20.1  2867.1    30.2 2866.55    60.3 2864.69    80.4  2863.6
   100.5  2862.9   130.7 2862.37   140.7 2861.92   150.8 2860.72   160.8 2858.98
   170.9  2857.1   180.9  2854.9     191 2852.56   192.6 2852.32     201 2851.09
   207.6 2851.19   211.1 2851.25   221.2 2852.47   231.2 2854.26   241.2 2855.56
   251.3 2856.54   261.4 2857.36   271.4 2858.05   281.5 2858.56   301.6 2859.15
   321.7 2859.45   331.7 2859.86   361.9 2862.04   371.9 2863.32     382 2865.75
#Mann= 3 , 0 , 0
       0      .1       0   192.6    .045       0   207.6      .1       0
Bank Sta=192.6,207.6
XS Rating Curve= 0 ,0
Exp/Cntr=0.3,0.1

Type RM Length L Ch R = 1 ,47816.6 ,292.6,292.6,292.7
XS GIS Cut Line= 2
     2076768.666      378035.015     2076344.143      378177.425
#Sta/Elev= 30
       0 2909.74      10 2906.06    19.9  2902.2    59.7 2886.13    79.6 2878.31
    89.6  2874.2    99.5 2869.79   109.5 2865.72   119.4    2863   129.4 2861.29
   139.3 2860.07   149.3 2859.06   159.2 2857.42   169.2 2855.06   179.1 2852.43
     199 2846.84   205.5 2845.74     209 2845.14   218.9 2845.24   220.5 2845.56
   228.9 2847.22   238.8  2850.3   248.8 2852.26   258.7 2852.94   328.4 2854.34
   378.1 2854.82     408 2855.43   417.9 2855.82   427.9  2856.6   447.8 2858.55
#Mann= 3 , 0 , 0
       0      .1       0   205.5    .045       0   220.5      .1       0
Bank Sta=205.5,220.5
XS Rating Curve= 0 ,0
Exp/Cntr=0.3,0.1

Type RM Length L Ch R = 1 ,47523.8 ,361.6,358.9,356.2
XS GIS Cut Line= 2
     2076717.699      377747.746     2076284.099      377893.201
#Sta/Elev= 30
       0 2884.16    29.8 2876.83    79.5 2865.59   109.4 2859.28   139.2  2853.5
   149.1 2851.89   159.1 2850.96     169 2850.34     179 2849.41   188.9 2848.15
   218.7 2844.14   238.6 2841.64   258.5 2838.65   268.4 2836.77   278.9 2835.27
   288.3  2834.8   293.9 2835.08   298.3  2835.3   308.2 2836.86   318.2 2838.76
   328.1 2840.16     338 2841.07   377.8 2844.24   387.8 2844.87   397.7 2845.23
   407.6 2846.48   417.6  2848.8   437.5 2854.26   447.4 2857.46   457.4 2861.02
#Mann= 3 , 0 , 0
       0      .1       0   278.9    .045       0   293.9      .1       0
Bank Sta=278.9,293.9
XS Rating Curve= 0 ,0
Exp/Cntr=0.3,0.1

Type RM Length L Ch R = 1 ,47164.8 ,347.3,347.3,347.3
XS GIS Cut Line= 2
     2076591.151      377401.252     2076145.417      377615.838
#Sta/Elev= 30
       0 2856.93    10.1 2854.98    60.6 2843.08    80.8  2838.7    90.9 2836.75
     101 2835.87     111 2836.22   121.2  2837.3   141.3 2839.85   151.4 2840.51
   161.5 2840.24   171.6 2839.06     212 2833.08   222.1 2830.89   232.2 2827.89
   237.3 2826.89   242.3  2825.9   252.3 2825.67   272.6 2826.92   292.8  2827.4
   302.9 2828.02   363.4 2832.72   383.6 2833.92   393.7  2835.5   403.8  2840.2
   413.9 2847.84     424 2856.55   464.4  2892.8   484.6 2907.34   494.7 2912.58
#Mann= 3 , 0 , 0
       0      .1       0   237.3    .045       0   252.3      .1       0
Bank Sta=237.3,252.3
XS Rating Curve= 0 ,0
Exp/Cntr=0.3,0.1

Type RM Length L Ch R = 1 ,46817.4 ,417.2,412.9,408.7
XS GIS Cut Line= 2
     2076435.074      377139.794     2075952.833      377371.956
#Sta/Elev= 30
       0 2852.19    49.6 2844.33    59.5  2842.5   138.8 2826.52   148.7  2824.7
   158.6 2823.58   168.5 2823.97   178.4 2825.01     218 2830.37     228  2831.3
   237.9 2831.31   247.8  2830.7   257.7  2829.7   287.4  2826.1   346.9  2818.2
   369.8  2814.4   376.6 2813.59   384.8  2813.5   386.5 2813.48   396.5 2815.17
   416.3 2823.26   426.2 2826.02   436.1 2827.66     446 2829.64   455.9 2834.37
   465.8 2842.08   495.6 2867.52   515.4 2883.96   525.3  2891.7   535.2 2897.46
#Mann= 3 , 0 , 0
       0      .1       0   369.8    .045       0   384.8      .1       0
Bank Sta=369.8,384.8
XS Rating Curve= 0 ,0
Exp/Cntr=0.3,0.1

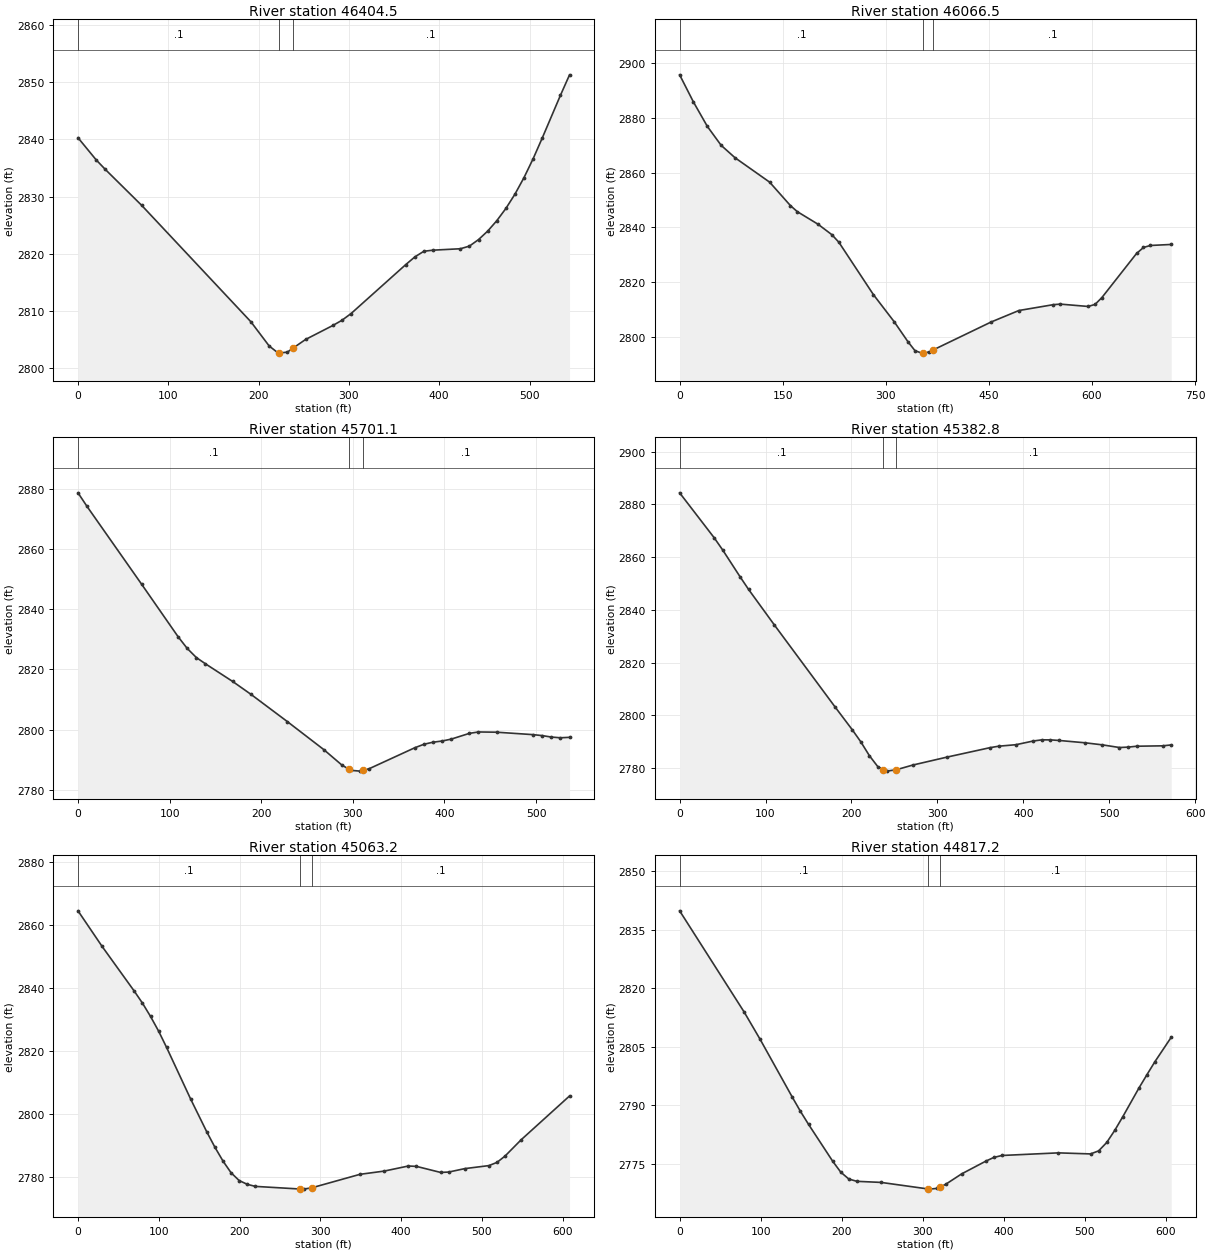
Type RM Length L Ch R = 1 ,46404.5 ,339.7,338,336.7
XS GIS Cut Line= 2
     2076165.302      376782.189     2075724.206      377101.131
#Sta/Elev= 30
       0 2840.29    20.2  2836.4    30.2 2834.75    70.6 2828.44   191.5 2808.07
   211.7 2803.84   221.8 2802.59   222.8 2802.61   231.8 2802.76   237.8 2803.43
     252 2804.98   282.2 2807.43   292.3 2808.34   302.4 2809.52   362.9 2818.08
     373 2819.43     383 2820.42   393.1 2820.61   423.4 2820.86   433.4 2821.32
   443.5 2822.46   453.6 2823.94   463.7 2825.76   473.8 2827.91   483.8  2830.4
   493.9 2833.32     504 2836.62   514.1 2840.25   534.2 2847.71   544.3  2851.3
#Mann= 3 , 0 , 0
       0      .1       0   222.8    .045       0   237.8      .1       0
Bank Sta=222.8,237.8
XS Rating Curve= 0 ,0
Exp/Cntr=0.3,0.1

Type RM Length L Ch R = 1 ,46066.5 ,398.5,365.4,411.9
XS GIS Cut Line= 2
     2076030.277      376444.943     2075478.923      376900.403
#Sta/Elev= 30
       0 2895.65    20.1 2885.74    40.3 2876.85    60.4 2869.94    80.6 2865.41
   130.9 2856.52   161.2 2847.96   171.2 2845.76   201.4 2841.16   221.6 2837.33
   231.7 2834.59     282 2815.47   312.2  2805.6   332.4 2798.25   342.5 2795.04
   352.5 2794.16   354.2 2794.23   362.6 2794.56   369.2 2795.36   453.3 2805.52
   493.6  2809.7   543.9 2811.84     554 2812.03   594.3 2811.18   604.4 2811.92
   614.4 2814.43   664.8  2830.5   674.9 2832.69   684.9 2833.42   715.2 2833.79
#Mann= 3 , 0 , 0
       0      .1       0   354.2    .045       0   369.2      .1       0
Bank Sta=354.2,369.2
XS Rating Curve= 0 ,0
Exp/Cntr=0.3,0.1

Type RM Length L Ch R = 1 ,45701.1 ,318.3,318.3,318.3
XS GIS Cut Line= 2
      2075795.92      376248.023     2075325.322      376505.764
#Sta/Elev= 30
       0 2878.61     9.9 2874.08    69.6 2848.21   109.3 2830.84   119.2 2826.98
   129.2 2823.94   139.1 2821.87   168.9 2815.99   188.8 2811.73   228.5 2802.69
   268.3 2793.39   288.2 2788.22   295.6 2786.93   298.1  2786.5     308 2786.24
   310.6 2786.45     318 2787.06   367.6 2793.99   377.6 2795.15   387.5 2795.84
   397.4 2796.23   407.4 2796.86   427.3 2798.78   437.2 2799.24   457.1 2799.16
   496.8 2798.35   506.8 2798.03   516.7 2797.55   526.6 2797.31   536.6 2797.46
#Mann= 3 , 0 , 0
       0      .1       0   295.6    .045       0   310.6      .1       0
Bank Sta=295.6,310.6
XS Rating Curve= 0 ,0
Exp/Cntr=0.3,0.1

Type RM Length L Ch R = 1 ,45382.8 ,319.5,319.6,319.7
XS GIS Cut Line= 2
     2075647.194      375974.053     2075145.301      376248.934
#Sta/Elev= 30
       0 2884.42    40.2 2867.37    50.2 2862.69    70.3 2852.59    80.3 2847.74
   110.4 2834.22   180.7 2803.26   200.8 2794.57   210.8 2789.97   220.9 2784.66
   230.9 2780.41   237.3 2779.38   240.9  2778.8   252.3 2779.33   271.1 2781.08
   311.2 2784.12   361.4 2787.71   371.4 2788.26   391.5 2788.83   411.6 2790.23
   421.6 2790.67   431.7 2790.66   441.7 2790.44   471.8 2789.56   491.9 2788.78
     512 2787.76     522 2787.91   532.1 2788.25   562.2  2788.4   572.2 2788.74
#Mann= 3 , 0 , 0
       0      .1       0   237.3    .045       0   252.3      .1       0
Bank Sta=237.3,252.3
XS Rating Curve= 0 ,0
Exp/Cntr=0.3,0.1

Type RM Length L Ch R = 1 ,45063.2 ,242.4,246,249.5
XS GIS Cut Line= 2
      2075496.07      375695.667     2074962.378      375987.963
#Sta/Elev= 30
       0 2864.38    29.9 2853.06    69.8 2838.84    79.8 2835.08    89.8 2830.85
    99.8 2826.19   109.7    2821   139.6 2804.55   159.6 2794.12   169.6 2789.28
   179.6  2784.9   189.5 2781.23   199.5 2778.76   209.5 2777.56   219.5  2776.9
   274.5 2776.07   279.3 2776.03   289.5 2776.46   349.1 2780.73   379.1 2781.76
     409 2783.37     419 2783.25   448.9 2781.33   458.9 2781.45   478.8 2782.54
   508.7  2783.5   518.7 2784.52   528.7 2786.54   548.6  2791.7   608.5 2805.61
#Mann= 3 , 0 , 0
       0      .1       0   274.5    .045       0   289.5      .1       0
Bank Sta=274.5,289.5
XS Rating Curve= 0 ,0
Exp/Cntr=0.3,0.1

Type RM Length L Ch R = 1 ,44817.2 ,207.6,208.8,210
XS GIS Cut Line= 2
     2075404.477      375526.944     2074832.124       375728.94
#Sta/Elev= 30
       0  2839.8    79.6  2813.9    99.5 2806.84   139.3    2792   149.2 2788.42
   159.2 2785.09     189 2775.65     199 2772.84     209 2771.08   218.9  2770.5
   248.8 2770.22   306.9 2768.54   308.4  2768.5   318.4  2768.7   321.9 2769.06
   328.4 2769.72   348.2  2772.4   378.1 2775.67     388 2776.62     398 2777.12
   467.6 2777.79   507.4 2777.52   517.4  2778.3   527.4 2780.45   537.3 2783.55
   547.2 2787.04   567.2 2794.41   577.1 2797.83     587 2801.18     607 2807.39
#Mann= 3 , 0 , 0
       0      .1       0   306.9    .045       0   321.9      .1       0
Bank Sta=306.9,321.9
XS Rating Curve= 0 ,0
Exp/Cntr=0.3,0.1