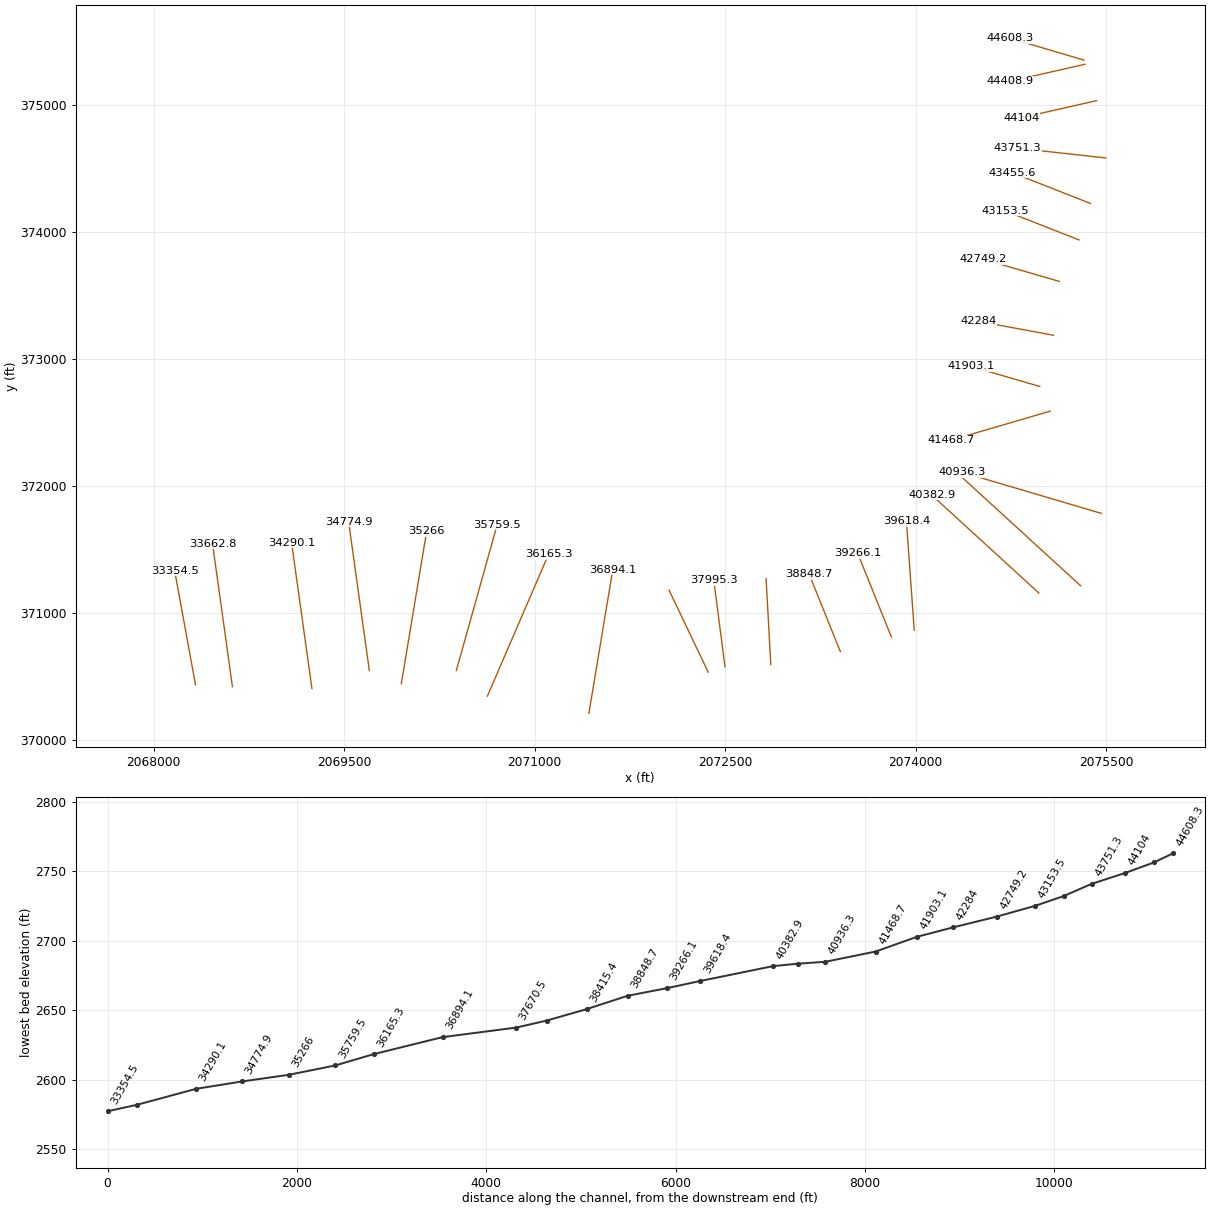
HEC-RAS study BigClearCk.prj: BigClearCk

--- BigClearCk.g01 (geometry) --- (continued)

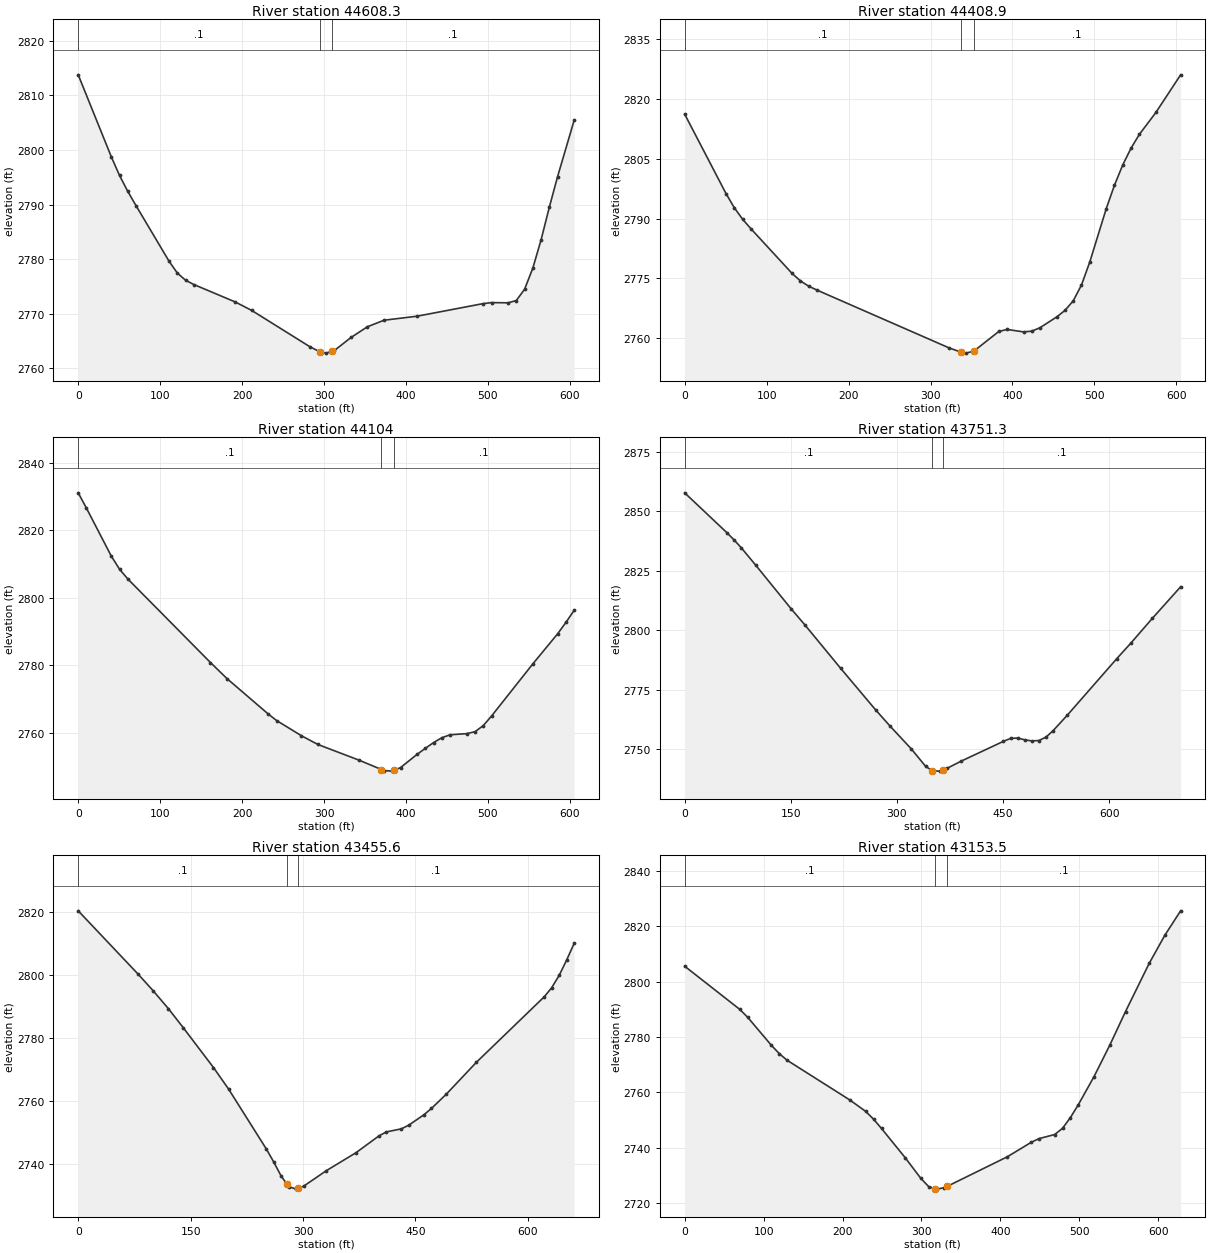
Type RM Length L Ch R = 1 ,44608.3 ,187.4,199.3,211.2
XS GIS Cut Line= 2
     2075326.956       375349.79     2074746.487      375521.116
#Sta/Elev= 30
       0 2813.77    40.4 2798.74    50.4 2795.33    60.5  2792.4    70.6 2789.78
     111 2779.57     121 2777.43   131.1 2776.11   141.2 2775.33   191.6 2772.14
   211.8 2770.58   282.4 2763.96   295.1 2762.98   302.6 2762.76   310.1 2763.12
   312.7 2763.25   332.9 2765.63     353  2767.6   373.2 2768.79   413.6 2769.53
   494.3 2771.84   504.4 2772.02   524.5 2771.98   534.6  2772.4   544.7 2774.46
   554.8 2778.35   564.9 2783.56     575 2789.56     585 2795.12   605.2 2805.44
#Mann= 3 , 0 , 0
       0      .1       0   295.1    .045       0   310.1      .1       0
Bank Sta=295.1,310.1
XS Rating Curve= 0 ,0
Exp/Cntr=0.3,0.1

Type RM Length L Ch R = 1 ,44408.9 ,305.4,304.9,304.5
XS GIS Cut Line= 2
     2075334.087      375316.922     2074743.895      375182.867
#Sta/Elev= 30
       0 2816.22    50.4 2796.31    60.5 2792.76    70.6 2789.88    80.7  2787.5
   131.1 2776.25   141.2 2774.39   151.3 2773.06   161.4 2772.08   322.8 2757.56
   337.8 2756.47     343 2756.26   352.8 2756.75   383.3 2761.69   393.4  2762.2
   413.6 2761.59   423.7 2761.78   433.7 2762.65   453.9 2765.33     464 2766.97
   474.1 2769.36   484.2 2773.34   494.3  2779.1   514.4 2792.48   524.5 2798.41
   534.6 2803.49   544.7 2807.69   554.8 2811.13     575 2816.64   605.2 2826.09
#Mann= 3 , 0 , 0
       0      .1       0   337.8    .045       0   352.8      .1       0
Bank Sta=337.8,352.8
XS Rating Curve= 0 ,0
Exp/Cntr=0.3,0.1

Type RM Length L Ch R = 1 ,44104   ,360.2,352.7,345.3
XS GIS Cut Line= 2
      2075425.65      375030.652     2074835.458      374896.597
#Sta/Elev= 30
       0 2831.08    10.1 2826.52    40.4 2812.33    50.4 2808.47    60.5 2805.58
   161.4 2780.83   181.6 2776.07     232 2765.57   242.1 2763.66   272.4 2759.16
   292.5 2756.57     343  2751.9   370.1 2749.15   373.2 2748.86   383.3 2748.68
   385.1 2748.87   393.4 2749.74   413.6 2753.66   423.7 2755.45   433.7 2757.14
   443.8 2758.58   453.9 2759.44   474.1 2759.78   484.2 2760.35   494.3 2762.16
   504.4    2765   554.8 2780.44     585 2789.33   595.1 2792.69   605.2  2796.3
#Mann= 3 , 0 , 0
       0      .1       0   370.1    .045       0   385.1      .1       0
Bank Sta=370.1,385.1
XS Rating Curve= 0 ,0
Exp/Cntr=0.3,0.1

Type RM Length L Ch R = 1 ,43751.3 ,301.7,295.7,289.7
XS GIS Cut Line= 2
      2075498.15      374580.045     2074801.269      374656.667
#Sta/Elev= 30
       0 2857.78    60.1 2840.91    70.1 2837.91    80.1 2834.66   100.2 2827.47
   150.2 2809.16   170.3 2802.16   220.3 2784.12   270.4 2766.43   290.4 2759.76
   320.5 2750.15   340.5 2742.91   350.3 2740.97   360.6 2740.86   365.3 2741.39
   370.6 2741.99   390.6 2745.02   450.7 2753.39   460.7 2754.61   470.7 2754.76
   480.7 2754.02   490.8 2753.54   500.8 2753.72   510.8 2755.16   520.8 2757.84
   540.8 2764.32   610.9 2788.13     631 2794.72     661    2805   701.1  2818.3
#Mann= 3 , 0 , 0
       0      .1       0   350.3    .045       0   365.3      .1       0
Bank Sta=350.3,365.3
XS Rating Curve= 0 ,0
Exp/Cntr=0.3,0.1

Type RM Length L Ch R = 1 ,43455.6 ,302.1,302.1,302.1
XS GIS Cut Line= 2
     2075378.611       374221.43     2074762.606      374463.352
#Sta/Elev= 30
       0 2820.48    80.2  2800.3   100.3 2795.01   120.3 2789.42   140.4 2783.28
   180.5  2770.7   200.6 2763.88   250.7 2744.95   260.7 2740.79   270.7 2736.27
   278.2 2733.75   280.8 2732.88   290.8 2732.07   293.2 2732.29   300.8    2733
   330.9  2737.9     371 2743.69   401.1 2748.95   411.1 2750.24   431.2 2751.22
   441.2  2752.4   461.3 2755.69   471.3 2757.69   491.3 2762.26   531.4 2772.38
   621.7 2793.13   631.7 2796.01   641.8 2799.97   651.8 2804.86   661.8 2810.14
#Mann= 3 , 0 , 0
       0      .1       0   278.2    .045       0   293.2      .1       0
Bank Sta=278.2,293.2
XS Rating Curve= 0 ,0
Exp/Cntr=0.3,0.1

Type RM Length L Ch R = 1 ,43153.5 ,402.3,404.3,406.4
XS GIS Cut Line= 2
     2075287.789      373934.793     2074702.839      374164.518
#Sta/Elev= 30
       0 2805.54    69.8 2789.95    79.8  2787.1   109.7 2777.03   119.7 2774.01
   129.7 2771.59   209.5 2757.18   229.4 2753.09   239.4 2750.27   249.4 2746.93
   279.3 2736.42   299.3 2728.89   309.2 2725.94   317.5 2725.18   319.2 2725.03
   329.2 2725.56   332.5 2726.01     409 2736.74   438.9  2741.9   448.9 2743.27
   468.8 2744.75   478.8 2747.01   488.8 2750.89   498.8 2755.53   518.7 2765.68
   538.7 2777.05   558.6 2789.17   588.5 2806.52   608.5 2816.76   628.4 2825.54
#Mann= 3 , 0 , 0
       0      .1       0   317.5    .045       0   332.5      .1       0
Bank Sta=317.5,332.5
XS Rating Curve= 0 ,0
Exp/Cntr=0.3,0.1

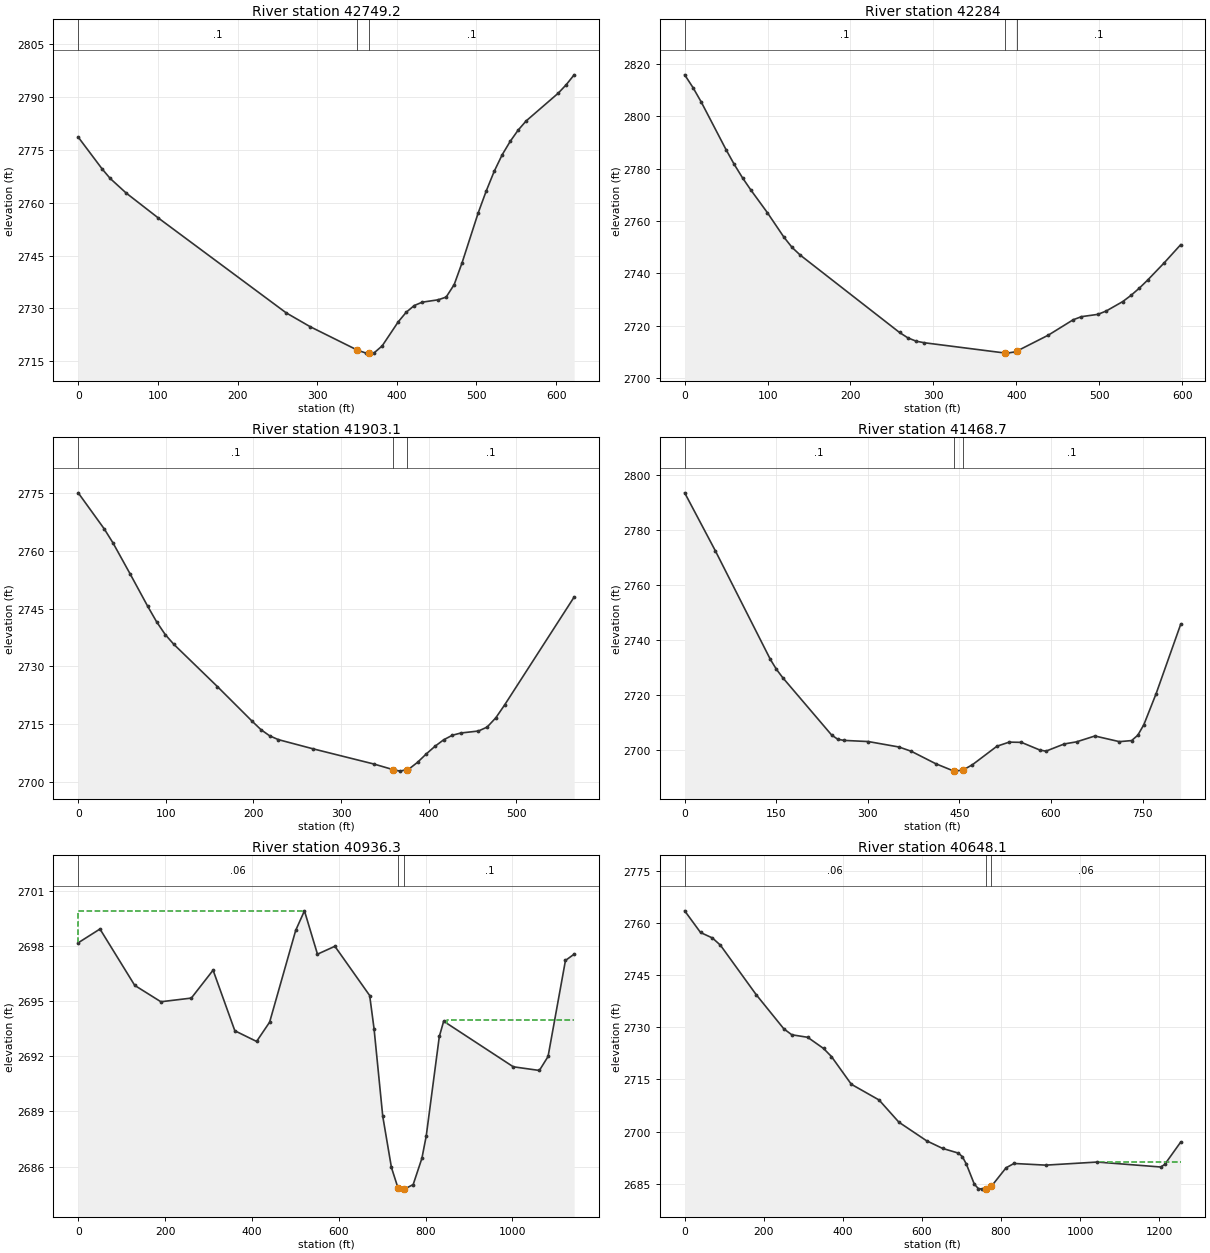
Type RM Length L Ch R = 1 ,42749.2 ,463,465.2,467.5
XS GIS Cut Line= 2
     2075131.524      373608.648     2074533.644      373782.408
#Sta/Elev= 30
       0 2778.67    30.1  2769.6    40.2 2766.91    60.2 2762.78   100.4 2755.72
   261.1 2728.74   291.2 2724.81   350.6 2718.14   361.5  2717.3   365.6 2717.34
   371.6  2717.4   381.6 2719.36   401.7 2726.17   411.7  2728.9   421.8 2730.81
   431.8 2731.77   451.9 2732.45   461.9 2733.22     472 2736.77     482 2743.04
   502.1 2757.11   512.2 2763.35   522.2 2768.93   532.2 2773.63   542.3 2777.45
   552.3 2780.66   562.4 2783.28   602.5 2791.12   612.6 2793.54   622.6 2796.36
#Mann= 3 , 0 , 0
       0      .1       0   350.6    .045       0   365.6      .1       0
Bank Sta=350.6,365.6
XS Rating Curve= 0 ,0
Exp/Cntr=0.3,0.1

Type RM Length L Ch R = 1 ,42284   ,383.1,380.9,378.6
XS GIS Cut Line= 2
      2075085.02      373184.931     2074496.818      373293.947
#Sta/Elev= 30
       0 2815.92      10 2811.06    19.9 2805.57    49.8 2787.36    59.8 2781.66
    69.8 2776.51    79.8 2771.88    99.7 2763.23   119.6 2753.88   129.6 2749.89
   139.6 2746.92   259.2 2717.37   269.2 2715.32   279.2 2714.05   289.1 2713.45
   385.8 2709.54   388.8 2709.48   398.8 2709.97   400.8 2710.27   438.7 2716.37
   468.6 2722.24   478.6 2723.43   498.5 2724.31   508.5  2725.6   528.4  2729.2
   538.4 2731.58   548.4 2734.34   558.3 2737.38   578.3 2743.98   598.2 2750.93
#Mann= 3 , 0 , 0
       0      .1       0   385.8    .045       0   400.8      .1       0
Bank Sta=385.8,400.8
XS Rating Curve= 0 ,0
Exp/Cntr=0.3,0.1

Type RM Length L Ch R = 1 ,41903.1 ,421.5,434.4,447.3
XS GIS Cut Line= 2
     2074978.212      372781.853      2074434.69      372939.816
#Sta/Elev= 30
       0 2775.15    29.8 2765.73    39.7 2762.11    59.6  2753.9    79.4 2745.58
    89.4 2741.61    99.3 2738.26   109.2  2735.7   158.9 2724.71   198.6 2715.68
   208.5 2713.52   218.5  2711.9   228.4 2710.91   268.1 2708.51   337.6 2704.55
   359.8 2703.07   367.4 2702.71   374.8  2703.1   377.3 2703.23   387.3 2705.01
   397.2 2707.18   407.1 2709.16   417.1 2710.87     427 2712.05   436.9 2712.64
   456.8 2713.15   466.7 2714.18   476.6 2716.59   486.6 2719.92     566 2748.03
#Mann= 3 , 0 , 0
       0      .1       0   359.8    .045       0   374.8      .1       0
Bank Sta=359.8,374.8
XS Rating Curve= 0 ,0
Exp/Cntr=0.3,0.1

Type RM Length L Ch R = 1 ,41468.7 ,544,532.2,517.9
XS GIS Cut Line= 2
     2075060.963      372587.387      2074281.12      372359.801
#Sta/Elev= 30
       0 2793.63    50.2 2772.51   140.4 2732.86   150.4 2729.24   160.5 2726.26
   240.7 2705.31   250.7 2703.77   260.8 2703.35   300.9 2702.92     351 2700.94
   371.1 2699.39   411.2 2694.85   440.8 2692.17   441.3 2692.14   455.8 2692.52
   471.4 2694.48   511.5 2701.22   531.6 2702.72   551.6 2702.63   581.7 2699.84
   591.7 2699.42   621.8 2702.05   641.9 2702.82     672 2704.95   712.1 2702.89
   732.1 2703.28   742.2 2705.22   752.2 2709.09   772.3 2720.41   812.4 2745.62
#Mann= 3 , 0 , 0
       0      .1       0   440.8    .045       0   455.8      .1       0
Bank Sta=440.8,455.8
XS Rating Curve= 0 ,0
Exp/Cntr=0.3,0.1

Type RM Length L Ch R = 1 ,40936.3 ,299.6,288.2,276.9
XS GIS Cut Line= 2
     2075462.957      371783.139     2074367.553      372106.458
#Sta/Elev= 30
       0 2698.18    50.1 2698.93   130.2 2695.86   190.4 2694.97   260.5 2695.17
   310.6 2696.69   360.7 2693.39   410.8 2692.81   440.8 2693.86   500.9 2698.86
     521 2699.92     551 2697.56   591.1 2697.99   671.2 2695.31   681.3  2693.5
   701.3 2688.74   721.3 2685.95   736.2 2684.85   741.4 2684.77   751.2 2684.77
   771.4 2685.02   791.5 2686.45   801.5 2687.67   831.6 2693.08   841.6 2693.91
  1001.9 2691.43    1062 2691.23    1082 2691.99  1122.1 2697.22  1142.1 2697.56
#Mann= 3 , 0 , 0
       0     .06       0   736.2    .045       0   751.2      .1       0
#XS Ineff= 2 , 0
          519.75  2699.9  850.31         2693.97
Permanent Ineff=
       F       F
Bank Sta=736.2,751.2
XS Rating Curve= 0 ,0
Exp/Cntr=0.3,0.1

Type RM Length L Ch R = 1 ,40648.1 ,265.3,265.2,265.2
XS GIS Cut Line= 2
     2075300.471      371212.801     2074374.716      372059.255
#Sta/Elev= 30
       0 2763.56    40.1 2757.32    70.2 2755.74    90.3 2753.68   180.6 2739.46
   250.9 2729.56     271 2727.86   311.1 2727.14   351.2 2723.92   371.3 2721.59
   421.5 2713.61   491.7 2709.08   541.9 2702.68   612.1 2697.32   652.3 2695.14
   692.4 2693.78   702.5 2692.74   712.5 2690.61   732.6 2684.84   742.6 2683.59
   752.6 2683.41   760.9 2683.45   775.9 2684.24   812.8 2689.54   832.9  2690.8
   913.2 2690.32  1043.7 2691.21  1204.2 2689.78  1214.2 2690.52  1254.4 2696.93
#Mann= 3 , 0 , 0
       0     .06       0   760.9    .045       0   775.9     .06       0
#XS Ineff= 2 , 0
                         1049.07         2691.17
Permanent Ineff=
       F       F
Bank Sta=760.9,775.9
XS Rating Curve= 0 ,0
Exp/Cntr=0.3,0.1

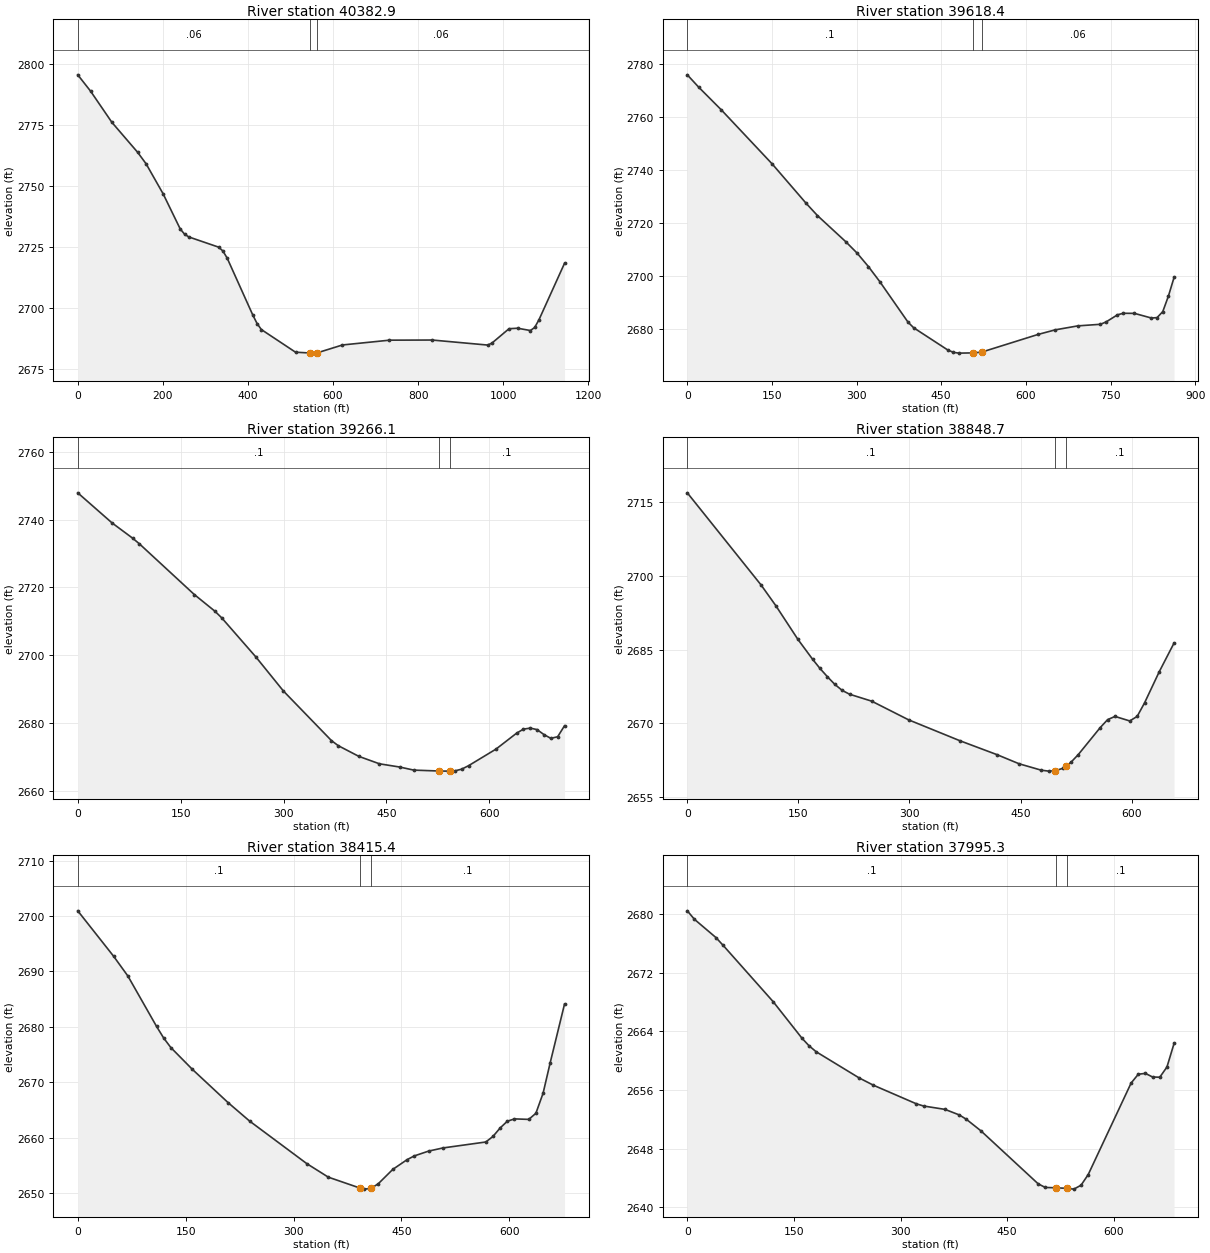
Type RM Length L Ch R = 1 ,40382.9 ,782.3,764.5,746.6
XS GIS Cut Line= 2
     2074970.938      371156.296     2074126.621      371928.287
#Sta/Elev= 30
       0 2795.51    30.1 2788.84    80.3 2776.05   140.5 2763.86   160.6 2759.11
   200.7  2746.8   240.8 2732.45   250.9 2730.33   260.9 2729.18   331.2 2724.99
   341.2 2723.41   351.2  2720.5   411.5 2697.18   421.5 2693.72   431.5 2691.28
   511.8 2682.01     547 2681.67     552 2681.63     562 2681.71   622.2 2684.97
   732.6 2686.93     833 2686.99   963.4 2684.93   973.4 2685.73  1013.6 2691.62
  1033.7 2691.82  1063.8 2690.88  1073.8 2692.12  1083.8 2695.22    1144 2718.37
#Mann= 3 , 0 , 0
       0     .06       0     547    .045       0     562     .06       0
Bank Sta=547,562
XS Rating Curve= 0 ,0
Exp/Cntr=0.3,0.1

Type RM Length L Ch R = 1 ,39618.4 ,345.2,352.3,359.4
XS GIS Cut Line= 2
     2073989.997       370863.01     2073927.812      371723.391
#Sta/Elev= 30
       0 2775.98    20.1 2771.34    60.2 2762.78   150.5 2742.34   210.6 2727.51
   230.7 2722.87   280.8 2713.03   300.9 2708.73     321 2703.63     341    2698
   391.2 2682.66   401.2 2680.55   461.4  2672.2   471.4 2671.29   481.5 2670.99
   506.6 2671.08   521.6 2671.37   621.9 2678.06     652 2679.77   692.1 2681.27
   732.2 2681.87   742.3 2682.78   762.3 2685.44   772.4 2686.02   792.4 2685.99
   822.5 2684.23   832.5 2684.39   842.6 2686.65   852.6 2692.51   862.6 2699.54
#Mann= 3 , 0 , 0
       0      .1       0   506.6    .045       0   521.6     .06       0
Bank Sta=506.6,521.6
XS Rating Curve= 0 ,0
Exp/Cntr=0.3,0.1

Type RM Length L Ch R = 1 ,39266.1 ,417.4,417.4,417.4
XS GIS Cut Line= 2
     2073809.474      370811.041     2073544.122      371469.196
#Sta/Elev= 30
       0 2747.88      50 2739.01      80 2734.51      90 2732.82   169.9  2717.9
   199.9 2712.99   209.9 2711.02   259.9 2699.44   299.8 2689.46   369.8 2674.85
   379.8 2673.34   409.8 2670.19   439.8    2668   469.8 2667.03   489.8 2666.14
   527.3 2665.87   539.7 2665.84   542.3 2665.86   549.7 2665.91   559.7 2666.42
   569.7 2667.44   609.7 2672.33   639.7 2677.02   649.7 2678.22   659.7 2678.52
   669.6 2678.08   679.6 2676.62   689.6 2675.51   699.6 2675.97   709.6 2679.22
#Mann= 3 , 0 , 0
       0      .1       0   527.3    .045       0   542.3      .1       0
Bank Sta=527.3,542.3
XS Rating Curve= 0 ,0
Exp/Cntr=0.3,0.1

Type RM Length L Ch R = 1 ,38848.7 ,440.9,433.3,425.7
XS GIS Cut Line= 2
     2073407.903      370695.437     2073162.134      371305.019
#Sta/Elev= 30
       0 2716.83    99.6 2698.12   119.5 2693.92   149.4 2687.06   169.3 2683.01
   179.2 2681.16   189.2 2679.48   199.2 2677.93   209.1 2676.71   219.1 2675.93
     249 2674.52   298.8 2670.73   368.5 2666.46   418.3 2663.65   448.1  2661.8
     478  2660.5     488 2660.31   496.7 2660.38   507.9 2660.92   511.7 2661.36
   517.8 2662.07   527.8 2663.64   557.7 2669.17   567.6 2670.77   577.6 2671.42
   597.5  2670.5   607.5 2671.43   617.4 2674.15   637.3  2680.5   657.3 2686.33
#Mann= 3 , 0 , 0
       0      .1       0   496.7    .045       0   511.7      .1       0
Bank Sta=496.7,511.7
XS Rating Curve= 0 ,0
Exp/Cntr=0.3,0.1

Type RM Length L Ch R = 1 ,38415.4 ,418.2,420.1,421.9
XS GIS Cut Line= 2
      2072860.24      370593.069     2072823.174      371268.893
#Sta/Elev= 30
       0 2700.94    49.8 2692.75    69.7 2689.17   109.5 2680.09   119.4 2677.99
   129.4 2676.26   159.3 2672.33     209 2666.32   238.9 2662.99   318.5  2655.3
   348.4 2652.86   392.7 2650.88   398.1  2650.7   407.7 2650.82     418 2651.69
     438 2654.26   457.9 2656.02   467.8 2656.69   487.7 2657.56   507.6 2658.13
   567.4 2659.21   577.3 2660.21   587.3 2661.74   597.2 2662.95   607.2 2663.38
   627.1 2663.29     637 2664.39     647 2668.01   656.9 2673.52   676.8  2684.1
#Mann= 3 , 0 , 0
       0      .1       0   392.7    .045       0   407.7      .1       0
Bank Sta=392.7,407.7
XS Rating Curve= 0 ,0
Exp/Cntr=0.3,0.1

Type RM Length L Ch R = 1 ,37995.3 ,317.8,324.7,331.8
XS GIS Cut Line= 2
     2072499.487      370576.103      2072411.52      371255.366
#Sta/Elev= 30
       0  2680.4    10.1 2679.24    40.3 2676.76    50.4  2675.7   120.9 2668.02
   161.2 2663.07   171.2 2662.03   181.3 2661.21   241.7 2657.65   261.9 2656.65
   322.3 2654.12   332.4 2653.82   362.6 2653.36   382.8  2652.6   392.8    2652
     413 2650.45   493.6 2643.23   503.6 2642.73   518.9 2642.68   533.9 2642.61
   543.9  2642.5     554 2643.03   564.1 2644.48   624.5 2656.95   634.6 2658.15
   644.6 2658.26   654.7 2657.77   664.8 2657.74   674.9 2659.13   684.9 2662.34
#Mann= 3 , 0 , 0
       0      .1       0   518.9    .045       0   533.9      .1       0
Bank Sta=518.9,533.9
XS Rating Curve= 0 ,0
Exp/Cntr=0.3,0.1

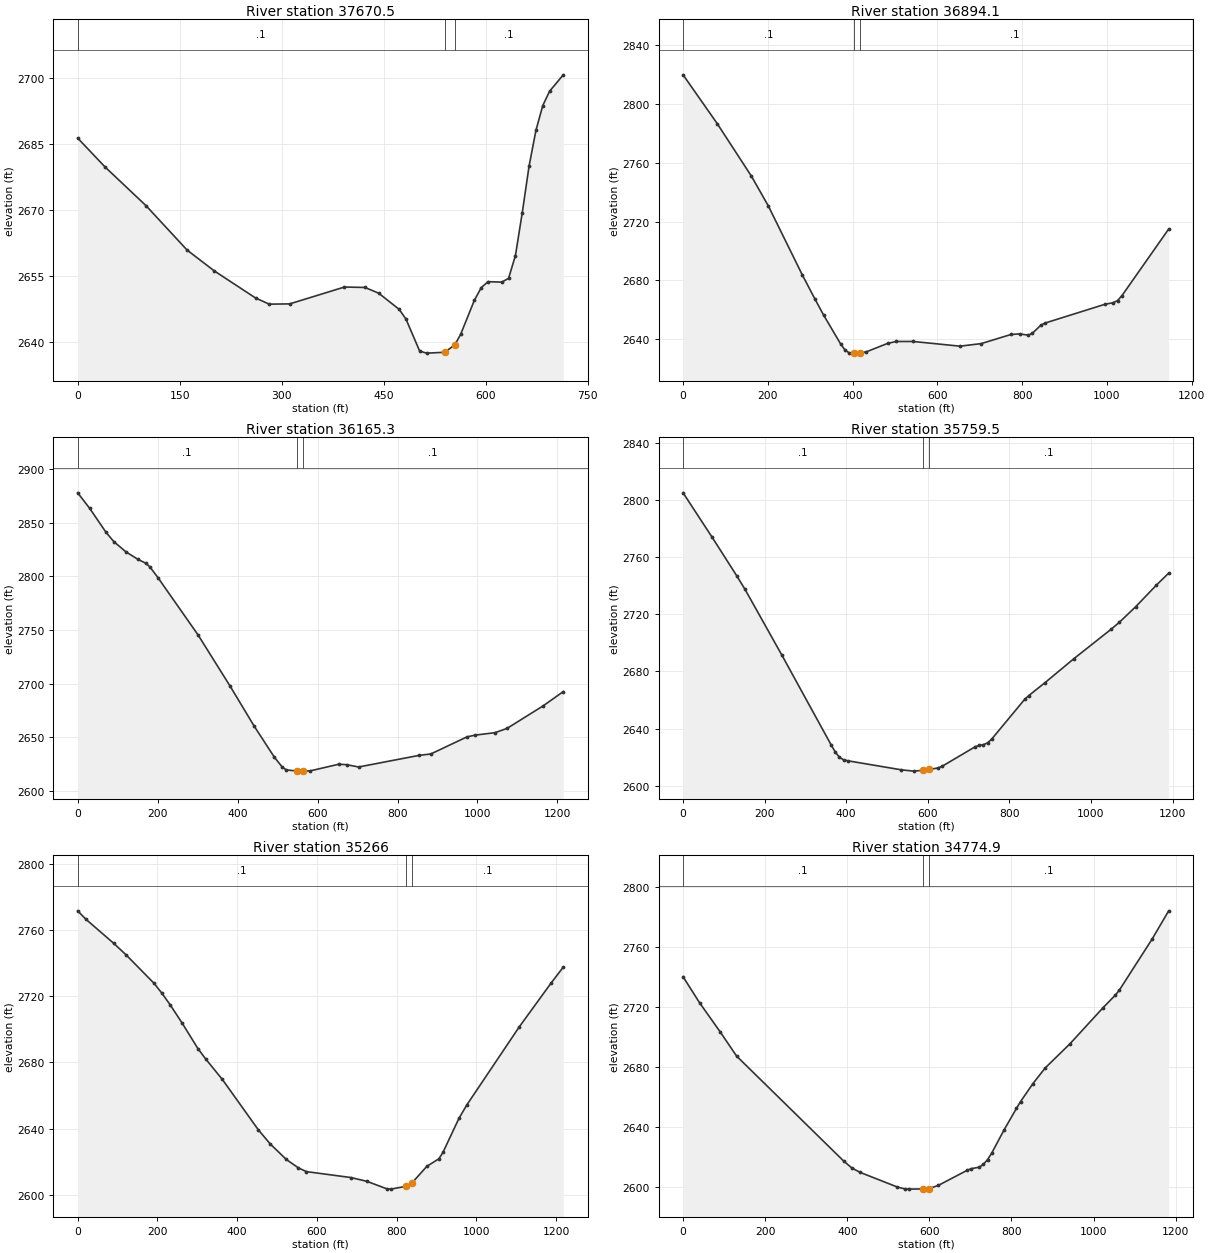
Type RM Length L Ch R = 1 ,37670.5 ,790,776.1,762.1
XS GIS Cut Line= 2
     2072367.072      370533.886     2072059.119       371178.42
#Sta/Elev= 30
       0 2686.36    40.2  2679.8   100.6 2670.97     161 2660.86   201.2  2656.1
   261.6 2649.97   281.7 2648.56   311.9 2648.62   392.4 2652.46   422.6 2652.36
   442.7 2651.06   472.9 2647.38   482.9 2645.16     503 2637.89   513.1 2637.41
   539.9  2637.6   554.9 2639.32   563.4 2641.72   583.5 2649.44   593.6 2652.32
   603.6 2653.68   623.8 2653.57   633.8 2654.43   643.9 2659.62     654 2669.42
     664 2680.02   674.1 2688.13   684.1 2693.76   694.2 2697.05   714.3 2700.77
#Mann= 3 , 0 , 0
       0      .1       0   539.9    .045       0   554.9      .1       0
Bank Sta=539.9,554.9
XS Rating Curve= 0 ,0
Exp/Cntr=0.3,0.1

Type RM Length L Ch R = 1 ,36894.1 ,733.7,728.6,723.6
XS GIS Cut Line= 2
     2071427.656      370209.564     2071615.652      371339.645
#Sta/Elev= 30
       0 2819.81    80.4  2786.7   160.8  2751.1     201 2730.73   281.4 2683.69
   311.5 2667.13   331.6 2656.42   371.8 2636.75   381.9 2632.74   391.9 2630.72
     402 2630.57   402.7 2630.58   417.7 2630.76   432.1 2631.43   482.4 2637.17
   502.5 2638.48   542.7  2638.5   653.2  2635.3   703.4 2637.05   773.8 2643.28
   793.9 2643.63     814 2642.82     824 2644.02   844.1 2649.61   854.2 2651.04
   994.9 2663.75    1015 2664.88    1025 2666.33  1035.1 2669.55  1145.6 2714.93
#Mann= 3 , 0 , 0
       0      .1       0   402.7    .045       0   417.7      .1       0
Bank Sta=402.7,417.7
XS Rating Curve= 0 ,0
Exp/Cntr=0.3,0.1

Type RM Length L Ch R = 1 ,36165.3 ,402.9,405.8,408.8
XS GIS Cut Line= 2
     2070628.344       370345.28     2071109.729      371460.358
#Sta/Elev= 30
       0 2877.98    30.1 2863.43    70.3 2841.43    90.3 2832.48   120.4    2823
   150.6 2815.94   170.6 2812.26   180.7 2808.84   200.8 2798.81   301.1 2745.38
   381.4 2697.52   441.6 2660.21   491.8  2631.4   511.9    2622     522 2619.44
   547.4 2618.48   562.1 2618.32   562.4 2618.32   582.2 2618.61   652.4 2624.71
   672.5 2624.37   702.6 2622.18   853.2 2632.97   883.3 2634.34   973.6 2650.24
   993.7 2651.89  1043.9  2654.2    1074  2658.2  1164.4 2679.25  1214.6 2692.53
#Mann= 3 , 0 , 0
       0      .1       0   547.4    .045       0   562.4      .1       0
Bank Sta=547.4,562.4
XS Rating Curve= 0 ,0
Exp/Cntr=0.3,0.1

Type RM Length L Ch R = 1 ,35759.5 ,491.3,493.5,495.7
XS GIS Cut Line= 2
     2070383.715      370545.856     2070704.999      371692.175
#Sta/Elev= 30
       0 2804.95    70.6 2774.13   131.2 2747.03   151.3 2737.66   242.1 2691.41
   363.2 2628.42   373.3  2623.5   383.4  2619.8   393.5 2618.08   403.6 2617.42
   534.7  2611.1     565 2610.17   587.7 2610.74   602.7 2611.34   625.5  2612.4
   635.6 2613.65   716.3 2627.25   726.4 2628.19   736.5  2628.7   746.6 2629.96
   756.7 2632.62   837.4  2660.4   847.5 2663.03   887.8 2672.19   958.4 2688.94
  1049.2 2709.42  1069.4 2714.29  1109.8 2725.28  1160.2  2740.3  1190.5 2748.74
#Mann= 3 , 0 , 0
       0      .1       0   587.7    .045       0   602.7      .1       0
Bank Sta=587.7,602.7
XS Rating Curve= 0 ,0
Exp/Cntr=0.3,0.1

Type RM Length L Ch R = 1 ,35266   ,484.3,491.1,497.9
XS GIS Cut Line= 2
      2069950.43      370441.886     2070150.263      371643.114
#Sta/Elev= 30
       0 2771.52    20.1 2766.55    90.6 2751.83   120.8 2745.06   191.2  2727.8
   211.3 2721.73   231.5 2714.88   261.7  2703.8   301.9 2688.16     322 2681.72
   362.3 2669.83   452.9 2639.27   483.1 2630.64   523.3 2621.32   553.5 2616.25
   573.6    2614   684.4 2610.44   724.6 2608.18   774.9 2603.64     785 2603.42
   822.7 2605.08   837.7    2607   875.6  2617.2   905.8 2621.75   915.8 2625.55
   956.1 2646.19   976.2 2654.42    1107 2701.33  1187.5 2728.02  1217.7 2737.53
#Mann= 3 , 0 , 0
       0      .1       0   822.7    .045       0   837.7      .1       0
Bank Sta=822.7,837.7
XS Rating Curve= 0 ,0
Exp/Cntr=0.3,0.1

Type RM Length L Ch R = 1 ,34774.9 ,484.9,484.8,484.7
XS GIS Cut Line= 2
     2069698.557      370546.134     2069535.273      371717.725
#Sta/Elev= 30
       0 2740.37    40.1 2723.05    90.2 2703.67   130.3 2687.46     391 2617.46
     411 2612.79   431.1 2609.86   521.3 2600.13   541.3 2598.71   551.4 2598.66
     584 2598.81     599 2599.02   621.5  2601.1   691.7 2611.18   701.7  2612.3
   721.8 2613.33   731.8 2615.27   741.8 2618.39   751.8 2622.68   781.9 2638.15
     812  2652.5     822 2657.04   852.1 2669.04   882.2 2679.54   942.3 2695.59
  1022.5 2719.56  1052.6 2727.99  1062.6 2731.38  1142.8 2765.61  1182.9 2784.36
#Mann= 3 , 0 , 0
       0      .1       0     584    .045       0     599      .1       0
Bank Sta=584,599
XS Rating Curve= 0 ,0
Exp/Cntr=0.3,0.1

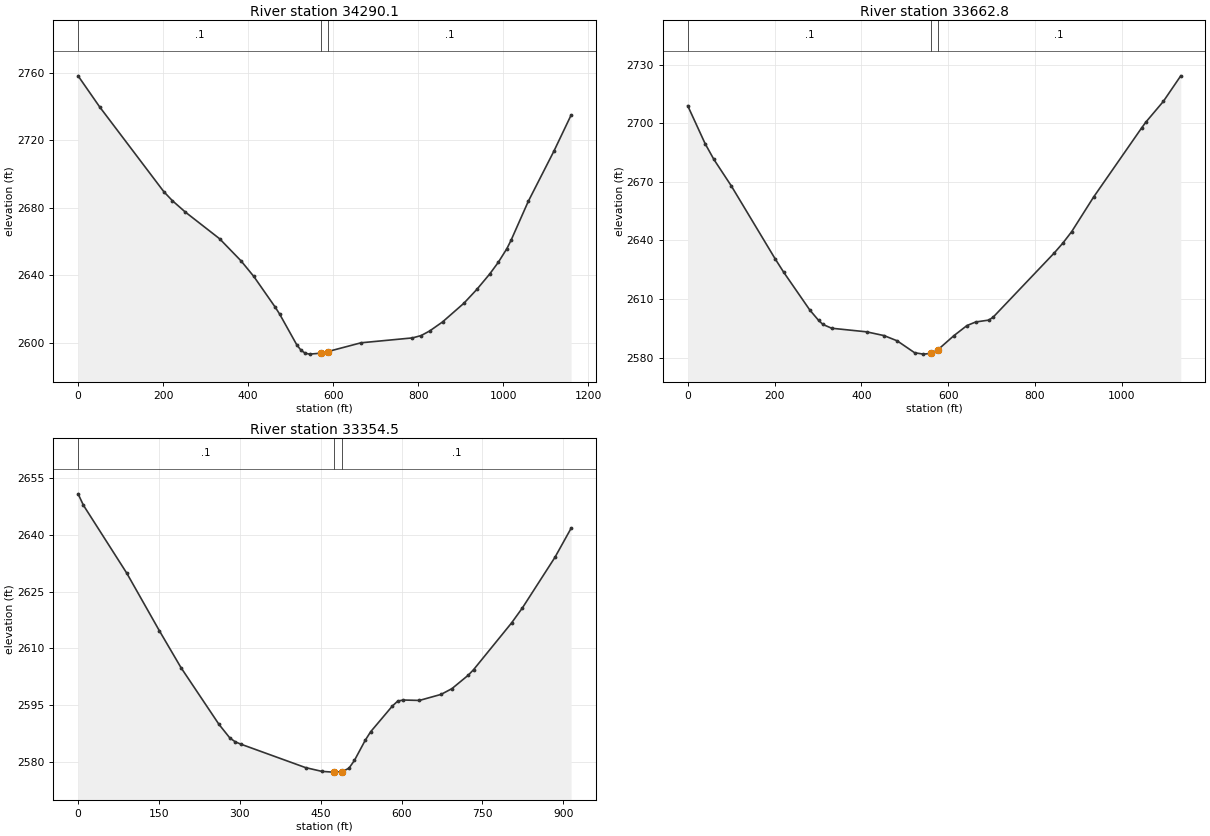
Type RM Length L Ch R = 1 ,34290.1 ,627.3,627.3,627.3
XS GIS Cut Line= 2
     2069246.226       370405.57     2069086.203      371553.769
#Sta/Elev= 30
       0 2758.17    50.4  2739.9   201.6 2689.57   221.8 2684.23     252 2677.54
   332.7 2661.71   383.1 2648.62   413.3 2639.34   463.7 2621.12   473.8 2617.14
   514.1 2598.94   524.2 2595.67   534.3 2593.87   544.4 2593.37   572.1 2593.95
   587.1 2594.88   665.3 2600.08   786.3 2602.98   806.5 2604.35   826.6 2607.07
   856.9 2612.42   907.3 2623.53   937.5 2631.66   967.8  2640.8   987.9 2647.68
  1008.1 2655.77  1018.2 2660.86  1058.5  2683.8    1119 2713.66  1159.3 2734.94
#Mann= 3 , 0 , 0
       0      .1       0   572.1    .045       0   587.1      .1       0
Bank Sta=572.1,587.1
XS Rating Curve= 0 ,0
Exp/Cntr=0.3,0.1

Type RM Length L Ch R = 1 ,33662.8 ,307.3,308.3,309.2
XS GIS Cut Line= 2
     2068620.476      370419.083     2068463.704       371543.95
#Sta/Elev= 30
       0 2708.99    40.2 2689.53    60.3  2681.5   100.5 2667.91     201 2630.76
   221.1 2623.75   281.4 2604.36   301.5 2599.11   311.6    2597   331.7 2595.08
   412.1 2593.24   452.3 2591.31   482.4 2588.65   522.6 2582.55   542.7 2581.83
   560.4 2582.18   575.4  2583.9   613.1 2591.28   643.2 2596.45   663.4 2598.29
   693.5 2599.25   703.6 2600.76   844.3 2633.62   864.4 2638.74   884.5 2644.55
   934.7 2662.16  1045.3 2697.54  1055.3  2700.6  1095.5 2711.18  1135.7 2724.29
#Mann= 3 , 0 , 0
       0      .1       0   560.4    .045       0   575.4      .1       0
Bank Sta=560.4,575.4
XS Rating Curve= 0 ,0
Exp/Cntr=0.3,0.1

Type RM Length L Ch R = 1 ,33354.5 ,402.6,405.6,408.5
XS GIS Cut Line= 2
     2068329.608      370433.912     2068165.111      371333.505
#Sta/Elev= 30
       0 2650.94      10  2647.9    90.4 2629.91   150.7  2614.7   190.9 2604.91
   261.3 2589.89   281.4  2586.3   291.4 2585.27   301.5 2584.66   422.1 2578.42
   452.2 2577.43   472.3 2577.23     475 2577.23     490 2577.36   502.5 2578.28
   512.5 2580.31   532.6 2585.66   542.7 2587.93   582.9 2594.73   592.9 2596.04
     603 2596.33   633.1 2596.22   673.3 2597.82   693.4 2599.34   723.6 2602.89
   733.6 2604.37     804 2616.74   824.1 2620.72   884.4  2634.1   914.5 2641.83
#Mann= 3 , 0 , 0
       0      .1       0     475    .045       0     490      .1       0
Bank Sta=475,490
XS Rating Curve= 0 ,0
Exp/Cntr=0.3,0.1