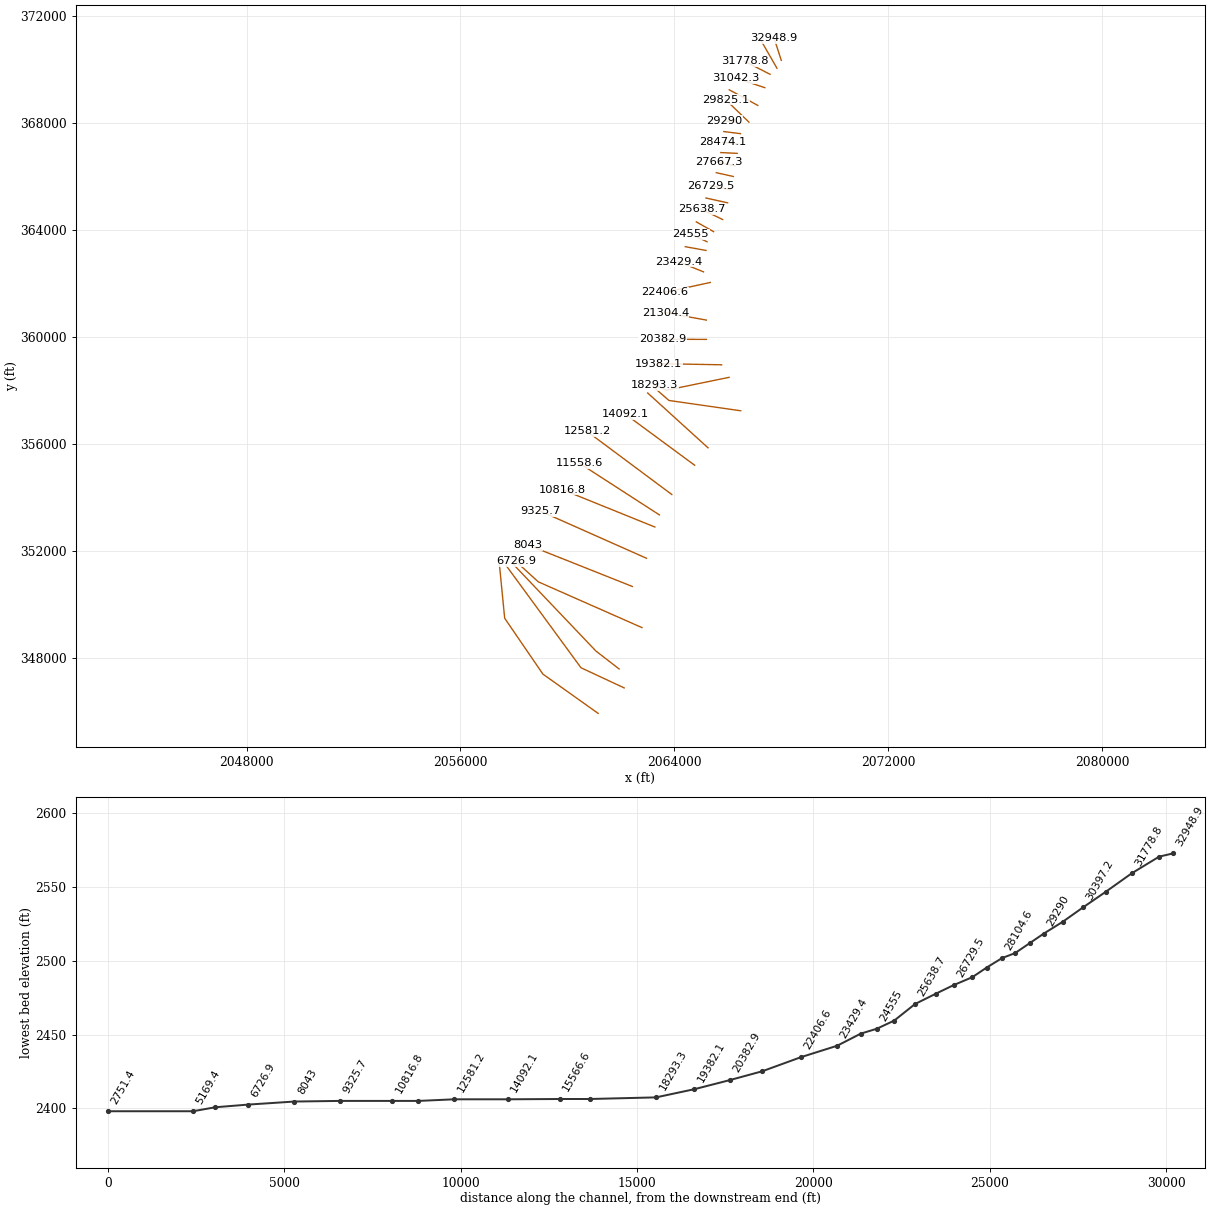
HEC-RAS study BigClearCk.prj: BigClearCk

--- BigClearCk.g01 (geometry) --- (continued)

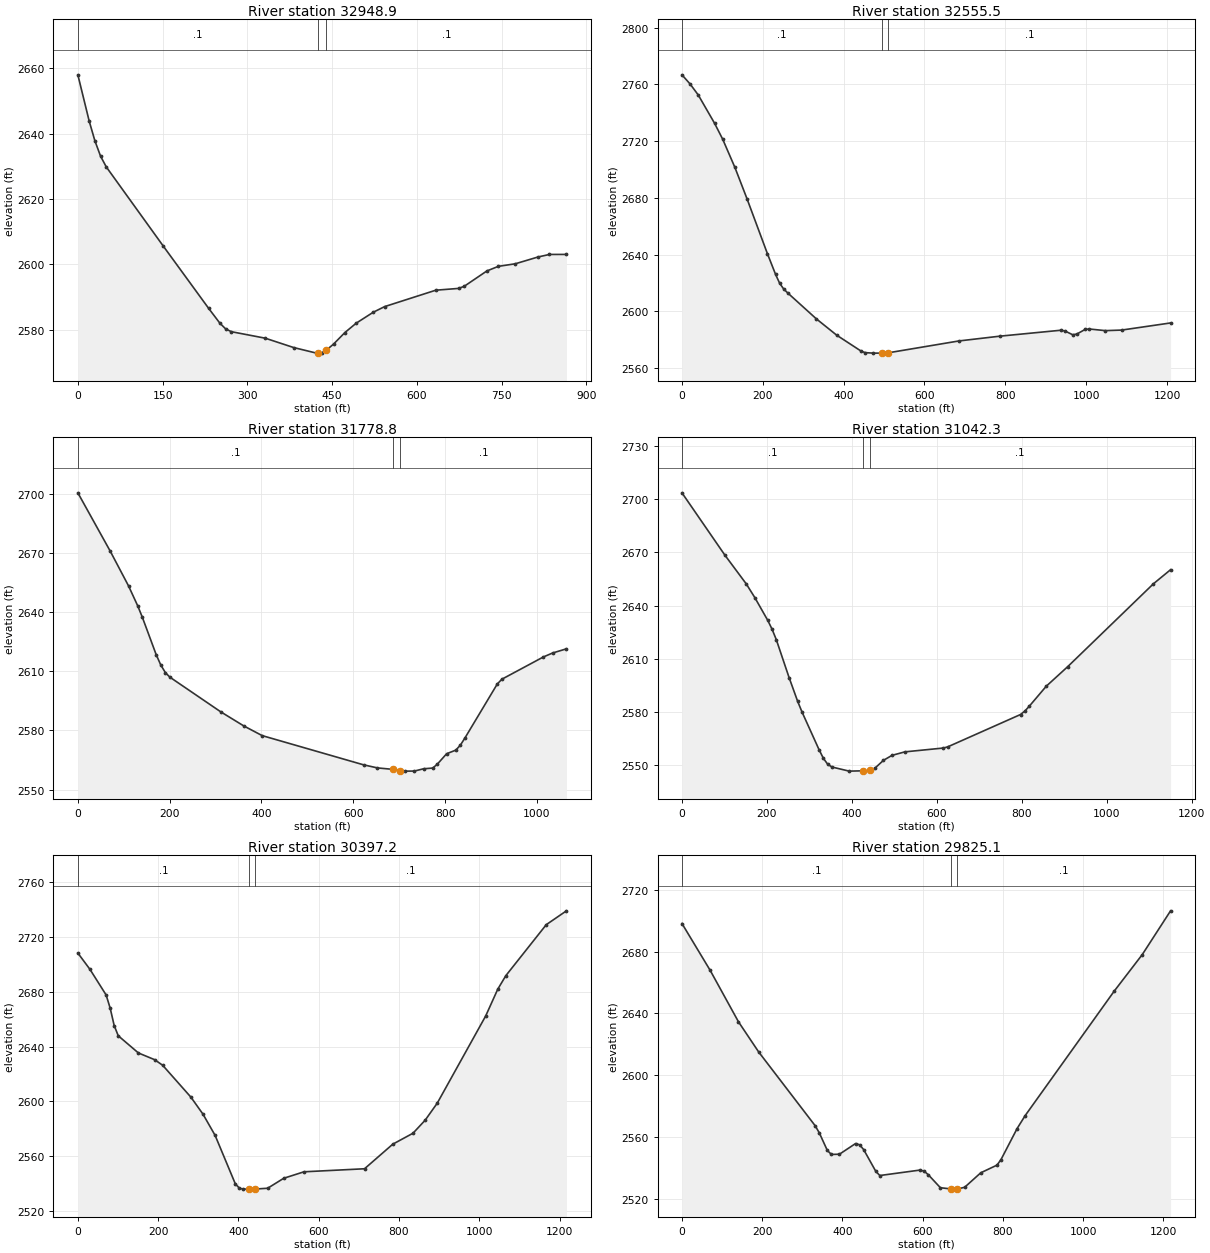
Type RM Length L Ch R = 1 ,32948.9 ,388.8,393.5,398.1
XS GIS Cut Line= 2
     2068001.692      370347.542     2067734.384      371170.028
#Sta/Elev= 30
       0 2657.95    20.1 2643.79    30.2 2637.77    40.2 2633.09    50.3 2629.81
   150.8  2605.7   231.3 2586.62   251.4 2582.04   261.5 2580.32   271.5 2579.45
   331.8 2577.45   382.1 2574.59   422.4 2572.89   424.9 2572.92   432.4 2573.02
   439.9  2573.8   452.5 2575.64   472.6 2579.17   492.8 2582.06   522.9 2585.39
     543 2587.11   633.5 2592.12   673.8 2592.67   683.8 2593.31     724 2598.01
   744.2 2599.41   774.3  2600.2   814.6 2602.28   834.7 2603.05   864.8 2603.06
#Mann= 3 , 0 , 0
       0      .1       0   424.9    .045       0   439.9      .1       0
Bank Sta=424.9,439.9
XS Rating Curve= 0 ,0
Exp/Cntr=0.3,0.1

Type RM Length L Ch R = 1 ,32555.5 ,763.7,776.7,789.6
XS GIS Cut Line= 2
     2067839.528      370051.842     2067237.373      371099.975
#Sta/Elev= 30
       0 2766.71    20.2 2760.23    40.3 2752.51    80.6 2732.62   100.7  2721.4
     131 2701.47   161.2  2679.2   211.5 2640.66   231.7 2626.07   241.8 2619.82
   251.8  2615.8   261.9    2613   332.4 2594.83   382.8 2583.32   443.2 2572.09
   453.3 2571.01   473.4 2570.67   494.6 2570.67   509.6 2570.86     685 2579.24
   785.7 2582.59   936.8 2586.78   946.9 2586.34     967 2583.58   977.1 2584.13
   997.2 2587.34  1007.3 2587.68  1047.6 2586.51  1087.9 2586.91  1208.8 2591.93
#Mann= 3 , 0 , 0
       0      .1       0   494.6    .045       0   509.6      .1       0
Bank Sta=494.6,509.6
XS Rating Curve= 0 ,0
Exp/Cntr=0.3,0.1

Type RM Length L Ch R = 1 ,31778.8 ,732.8,736.5,740.2
XS GIS Cut Line= 2
     2067582.181      369825.365     2066634.783      370310.038
#Sta/Elev= 30
       0 2700.59    70.3 2671.09   110.4 2653.36   130.5 2643.19   140.6 2637.37
   170.7 2618.42   180.7  2613.2   190.8  2609.3   200.8 2606.99   311.2 2589.47
   361.4 2582.31   401.6 2577.38   622.4 2562.56   652.6    2561   686.9 2560.25
   701.9 2559.61   712.8 2559.37   732.9  2559.4     753 2560.56     773 2560.93
   783.1 2562.94   803.2 2568.19   823.2 2570.03   833.3 2572.59   843.3 2576.27
   913.6  2603.6   923.6 2606.02    1014 2617.31  1034.1 2619.32  1064.2 2621.43
#Mann= 3 , 0 , 0
       0      .1       0   686.9    .045       0   701.9      .1       0
Bank Sta=686.9,701.9
XS Rating Curve= 0 ,0
Exp/Cntr=0.3,0.1

Type RM Length L Ch R = 1 ,31042.3 ,649.4,645.1,640.8
XS GIS Cut Line= 2
     2067386.845      369324.817     2066295.572      369688.152
#Sta/Elev= 30
       0 2703.45   100.9 2668.43   151.3 2652.22   171.5  2644.5   201.8 2631.74
   211.9  2626.8     222 2620.88   252.2 2599.46   272.4 2586.07   282.5 2580.16
   322.8 2558.85   332.9 2554.03     343 2550.71   353.1 2549.14   393.5 2546.82
     427    2547     442 2547.29     454 2548.43   474.2 2552.88   494.4 2555.69
   524.6 2557.66   615.4 2559.82   625.5 2560.47     797 2578.69   807.1 2580.61
   817.2 2583.24   857.6 2594.61     908  2605.6  1109.8 2652.25  1150.2 2660.18
#Mann= 3 , 0 , 0
       0      .1       0     427    .045       0     442      .1       0
Bank Sta=427,442
XS Rating Curve= 0 ,0
Exp/Cntr=0.3,0.1

Type RM Length L Ch R = 1 ,30397.2 ,578.1,572.1,566.1
XS GIS Cut Line= 2
     2067122.781      368662.002     2066055.476      369246.551
#Sta/Elev= 30
       0 2708.04    30.2 2696.15    70.4 2677.54    80.5 2667.96    90.5 2655.28
   100.6 2647.83   150.8 2635.32   191.1 2630.44   211.2 2626.38   281.6 2603.15
   311.8 2590.72   341.9 2575.31   392.2 2540.06   402.3 2536.91   412.3 2536.22
   425.4 2536.23   440.4 2536.26   472.7 2536.86   512.9 2544.14   563.2 2548.83
     714 2551.04   784.4 2568.94   834.7  2576.9   864.9 2586.35   895.1 2598.78
  1015.8 2662.27  1045.9 2681.78    1066  2691.6  1166.6 2728.68  1216.9 2738.76
#Mann= 3 , 0 , 0
       0      .1       0   425.4    .045       0   440.4      .1       0
Bank Sta=425.4,440.4
XS Rating Curve= 0 ,0
Exp/Cntr=0.3,0.1

Type RM Length L Ch R = 1 ,29825.1 ,520.5,535,549.5
XS GIS Cut Line= 2
     2066790.025      368038.985     2065912.354      368883.104
#Sta/Elev= 30
       0 2698.11    70.4  2667.8   140.9 2634.58   191.2 2615.12   332.1 2567.42
   342.2  2562.9   362.3  2551.5   372.4 2548.91   392.5 2549.07   432.7 2555.97
   442.8 2555.14   452.9 2552.03   483.1 2537.99   493.1  2535.3   593.8 2538.84
   603.8 2538.07   613.9 2535.81   644.1 2527.41   670.1 2526.66   684.3 2526.51
   685.1 2526.53   704.5  2527.7   744.7 2537.07     785    2542     795 2545.54
   835.3 2565.67   855.4 2574.04  1076.8 2654.27  1147.3 2678.08  1217.7  2706.3
#Mann= 3 , 0 , 0
       0      .1       0   670.1    .045       0   685.1      .1       0
Bank Sta=670.1,685.1
XS Rating Curve= 0 ,0
Exp/Cntr=0.3,0.1

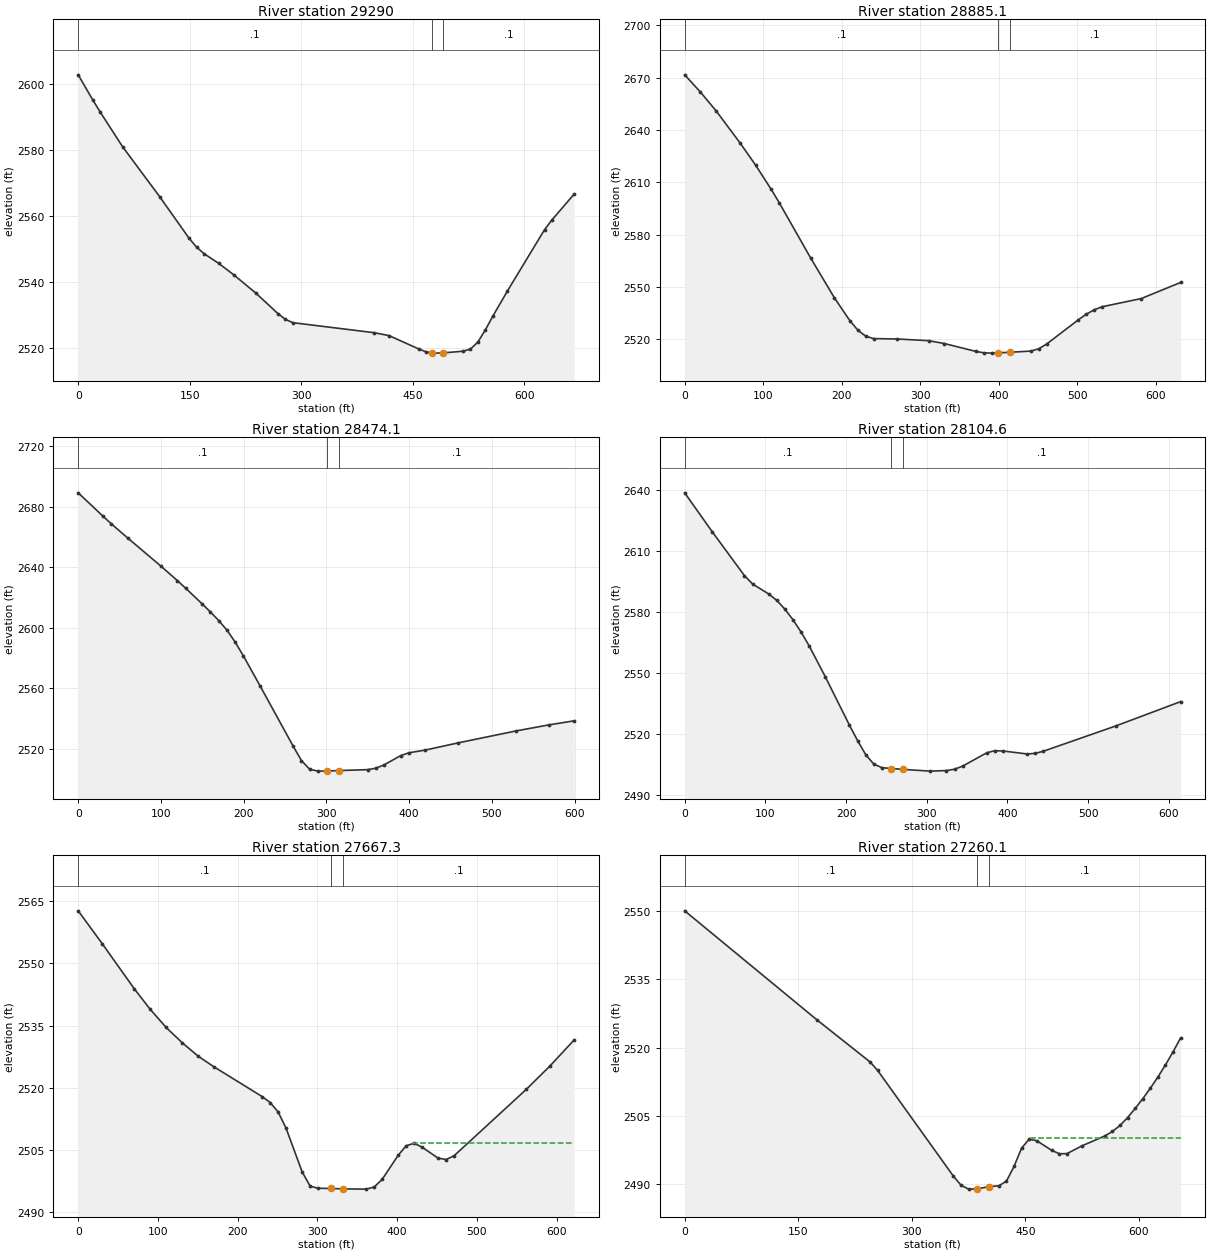
Type RM Length L Ch R = 1 ,29290   ,404.9,404.9,404.9
XS GIS Cut Line= 2
     2066541.823      368001.451     2065879.652      368084.425
#Sta/Elev= 30
       0  2602.9    19.9 2595.17    29.9 2591.51    59.8 2581.08   109.6 2565.97
   149.4  2553.3   159.4 2550.66   169.3 2548.69   189.2 2545.73   209.2  2542.3
     239 2536.74   268.9  2530.5   278.9 2528.77   288.8 2527.77   398.4 2524.73
   418.3 2523.85   458.2 2519.81   468.1 2518.94   476.1 2518.62   478.1 2518.54
   491.1 2518.61   517.9 2519.12   527.9 2519.78   537.9  2521.9   547.8 2525.54
   557.8 2529.68   577.7 2537.41   627.5 2555.94   637.5 2558.91   667.4 2566.75
#Mann= 3 , 0 , 0
       0      .1       0   476.1    .045       0   491.1      .1       0
Bank Sta=476.1,491.1
XS Rating Curve= 0 ,0
Exp/Cntr=0.3,0.1

Type RM Length L Ch R = 1 ,28885.1 ,411,411,411
XS GIS Cut Line= 2
      2066476.01       367606.57     2065849.592      367685.063
#Sta/Elev= 30
       0 2671.68      20 2661.82    40.1 2650.94    70.2 2632.77    90.2 2619.91
   110.2 2605.91   120.2  2598.4   160.3  2566.6   190.4 2543.83   210.4 2530.48
   220.5  2525.1   230.5 2521.66   240.5 2520.29   270.6 2520.06   310.6  2519.1
   330.7 2517.44   370.8 2512.93   380.8 2512.14   390.8 2511.95   398.8 2512.11
   413.8 2512.44   440.9 2513.14   450.9 2514.49     461 2517.24     501 2531.05
   511.1 2534.25   521.1 2536.79   531.1 2538.54   581.2 2543.27   631.3 2552.51
#Mann= 3 , 0 , 0
       0      .1       0   398.8    .045       0   413.8      .1       0
Bank Sta=398.8,413.8
XS Rating Curve= 0 ,0
Exp/Cntr=0.3,0.1

Type RM Length L Ch R = 1 ,28474.1 ,367.7,369.4,371.2
XS GIS Cut Line= 2
     2066410.196      367211.689     2065815.384      367286.222
#Sta/Elev= 30
       0  2689.2      30 2673.72      40 2668.72      60 2659.26    99.9  2640.8
   119.9 2631.16   129.9 2626.15   149.9 2615.76   159.9 2610.39   169.8  2604.8
   179.8 2598.45   189.8 2590.52   199.8 2581.27   219.8 2561.66   259.8 2521.78
   269.8 2512.28   279.8 2506.49   289.7 2505.26   300.4 2505.33   315.4 2505.63
   349.7 2506.24   359.7 2507.17   369.7 2509.38   389.6 2515.44   399.6 2517.36
   419.6 2519.18   459.6 2523.98   529.5 2531.85   569.5 2535.88   599.5  2538.5
#Mann= 3 , 0 , 0
       0      .1       0   300.4    .045       0   315.4      .1       0
Bank Sta=300.4,315.4
XS Rating Curve= 0 ,0
Exp/Cntr=0.3,0.1

Type RM Length L Ch R = 1 ,28104.6 ,441.1,437.3,433.4
XS GIS Cut Line= 3
     2066353.191      366869.656     2066349.113      366869.852
     2065739.319      366899.285
#Sta/Elev= 30
       0 2638.84    34.1  2619.7    74.1 2598.08    84.2 2593.96   104.2 2589.05
   114.2 2585.89   124.2 2581.58   134.2  2576.4   144.2 2570.38   154.2 2563.57
   174.2 2548.38   204.2 2524.49   214.3 2516.88   224.3 2510.03   234.3 2505.38
   244.3  2503.6     256 2503.18     271 2502.74   304.3 2501.89   324.4 2502.18
   334.4 2502.82   344.4 2504.34   374.4 2510.93   384.4 2511.94   394.4  2511.8
   424.4 2510.34   434.4 2510.63   444.4 2511.67   534.5 2524.16   614.6  2536.1
#Mann= 3 , 0 , 0
       0      .1       0     256    .045       0     271      .1       0
Bank Sta=256,271
XS Rating Curve= 0 ,0
Exp/Cntr=0.3,0.1

Type RM Length L Ch R = 1 ,27667.3 ,407.3,407.2,407.1
XS GIS Cut Line= 3
     2066274.955      366400.241     2066265.304      366402.384
      2065667.72      366535.064
#Sta/Elev= 30
       0 2562.73      30 2554.82    70.1 2543.94    90.2 2538.94   110.2 2534.54
   130.3 2530.86   150.4 2527.59   170.4 2524.99   230.7 2517.82   240.7 2516.38
   250.7 2514.12   260.8 2510.12   280.8 2499.64   290.9 2496.15   300.9 2495.65
   316.9  2495.6   331.9  2495.5   361.1 2495.44   371.2 2495.95   381.2 2497.79
   401.2 2503.59   411.3 2505.92   421.3 2506.53   431.4 2505.57   451.4 2502.93
   461.5  2502.6   471.5 2503.52   561.8 2519.53   591.9 2525.26     622 2531.52
#Mann= 3 , 0 , 0
       0      .1       0   316.9    .045       0   331.9      .1       0
#XS Ineff= 2 , 0
                          419.75         2506.55
Permanent Ineff=
       F       F
Bank Sta=316.9,331.9
XS Rating Curve= 0 ,0
Exp/Cntr=0.3,0.1

Type RM Length L Ch R = 1 ,27260.1 ,530.5,530.5,530.5
XS GIS Cut Line= 3
     2066209.102      366005.122     2066194.656      366008.329
     2065569.593      366147.111
#Sta/Elev= 30
       0 2550.02   174.9 2526.05   244.9 2516.83   254.9 2514.97     355 2491.74
     365 2489.77     375  2488.9   386.5 2488.95   401.5 2489.44     415 2489.63
     425 2490.64     435 2493.87     445 2497.89     455 2499.87     465 2499.53
     485  2497.4     495 2496.67     505  2496.7     525 2498.42     555 2500.58
     565 2501.56     575 2502.88     585 2504.61   595.1 2506.62   605.1 2508.76
   615.1 2511.06   625.1 2513.52   635.1 2516.18   645.1 2519.05   655.1 2522.12
#Mann= 3 , 0 , 0
       0      .1       0   386.5    .045       0   401.5      .1       0
#XS Ineff= 2 , 0
                          456.95          2500.1
Permanent Ineff=
       F       F
Bank Sta=386.5,401.5
XS Rating Curve= 0 ,0
Exp/Cntr=0.3,0.1

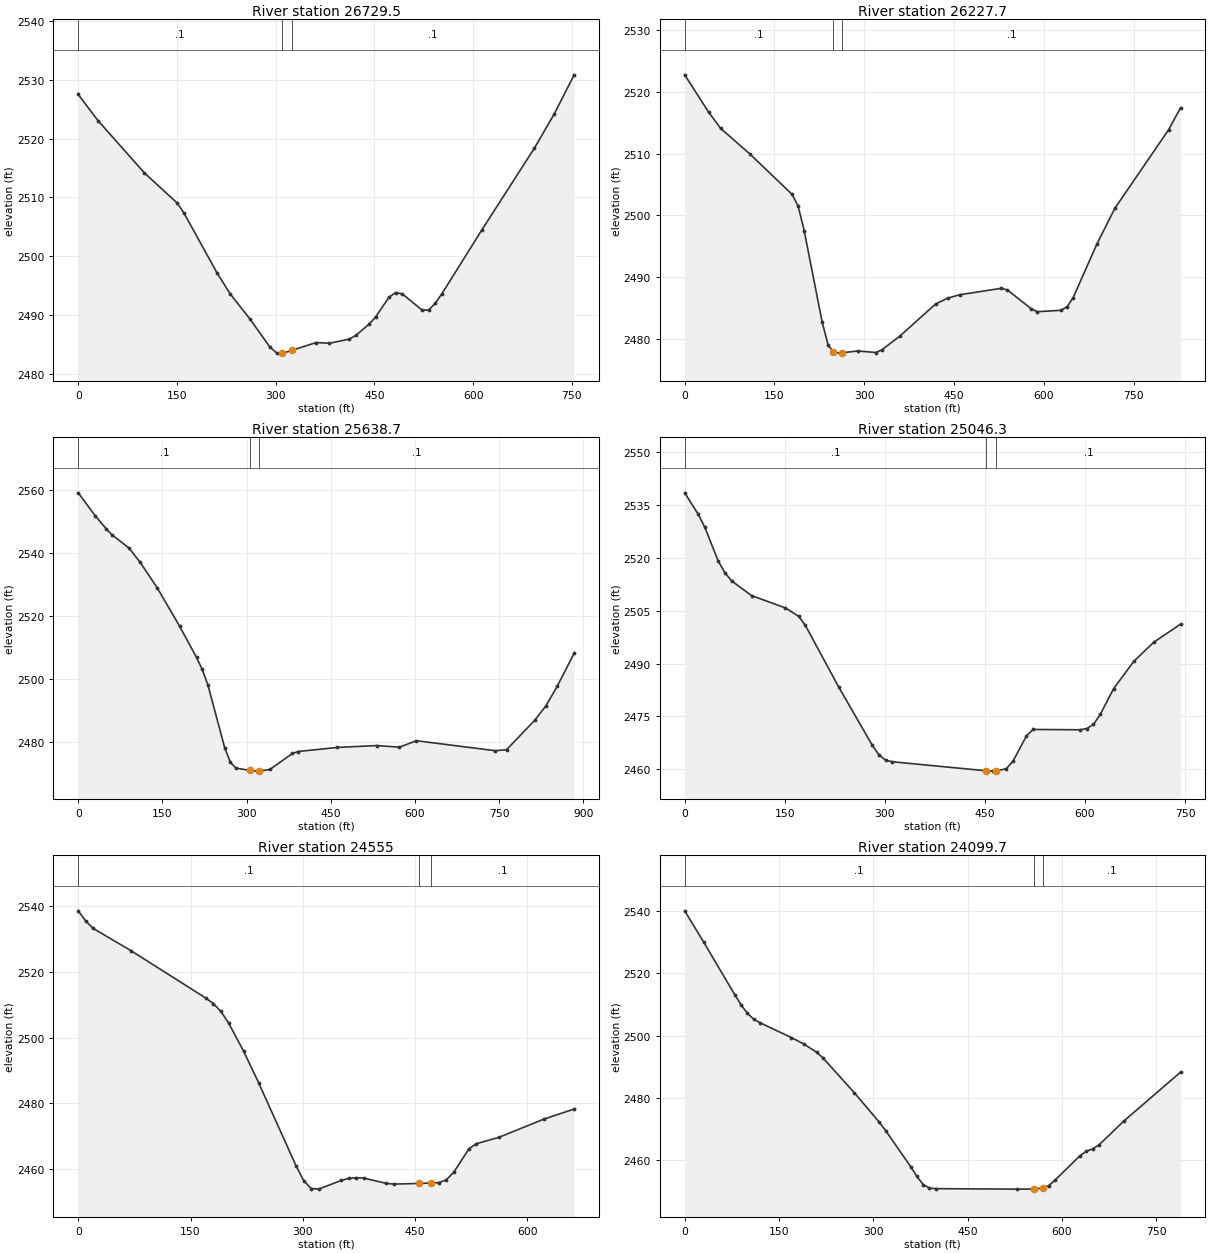
Type RM Length L Ch R = 1 ,26729.5 ,501.8,501.9,502
XS GIS Cut Line= 2
     2066109.941      365503.253     2065374.491      365666.543
#Sta/Elev= 30
       0 2527.52    30.1 2523.06   100.4 2514.19   150.7 2509.01   160.7 2507.34
   210.9 2497.16     231 2493.58   261.2 2489.28   291.3 2484.54   301.3 2483.56
   309.3 2483.53   311.4 2483.52   324.3 2483.99   361.6 2485.32   381.7  2485.2
   411.8 2485.91   421.9 2486.55     442 2488.46     452  2489.7   472.1 2493.02
   482.2 2493.82   492.2  2493.6   522.3 2490.86   532.4 2490.86   542.4 2491.99
   552.5 2493.62   612.7 2504.39   693.1  2518.4   723.2 2524.21   753.4 2530.85
#Mann= 3 , 0 , 0
       0      .1       0   309.3    .045       0   324.3      .1       0
#XS Ineff= 2 , 0
                          482.55         2493.78
Permanent Ineff=
       F       F
Bank Sta=309.3,324.3
XS Rating Curve= 0 ,0
Exp/Cntr=0.3,0.1

Type RM Length L Ch R = 1 ,26227.7 ,594.1,588.9,583.8
XS GIS Cut Line= 2
     2065993.603      365020.271     2065185.002      365199.803
#Sta/Elev= 30
       0 2522.75    39.9 2516.73    59.9  2514.1   109.8 2509.86   179.6 2503.39
   189.6 2501.47   199.6 2497.54   229.5 2482.79   239.5 2479.06   247.8 2477.96
   259.5 2477.72   262.8 2477.78   289.4 2478.07   319.3 2477.82   329.3 2478.25
   359.3 2480.47   419.1 2485.67   439.1 2486.61     459 2487.16   528.9 2488.21
   538.9 2487.95   578.8  2484.9   588.8 2484.42   628.7 2484.65   638.7 2485.23
   648.7 2486.67   688.6  2495.4   718.5 2501.16   808.3 2513.87   828.3 2517.45
#Mann= 3 , 0 , 0
       0      .1       0   247.8    .045       0   262.8      .1       0
#XS Ineff= 2 , 0
                          532.33         2487.97
Permanent Ineff=
       F       F
Bank Sta=247.8,262.8
XS Rating Curve= 0 ,0
Exp/Cntr=0.3,0.1

Type RM Length L Ch R = 1 ,25638.7 ,592.9,592.4,591.2
XS GIS Cut Line= 2
     2065810.088      364395.477     2065014.039      364778.693
#Sta/Elev= 30
       0 2559.14    30.1 2551.91    50.2 2547.64    60.2 2545.78    90.4 2541.63
   110.4 2537.05   140.6 2528.99   180.7 2516.75   210.8 2506.83   220.9 2503.06
   230.9 2498.18     261 2478.13   271.1 2473.52   281.1 2471.68   306.7 2470.94
   321.3 2470.73   321.7 2470.73   341.4 2471.25   381.5 2476.33   391.6 2476.96
   461.8 2478.26   532.1 2478.86   572.3 2478.34   602.4 2480.39   742.9 2477.22
     763 2477.53   813.2 2486.86   833.3  2491.5   853.4 2497.71   883.5 2508.17
#Mann= 3 , 0 , 0
       0      .1       0   306.7    .045       0   321.7      .1       0
#XS Ineff= 2 , 0
                          604.07          2480.3
Permanent Ineff=
       F       F
Bank Sta=306.7,321.7
XS Rating Curve= 0 ,0
Exp/Cntr=0.3,0.1

Type RM Length L Ch R = 1 ,25046.3 ,490.5,491.3,492.8
XS GIS Cut Line= 2
     2065470.249      363942.359     2064822.634      364307.234
#Sta/Elev= 30
       0 2538.54    20.1 2532.53    30.1 2528.78    50.2 2519.19    60.3 2515.84
    70.3 2513.53   100.4 2509.32   150.7 2505.86   170.8 2503.47   180.8  2500.9
     231 2483.31   281.3 2466.76   291.3 2464.04   301.4 2462.54   311.4 2462.12
   451.5 2459.56   462.1 2459.46   466.5 2459.47   482.2 2460.18   492.2 2462.34
   512.3 2469.48   522.3  2471.3   592.6 2471.21   602.7 2471.57   612.7 2472.73
   622.8 2475.56   642.9 2482.89     673 2490.63   703.2 2496.12   743.3 2501.22
#Mann= 3 , 0 , 0
       0      .1       0   451.5    .045       0   466.5      .1       0
Bank Sta=451.5,466.5
XS Rating Curve= 0 ,0
Exp/Cntr=0.3,0.1

Type RM Length L Ch R = 1 ,24555   ,449.5,455.3,461
XS GIS Cut Line= 2
     2065222.057      363566.216     2064620.834       363844.47
#Sta/Elev= 30
       0 2538.52      10 2535.43    20.1 2533.17    70.3 2526.44   170.6 2511.99
   180.7  2510.3   190.7 2507.94   200.8 2504.46   220.8 2495.94   240.9 2486.33
   291.1 2460.99   301.1 2456.57   311.2 2454.14   321.2 2453.95   351.3 2456.59
   361.4 2457.22   371.4 2457.42   381.4  2457.3   411.6  2455.7   421.6 2455.48
   455.9 2455.68   470.9  2455.8   481.8 2455.94   491.8 2456.79   501.9 2459.16
     522  2466.2     532 2467.76   562.1  2469.7   622.3 2475.25   662.5 2478.29
#Mann= 3 , 0 , 0
       0      .1       0   455.9    .045       0   470.9      .1       0
Bank Sta=455.9,470.9
XS Rating Curve= 0 ,0
Exp/Cntr=0.3,0.1

Type RM Length L Ch R = 1 ,24099.7 ,675,670.4,665.8
XS GIS Cut Line= 2
     2065184.803      363240.248     2064408.517      363380.724
#Sta/Elev= 30
       0 2540.07      30 2530.09    79.9 2513.05    89.9 2509.82    99.9  2507.1
   109.8 2505.27   119.8  2504.1   169.8 2499.34   189.7 2497.24   209.7 2494.65
   219.7 2492.86   269.6 2481.67   309.6 2472.15   319.6 2469.47   359.5 2457.86
   369.5 2454.69   379.5 2452.08   389.4 2450.98   399.4 2450.78   529.3 2450.63
   554.9 2450.66   569.9 2450.94   579.2 2451.77   589.2 2453.53   629.1 2461.42
   639.1 2462.78   649.1  2463.6   659.1 2464.86     699 2472.58   788.9 2488.25
#Mann= 3 , 0 , 0
       0      .1       0   554.9    .045       0   569.9      .1       0
Bank Sta=554.9,569.9
XS Rating Curve= 0 ,0
Exp/Cntr=0.3,0.1

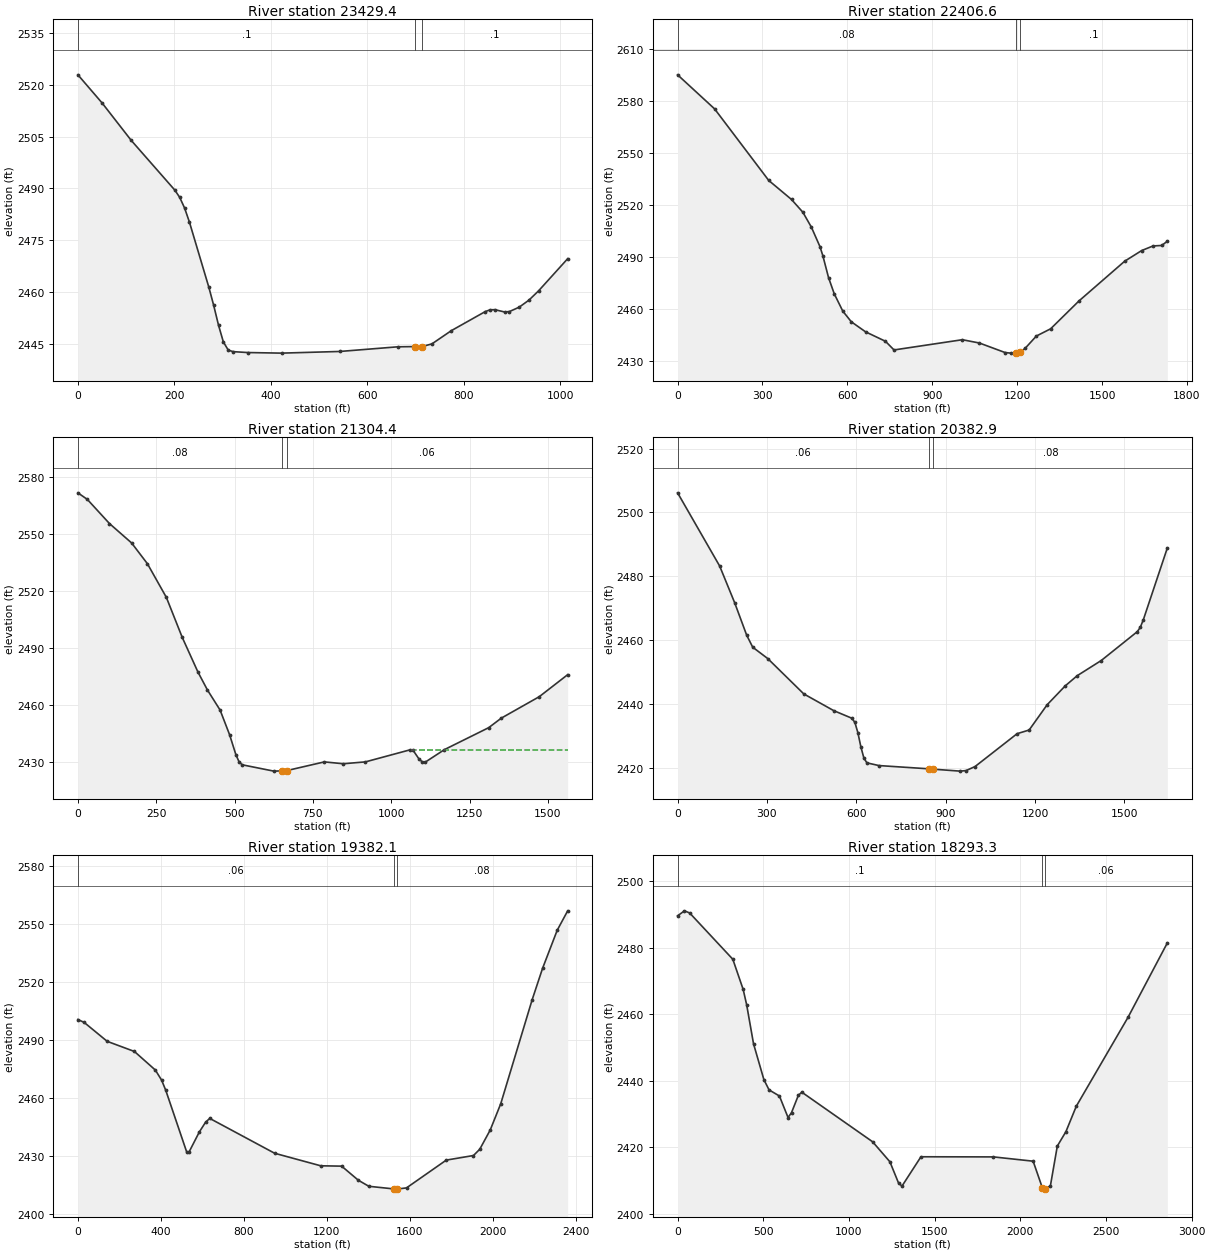
Type RM Length L Ch R = 1 ,23429.4 ,1009.2,1022.7,1036.2
XS GIS Cut Line= 2
     2065093.294      362439.547     2064151.378      362819.078
#Sta/Elev= 30
       0 2522.85    50.3 2514.69   110.6 2503.89   201.1  2489.5   211.1 2487.42
   221.2 2484.34   231.2 2480.29   271.5 2461.44   281.5 2456.22   291.6 2450.44
   301.6 2445.63   311.7 2443.28   321.7 2442.83   351.9 2442.57   422.3  2442.4
   542.9 2442.88   663.6 2444.23   698.1 2444.29   713.1 2444.28     734 2445.07
   774.2 2448.89   844.6 2454.41   854.6 2454.92   864.7 2454.96   884.8 2454.29
   894.8 2454.42     915 2455.69   935.1 2457.71   955.2 2460.41  1015.5  2469.7
#Mann= 3 , 0 , 0
       0      .1       0   698.1    .045       0   713.1      .1       0
Bank Sta=698.1,713.1
XS Rating Curve= 0 ,0
Exp/Cntr=0.3,0.1

Type RM Length L Ch R = 1 ,22406.6 ,1111.1,1102.1,1092.6
XS GIS Cut Line= 2
     2065345.141      362042.814     2063654.075      361675.121
#Sta/Elev= 30
       0 2595.12   130.8 2575.48     322 2534.24   402.5 2523.26   442.7 2515.89
   472.9 2507.25   503.1 2496.06   513.1 2490.93   533.3 2478.26   553.4 2468.94
   583.6 2458.93   613.8 2452.75   664.1 2446.97   734.5 2441.51   764.7 2436.51
  1006.2 2442.41  1066.5 2440.51  1157.1 2435.02  1177.2 2434.68    1194 2434.69
    1209 2435.09  1227.5 2437.35  1267.8 2444.54  1318.1  2448.7  1418.7 2464.83
  1579.7 2487.66    1640 2493.83  1680.3 2496.48  1710.5 2496.74  1730.6 2499.21
#Mann= 3 , 0 , 0
       0     .08       0    1194    .045       0    1209      .1       0
Bank Sta=1194,1209
XS Rating Curve= 0 ,0
Exp/Cntr=0.3,0.1

Type RM Length L Ch R = 1 ,21304.4 ,915.3,921.5,927.6
XS GIS Cut Line= 2
     2065198.395      360636.393     2063660.798      360915.988
#Sta/Elev= 30
       0 2571.57    30.2 2568.09   100.8 2555.38   171.4 2545.18   221.8 2534.25
   282.3 2516.52   332.7 2495.56   383.1 2477.21   413.4 2467.77   453.7 2457.22
     484 2444.25   504.1 2433.74   514.2 2429.99   524.3 2428.41   625.1 2425.08
   650.6 2425.21   665.6 2425.33   786.4 2429.94   846.9 2428.96   917.5 2429.95
  1058.7 2436.24  1068.8 2436.21  1088.9 2431.34    1099 2429.96  1109.1 2429.89
  1169.6 2436.41  1310.7 2447.95  1351.1 2452.98  1472.1 2464.26  1562.8 2475.85
#Mann= 3 , 0 , 0
       0     .08       0   650.6    .045       0   665.6     .06       0
#XS Ineff= 2 , 0
                          1064.3         2436.45
Permanent Ineff=
       F       F
Bank Sta=650.6,665.6
XS Rating Curve= 0 ,0
Exp/Cntr=0.3,0.1

Type RM Length L Ch R = 1 ,20382.9 ,1000.6,1000.8,1001
XS GIS Cut Line= 2
     2065201.604      359914.904     2063557.545      359918.095
#Sta/Elev= 30
       0 2506.14   141.2 2483.24   191.6 2471.75     232 2461.58   252.2 2457.84
   302.6 2454.29   423.6 2443.23   524.5 2437.98     585 2435.62   595.1 2434.32
   605.2  2431.1   615.3 2426.64   625.4 2423.16   635.4 2421.66   675.8 2420.81
   843.4 2419.79   858.4 2419.68   948.1 2419.07   968.3 2419.24   998.5  2420.5
  1139.8 2430.79  1180.1 2431.93  1240.6 2439.84  1301.1 2445.73  1341.5 2448.93
  1422.2 2453.68  1543.2 2462.71  1553.3 2464.07  1563.4 2466.42  1644.1 2488.92
#Mann= 3 , 0 , 0
       0     .06       0   843.4    .045       0   858.4     .08       0
Bank Sta=843.4,858.4
XS Rating Curve= 0 ,0
Exp/Cntr=0.3,0.1

Type RM Length L Ch R = 1 ,19382.1 ,1083.6,1088.2,1092.9
XS GIS Cut Line= 2
     2065768.663      358965.409      2063408.12      359007.538
#Sta/Elev= 30
       0 2500.66    30.3 2499.15   141.2 2489.37   272.4 2484.13   373.3 2474.52
   403.6 2469.28   423.8 2463.96   524.6 2432.08   534.7 2431.92   585.2 2442.48
   615.4 2447.54   635.6 2449.51   948.4 2431.48  1170.4    2425  1271.3 2424.82
    1352 2417.51  1402.4  2414.4  1522.4 2413.04  1533.6 2412.93  1537.4 2412.94
    1584 2413.57  1775.7 2427.94  1906.9 2430.32  1937.2 2433.58  1987.6 2443.53
  2038.1 2457.06  2189.4  2510.8  2239.8 2527.12  2310.5 2546.85  2360.9 2556.88
#Mann= 3 , 0 , 0
       0     .06       0  1522.4    .045       0  1537.4     .08       0
Bank Sta=1522.4,1537.4
XS Rating Curve= 0 ,0
Exp/Cntr=0.3,0.1

Type RM Length L Ch R = 1 ,18293.3 ,1878.3,1876.2,1877
XS GIS Cut Line= 4
     2066049.016      358495.981      2063710.61      358015.849
     2063300.515       358183.46     2063274.623      358194.042
#Sta/Elev= 30
       0 2489.64    40.3 2491.14    70.5 2490.49   322.3 2476.56   382.8 2467.46
   402.9  2462.9   443.2 2451.11   503.6 2440.33   533.8 2437.24   594.3  2435.4
   644.6 2428.92   664.8 2430.39   705.1 2435.64   725.2 2436.54  1138.2 2421.62
  1238.9 2415.61  1289.3 2409.22  1309.4 2408.28  1420.2 2417.11  1843.3 2417.07
  2074.9 2415.78  2128.6 2407.77  2143.6 2407.38  2145.4 2407.37  2175.7 2408.39
    2216 2420.34  2266.3 2424.68  2326.8 2432.33  2628.8  2459.1  2858.2  2481.5
#Mann= 3 , 0 , 0
       0      .1       0  2128.6    .045       0  2143.6     .06       0
Bank Sta=2128.6,2143.6
XS Rating Curve= 0 ,0
Exp/Cntr=0.3,0.1

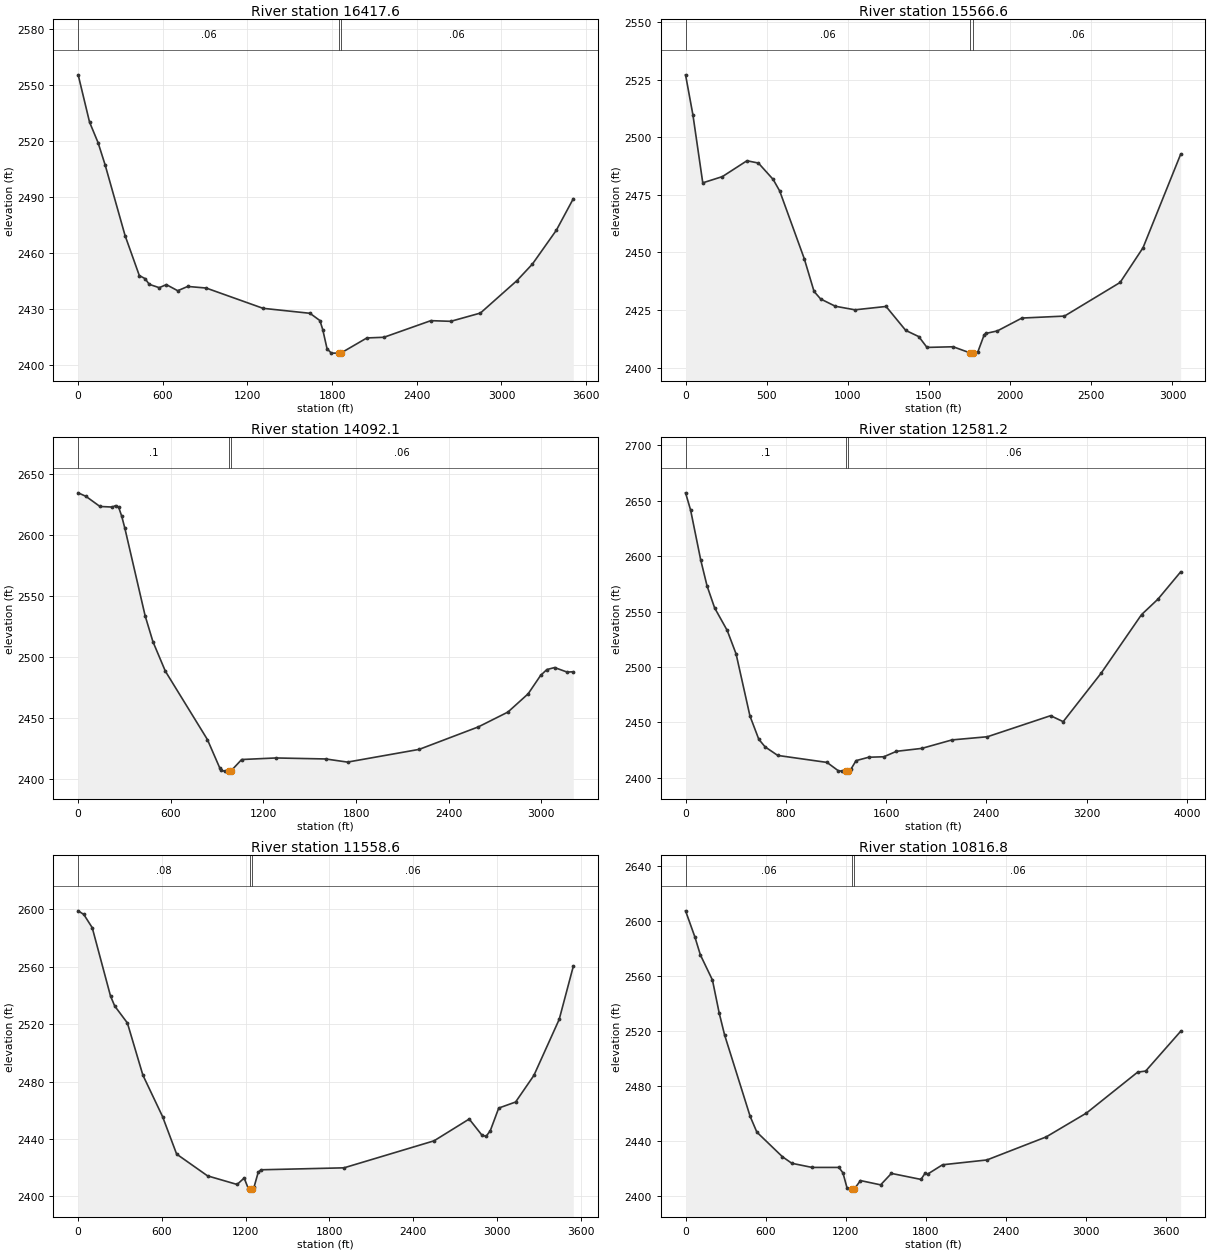
Type RM Length L Ch R = 1 ,16417.6 ,871.8,851,827.3
XS GIS Cut Line= 3
     2066483.802      357245.403     2063799.909      357631.443
      2063197.17      358154.046
#Sta/Elev= 30
       0 2555.65    80.6 2530.28   141.1 2519.23   191.5  2507.2   332.6 2469.33
   433.4 2447.91   473.8 2446.27     504 2443.19   574.6  2441.4     625 2443.05
   705.6 2439.76   776.2 2442.06   907.2 2441.21  1310.4 2430.32    1643 2427.65
  1713.6 2423.74  1733.8 2418.81    1764 2408.63  1794.2 2406.27  1846.5 2406.27
  1861.5 2406.28  2046.2 2414.42  2167.2 2414.78  2499.8  2423.7    2641 2423.34
  2851.1 2427.78  3110.4 2445.23  3220.1 2454.12  3389.6 2472.28  3509.3 2489.14
#Mann= 3 , 0 , 0
       0     .06       0  1846.5    .045       0  1861.5     .06       0
Bank Sta=1846.5,1861.5
XS Rating Curve= 0 ,0
Exp/Cntr=0.3,0.1

Type RM Length L Ch R = 1 ,15566.6 ,1471.2,1474.4,1477.7
XS GIS Cut Line= 3
     2065262.251      355859.669     2065243.396      355876.796
     2063004.111      357910.699
#Sta/Elev= 30
       0 2527.03    45.6 2509.57   106.1 2480.16   227.1 2482.87   378.4 2489.75
     449 2488.74   539.7 2481.65   580.1 2476.63   731.3 2447.28   791.8 2433.04
   832.2 2429.78   922.9 2426.61  1043.9 2425.06  1235.5 2426.52  1356.5 2416.14
  1437.2 2413.43  1487.6 2408.75  1648.9 2409.03    1755 2406.32  1759.9 2406.27
    1770 2406.27  1800.2 2406.65  1840.5 2414.31  1850.6 2414.82  1921.2 2415.91
  2072.4 2421.49  2334.6 2422.34  2677.5 2436.93  2818.6 2451.98  3050.6 2492.58
#Mann= 3 , 0 , 0
       0     .06       0    1755    .045       0    1770     .06       0
Bank Sta=1755,1770
XS Rating Curve= 0 ,0
Exp/Cntr=0.3,0.1

Type RM Length L Ch R = 1 ,14092.1 ,1507.5,1510.7,1510.3
XS GIS Cut Line= 2
     2064758.439      355211.285     2062176.052      357113.628
#Sta/Elev= 30
       0 2634.41    50.4 2631.52   141.2 2623.21   221.9 2622.74   242.1 2623.94
   262.2 2622.61   282.4 2615.11   302.6 2605.25   433.7 2533.59   484.1 2512.35
   564.8 2488.07   837.2 2431.98   917.8 2408.51   927.9 2406.65   948.1 2406.07
   974.8 2406.07   989.8 2406.22  1059.1 2415.59    1281 2416.87  1603.7 2416.05
  1744.9 2413.48  2208.9 2423.91  2592.2 2442.36  2783.8 2454.52  2914.9 2469.49
  2995.6 2484.57    3036 2489.39  3086.4 2491.06  3167.1 2487.34  3207.4 2487.59
#Mann= 3 , 0 , 0
       0      .1       0   974.8    .045       0   989.8     .06       0
Bank Sta=974.8,989.8
XS Rating Curve= 0 ,0
Exp/Cntr=0.3,0.1

Type RM Length L Ch R = 1 ,12581.2 ,1025.6,1022.6,1023.1
XS GIS Cut Line= 2
     2063906.817      354115.284     2060737.579       356472.89
#Sta/Elev= 30
       0 2657.19    40.3 2641.65   120.9 2596.68   171.3  2573.3   231.8 2553.41
   332.5 2532.99   403.1 2511.87   513.9 2455.79   584.4 2434.81   634.8 2427.95
   735.6 2420.23  1128.6 2413.93  1219.3 2406.36  1249.5 2406.07  1277.7 2406.07
  1292.7 2406.07    1320 2407.91  1360.3 2415.54  1461.1  2418.6    1582 2419.03
  1682.8 2423.95  1884.3 2426.58  2126.1 2434.24  2408.3  2437.1  2912.1 2456.09
  3012.9 2450.72  3315.2  2494.4  3637.6 2547.26  3768.6 2561.23    3950 2585.86
#Mann= 3 , 0 , 0
       0      .1       0  1277.7    .045       0  1292.7     .06       0
Bank Sta=1277.7,1292.7
XS Rating Curve= 0 ,0
Exp/Cntr=0.3,0.1

Type RM Length L Ch R = 1 ,11558.6 ,737.1,741.9,746.7
XS GIS Cut Line= 2
     2063441.386      353353.629     2060462.437      355277.083
#Sta/Elev= 30
       0 2599.05    40.3 2596.51   100.7 2587.29   231.7 2539.61   261.9 2532.64
   352.6 2520.82   463.4 2484.48   604.4 2455.56   705.2  2429.4   926.8 2414.21
  1138.3 2408.22  1188.7  2412.7  1218.9 2405.29  1232.9 2404.98  1239.1 2404.97
  1247.9 2405.15  1259.2 2406.24  1289.4  2416.7  1309.6 2418.46  1903.9 2419.82
  2548.7 2438.65  2800.5 2453.85  2891.2 2442.69  2921.4 2441.75  2951.6 2445.71
    3012  2461.5  3132.9 2465.72  3263.9 2484.28  3445.2 2523.37    3546 2560.32
#Mann= 3 , 0 , 0
       0     .08       0  1232.9    .045       0  1247.9     .06       0
Bank Sta=1232.9,1247.9
XS Rating Curve= 0 ,0
Exp/Cntr=0.3,0.1

Type RM Length L Ch R = 1 ,10816.8 ,1491.8,1491.1,1490.5
XS GIS Cut Line= 2
     2063270.446      352900.868     2059827.496      354292.924
#Sta/Elev= 30
       0 2607.63    70.6 2588.45     111 2575.59   201.8 2557.22   252.3 2533.23
   292.7  2517.3   484.4    2458   534.9 2446.47   726.6 2428.56   797.2 2423.79
   948.6 2420.78  1150.4 2420.77  1180.7 2416.79    1211 2405.96  1231.2 2404.97
  1251.2 2404.97  1266.2 2405.11  1311.9 2411.21  1463.3 2408.08    1544 2416.42
    1766 2412.04  1796.3  2416.5  1816.5 2415.95  1927.5  2422.7  2260.5 2426.21
  2704.6 2442.97  3007.3 2460.38  3390.8 2490.14  3451.3 2490.96  3713.7  2519.9
#Mann= 3 , 0 , 0
       0     .06       0  1251.2    .045       0  1266.2     .06       0
Bank Sta=1251.2,1266.2
XS Rating Curve= 0 ,0
Exp/Cntr=0.3,0.1

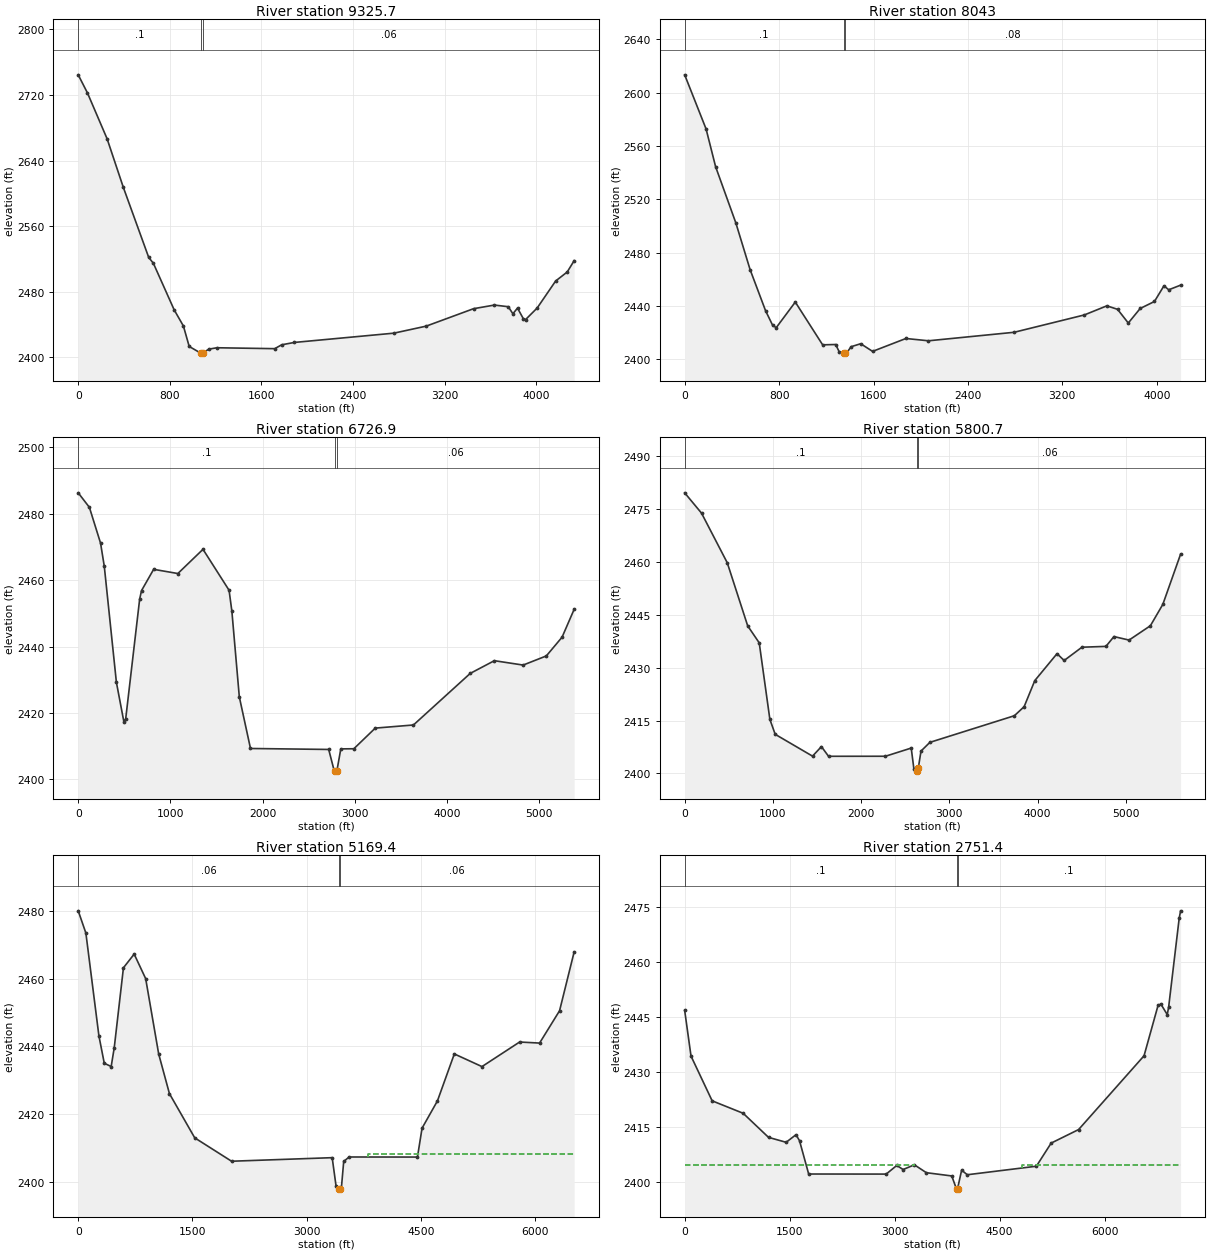
Type RM Length L Ch R = 1 ,9325.7  ,1281.2,1282.7,1284.1
XS GIS Cut Line= 2
     2062959.875      351731.992     2059002.071      353488.664
#Sta/Elev= 30
       0 2744.55    80.8 2722.41   252.3 2666.47   393.6 2607.36   615.7 2521.69
   656.1 2514.66   837.8 2457.78   918.5 2438.06     969 2413.11  1069.9 2404.97
  1071.1 2404.97  1086.1 2405.04  1140.6 2409.84  1211.2 2411.52  1715.9 2410.41
  1776.5 2415.14  1887.5 2418.02  2755.5 2429.32  3038.2  2437.9    3452  2459.2
  3633.7 2463.62  3754.8  2461.6  3795.2 2452.99  3835.6 2459.92    3886 2447.09
  3906.2 2445.96  4007.2 2460.02  4168.6    2493  4269.6 2503.98  4330.1 2517.81
#Mann= 3 , 0 , 0
       0      .1       0  1071.1    .045       0  1086.1     .06       0
Bank Sta=1071.1,1086.1
XS Rating Curve= 0 ,0
Exp/Cntr=0.3,0.1

Type RM Length L Ch R = 1 ,8043    ,1317.2,1315.9,1314.5
XS GIS Cut Line= 2
     2062430.904      350677.219     2058525.865      352229.363
#Sta/Elev= 30
       0 2613.39   181.4 2572.75     262 2544.47   433.3 2502.32   554.2 2467.25
   685.2 2436.41   745.7 2425.37     776 2423.69   937.2 2442.88    1169 2410.77
  1279.8 2411.02    1310 2405.38  1346.2 2404.69  1361.2 2404.58  1370.5 2404.55
  1410.8 2409.38  1491.4 2411.61  1592.2 2405.86  1874.4 2415.53  2065.8 2413.81
  2791.4 2420.19    3386 2433.19  3577.4 2440.04  3668.1 2437.41  3758.8 2427.14
  3859.6 2438.05  3980.5  2443.3  4061.1 2455.09  4101.4 2452.08  4202.2 2455.57
#Mann= 3 , 0 , 0
       0      .1       0  1346.2    .045       0  1361.2     .08       0
Bank Sta=1346.2,1361.2
XS Rating Curve= 0 ,0
Exp/Cntr=0.3,0.1

Type RM Length L Ch R = 1 ,6726.9  ,935.3,926.3,917.3
XS GIS Cut Line= 3
     2062790.557      349139.312     2058911.478      350850.788
     2058070.823      351615.586
#Sta/Elev= 30
       0 2486.31   121.1 2481.94   242.3 2471.15   282.7 2464.17   413.9 2429.23
   494.6  2417.4   514.8 2418.22   666.3 2454.32   686.4 2456.86   817.7 2463.26
  1080.2    2462  1352.7 2469.29  1635.4 2456.96  1665.7 2450.68  1746.4 2424.85
  1867.6 2409.29  2715.5    2409  2776.1 2402.47    2789 2402.47    2804 2402.52
  2846.8 2409.17  2988.1 2409.21  3220.3 2415.43  3634.2 2416.37  4249.9 2431.91
  4511.4 2435.74  4823.2 2434.42  5074.6 2437.17  5245.6 2442.83  5376.4 2451.22
#Mann= 3 , 0 , 0
       0      .1       0    2789    .045       0    2804     .06       0
Bank Sta=2789,2804
XS Rating Curve= 0 ,0
Exp/Cntr=0.3,0.1

Type RM Length L Ch R = 1 ,5800.7  ,634.2,631.3,628.4
XS GIS Cut Line= 3
     2061933.386      347594.287     2061066.023      348265.234
     2057943.835      351541.509
#Sta/Elev= 30
       0 2479.61   191.2 2473.84   482.9 2459.76   714.3 2441.88   845.1 2437.06
   965.8 2415.35  1026.2 2411.11  1449.4 2404.92  1550.2 2407.63  1630.8 2404.88
  2275.9 2404.89  2568.2 2407.21  2598.4 2401.32  2628.7 2400.67  2633.5 2400.71
  2648.5 2401.53  2679.1 2406.36  2779.9 2408.83  3737.4 2416.38  3848.3 2418.95
  3969.2 2426.35  4221.2 2433.99  4301.9 2432.05  4503.5 2435.82  4775.6 2436.05
  4866.3 2438.84  5037.7 2437.84  5279.6 2441.91  5420.7 2447.97  5622.3 2462.23
#Mann= 3 , 0 , 0
       0      .1       0  2633.5    .045       0  2648.5     .06       0
Bank Sta=2633.5,2648.5
XS Rating Curve= 0 ,0
Exp/Cntr=0.3,0.1

Type RM Length L Ch R = 1 ,5169.4  ,2415,2418,2418.2
XS GIS Cut Line= 3
     2062123.869      346885.269     2060508.307      347638.814
     2057711.023       351456.85
#Sta/Elev= 30
       0 2479.98   100.7 2473.43   271.9 2443.14   342.4 2435.06   433.1  2434.1
   473.4 2439.64   594.2  2463.2   735.2 2467.23   886.3    2460  1057.5 2437.77
  1198.5 2426.11  1530.9 2413.08  2014.8 2406.19  3336.8 2407.24  3387.3 2398.93
  3407.4 2397.97  3425.2 2397.97  3440.2 2397.98  3457.9 2398.39  3488.2 2406.12
  3558.8 2407.44    4457 2407.42  4517.6 2415.94  4719.4 2423.96  4941.4 2437.81
  5304.7 2434.08  5799.2 2441.32  6061.6 2441.01    6324 2450.53  6515.8 2467.88
#Mann= 3 , 0 , 0
       0     .06       0  3425.2    .045       0  3440.2     .06       0
#XS Ineff= 2 , 0
                         3810.14         2408.27
Permanent Ineff=
       F       F
Bank Sta=3425.2,3440.2
XS Rating Curve= 0 ,0
Exp/Cntr=0.3,0.1

Type RM Length L Ch R = 1 ,2751.4  ,2715.7,2751.4,2774.1
XS GIS Cut Line= 4
     2061150.291      345932.856      2059082.96      347402.154
     2057654.675       349488.57     2057457.046       351499.18
#Sta/Elev= 30
       0 2446.79    90.6 2434.33   392.5  2422.1   835.4  2418.7  1197.7 2412.12
  1449.3 2410.77  1590.2 2412.84  1640.5 2411.21  1771.4  2402.1  2878.8 2402.08
  3029.9 2404.44  3120.5 2403.33  3281.7 2404.61    3453 2402.46  3815.6 2401.57
  3883.4 2397.98  3886.1 2397.97  3898.4  2398.1  3956.6 2403.15  4037.2  2401.9
  5024.4 2404.23  5235.6 2410.55  5627.6 2414.25  6562.4 2434.41  6763.4 2448.23
  6803.6 2448.52  6894.1 2445.66  6914.2 2447.76  7064.9 2472.04    7085 2474.03
#Mann= 3 , 0 , 0
       0      .1       0  3883.4    .045       0  3898.4      .1       0
#XS Ineff= 2 , 0
         3294.95 2404.49 4825.51         2404.49
Permanent Ineff=
       F       F
Bank Sta=3883.4,3898.4
XS Rating Curve= 0 ,0
Exp/Cntr=0.3,0.1

Chan Stop Cuts=-1
Use User Specified Reach Order=0
Composite Channel Slope=5